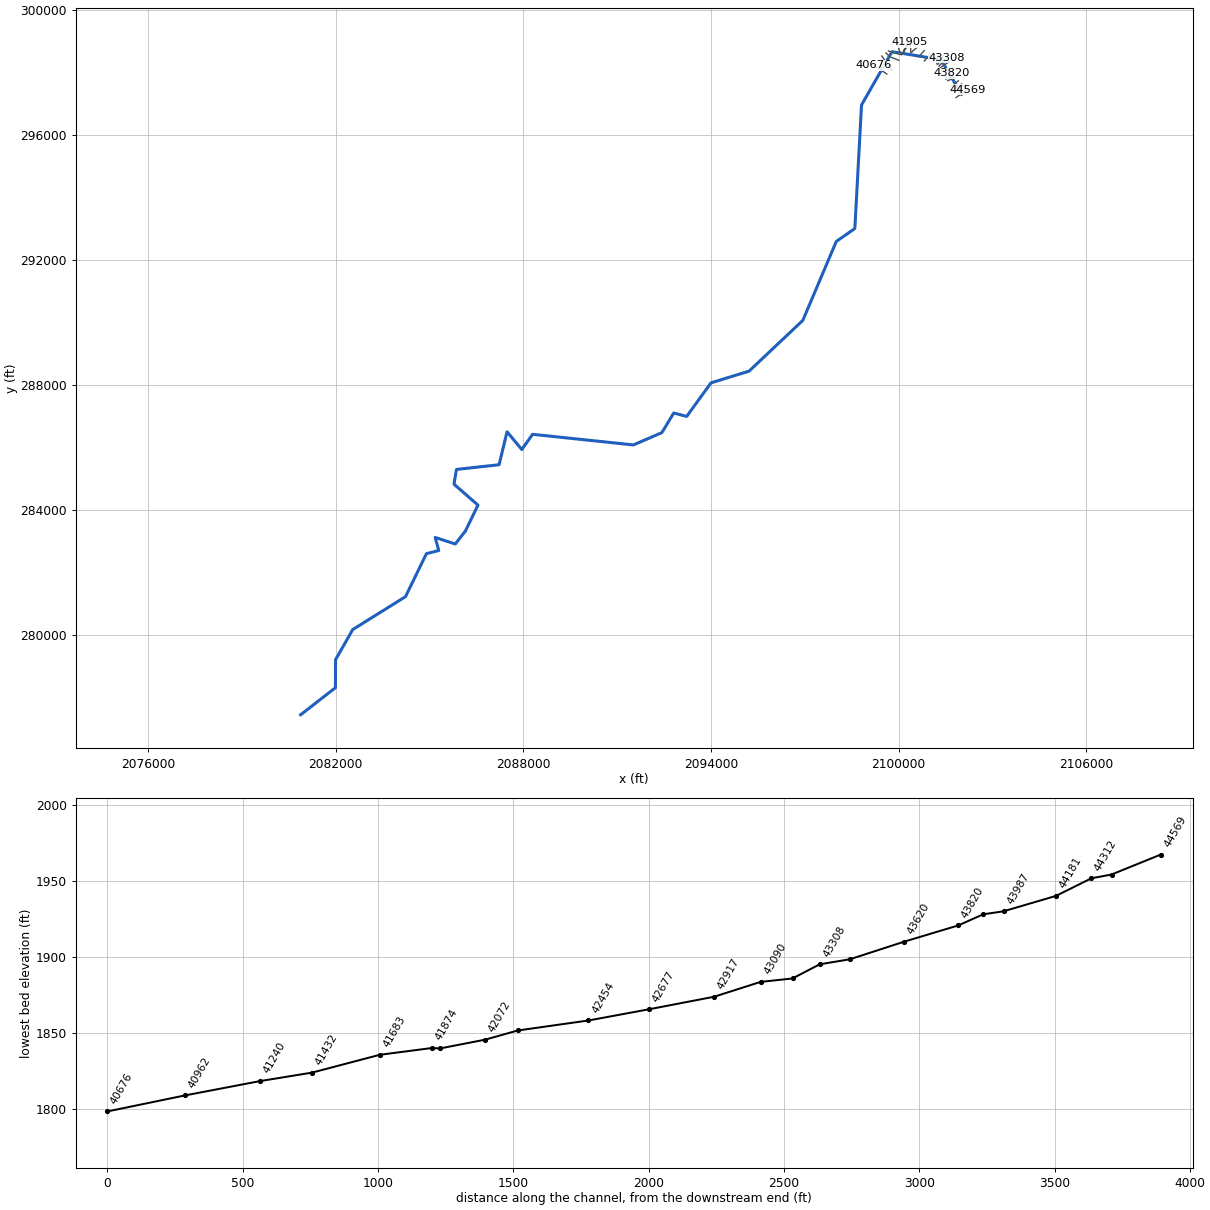
--- MILLCK1.prj (project) ---

Proj Title=MILLCK1
Current Plan=p01
Default Exp/Contr=0.3,0.1
English Units
Geom File=g01
Flow File=f01
Plan File=p01
Y Axis Title=Elevation
X Axis Title(PF)=Main Channel Distance
X Axis Title(XS)=Station
BEGIN DESCRIPTION:
Stream Name- Mill Creek 1
Flood Zone: Zone A
Greenbrier County, WV
County-Wide Study
WVDHSEM-2018-3, Flood Risk Project
HEC-RAS Version: 5.0.7
General Notes:
For the Hydrology Regression was used.
END DESCRIPTION:
DSS Export Rating Curves= 0
DSS Export Rating Curve Sorted= 0
DSS Export Volume Flow Curves= 0
DXF Filename=..\J2.
DXF OffsetX= 0
DXF OffsetY= 0
DXF ScaleX= 1
DXF ScaleY= 10

--- MILLCK1.p01 (plan) ---

Plan Title=Floodplain
Program Version=5.07
Short Identifier=Floodplain
Geom File=g01
Flow File=f01
Subcritical Flow
K Sum by GR= 0
Std Step Tol= 0.01
Critical Tol= 0.01
Num of Std Step Trials= 20
Max Error Tol= 0.3
Flow Tol Ratio= 0.001
Split Flow NTrial= 30
Split Flow Tol= 0.02
Split Flow Ratio= 0.02
Log Output Level= 0
Friction Slope Method= 1
Unsteady Friction Slope Method= 2
Unsteady Bridges Friction Slope Method= 1
Parabolic Critical Depth
Global Vel Dist= 0 , 0 , 0
Global Log Level= 0
CheckData=True
Encroach Param=-1 ,0,0, 0
Computation Interval=1MIN
Output Interval=1HOUR
Instantaneous Interval=1HOUR
Mapping Interval=1HOUR
Computation Time Step Use Courant=        0
Computation Time Step Use Time Series=    0
Computation Time Step Count To Double=0
Computation Time Step Max Doubling=0
Computation Time Step Max Halving=0
Computation Time Step Residence Courant=0
Run HTab= 0
Run UNet= 0
Run Sediment= 0
Run PostProcess= 0
Run WQNet= 0
Run RASMapper= 0
UNET Theta= 1
UNET Theta Warmup= 1
UNET ZTol= 0.02
UNET ZSATol= 0.02
UNET MxIter= 20
UNET Max Iter WO Improvement= 0
UNET MaxInSteps= 0
UNET DtIC= 0
UNET DtMin= 0
UNET MaxCRTS= 20
UNET WFStab= 2
UNET SFStab= 1
UNET WFX= 1
UNET SFX= 1
UNET 1D Methodology=Finite Difference
UNET DSS MLevel= 4
UNET Pardiso=0
UNET DZMax Abort= 100
UNET Use Existing IB Tables=-1
UNET Froude Reduction=False
UNET Froude Limit= 0.8
UNET Froude Power= 4
UNET D1 Cores= 0
UNET D2 Coriolis=0
UNET D2 Cores= 0
UNET D2 Theta= 1
UNET D2 Theta Warmup= 1
UNET D2 Z Tol= 0.01
UNET D2 Volume Tol= 0.01
UNET D2 Max Iterations= 20
UNET D2 Equation= 0
UNET D2 RampUpFraction=0.1
UNET D2 TimeSlices= 1
UNET D2 BCVolumeCheck=0
UNET D1D2 MaxIter= 0
UNET D1D2 ZTol=0.01
UNET D1D2 QTol=0.1
UNET D1D2 MinQTol=1
Write IC File= 0
Write IC File at Fixed DateTime=0
Write IC File at Sim End=0
Echo Input=False
Echo Parameters=False
Echo Output=False
Write Detailed= 0
HDF Write Warmup=0
HDF Write Time Slices=0
HDF Flush=0
HDF Face Node Velocities=0
HDF Compression= 1
HDF Chunk Size= 1
HDF Spatial Parts= 1
HDF Use Max Rows=0
HDF Fixed Rows= 1
Calibration Method= 0
Calibration Iterations= 20
Calibration Max Change=0.05
Calibration Tolerance=0.2
Calibration Maximum=1.5
Calibration Minimum=0.5
Calibration Optimization Method= 1
WQ AD Non Conservative
WQ ULTIMATE=-1
WQ Max Comp Step=1HOUR
WQ Output Interval=15MIN
WQ Output Selected Increments= 0
WQ Output face flow=0
WQ Output face velocity=0
WQ Output face area=0
WQ Output face dispersion=0
WQ Output cell volume=0
WQ Output cell surface area=0
WQ Output cell continuity=0
WQ Output cumulative cell continuity=0
WQ Output face conc=0
WQ Output face dconc_dx=0
WQ Output face courant=0
WQ Output face peclet=0
WQ Output face adv mass=0
WQ Output face disp mass=0
WQ Output cell mass=0
WQ Output cell source sink temp=0
WQ Output nsm pathways=0
WQ Output nsm derived pathways=0
WQ Output MaxMinRange=-1
WQ Daily Max Min Mean=-1
WQ Daily Range=0
WQ Daily Time=0
WQ Create Restart=0
WQ Fixed Restart=0
WQ System Summary=0
WQ Write To DSS=0
WQ Use Fixed Temperature=0
Sorting and Armoring Iterations= 10
XS Update Threshold= 0.02
Bed Roughness Predictor= 0
Hydraulics Update Threshold= 0.02
Energy Slope Method= 1
Volume Change Method= 1
Sediment Retention Method= 0
XS Weighting Method= 0
Number of US Weighted Cross Sections= 1
Number of DS Weighted Cross Sections= 1
Upstream XS Weight=0
Main XS Weight=1
Downstream XS Weight=0
Number of DS XS's Weighted with US Boundary= 1
Upstream Boundary Weight= 1
Weight of XSs Associated with US Boundary= 0
Number of US XS's Weighted with DS Boundary= 1
Downstream Boundary Weight= 0.5
Weight of XSs Associated with DS Boundary= 0.5
Percentile Method= 0
Sediment Output Level= 3
Mass or Volume Output= 0
Output Increment Type= 1
Profile and TS Output Increment= 1
XS Output Flag= 0
XS Output Increment= 10
Write Gradation File= 0
Read Gradation Hotstart= 0
Write HDF5 File= 1
Write Binary Output= 1
Write DSS Sediment File= 0
SV Curve= 0
Specific Gage Flag= 0

--- MILLCK1.f01 (steady flow) ---

Flow Title=Flow
Program Version=5.07
Number of Profiles= 6
Profile Names=f1p,f10p,f4p,f2p,f02p,f1pplus
River Rch & RM=ALUMRN,Main            ,13094
     682     363     481     579     950    1010
River Rch & RM=ALUMRN,Main            ,11059
     799     428     565     679    1110    1180
River Rch & RM=ALUMRN,Main            ,9883
     965     521     686     821    1340    1430
River Rch & RM=ALUMRN,Main            ,6456
    1080     584     767     917    1490    1590
River Rch & RM=ALUMRN,Main            ,284
    1350     740     968    1160    1860    2000
River Rch & RM=KTCHNCK,Main            ,41842
     743     397     525     631    1030    1100
River Rch & RM=KTCHNCK,Main            ,37328
     832     446     589     707    1150    1230
River Rch & RM=KTCHNCK,Main            ,35092
     926     499     657     788    1280    1370
River Rch & RM=KTCHNCK,Main            ,33009
    1030     557     732     876    1420    1520
River Rch & RM=KTCHNCK,Main            ,28691
    1150     622     817     977    1580    1700
River Rch & RM=KTCHNCK,Main            ,21556
    1810    1000    1300    1550    2480    2680
River Rch & RM=KTCHNCK,Main            ,16488
    2900    1630    2110    2490    3930    4290
River Rch & RM=KTCHNCK,Main            ,10721
    3870    2200    2830    3340    5220    5730
River Rch & RM=KTCHNCKT1,Main            ,9111
     634     336     447     537     884     938
River Rch & RM=KTCHNCKT1,Main            ,6856
     715     381     504     606     994    1060
River Rch & RM=KTCHNCKT1,Main            ,2501
     856     459     606     727    1190    1270
River Rch & RM=MILLCK1,Main            ,44569
     546     288     383     462     764     808
River Rch & RM=MILLCK1,Main            ,42192
     668     355     471     567     931     988
River Rch & RM=MILLCK1,Main            ,40676
     926     498     657     787    1280    1370
River Rch & RM=MILLCK1,Main            ,39243
    1580     868    1130    1350    2160    2330
River Rch & RM=MILLCK1,Main            ,32901
    1760     973    1270    1510    2410    2610
River Rch & RM=MILLCK1,Main            ,26603
    1970    1090    1420    1690    2700    2920
River Rch & RM=MILLCK1,Main            ,16549
    2620    1470    1890    2240    3550    3870
River Rch & RM=MILLCK1,Main            ,5376
    3090    1740    2250    2650    4180    4570
River Rch & RM=MILLCK1T1,Main            ,2820
     564     298     397     478     789     835
River Rch & RM=RENICKCK,Main            ,22028
     617     327     434     523     861     913
River Rch & RM=RENICKCK,Main            ,19013
     695     370     490     589     967    1030
River Rch & RM=RENICKCK,Main            ,16528
     937     505     665     797    1300    1390
River Rch & RM=RENICKCK,Main            ,13874
    1040     565     742     888    1440    1540
River Rch & RM=RENICKCK,Main            ,9049
    1170     638     837    1000    1620    1740
River Rch & RM=SNAKERN,Main            ,20697
     463     243     324     392     650     685
River Rch & RM=SNAKERN,Main            ,20190
     763     408     539     648    1060    1130
River Rch & RM=SNAKERN,Main            ,19342
     852     457     603     724    1180    1260
River Rch & RM=SNAKERN,Main            ,16967
    1190     644     845    1010    1630    1750
River Rch & RM=SNAKERN,Main            ,11910
    1330     728     952    1140    1830    1970
River Rch & RM=SNAKERN,Main            ,6596
    1480     812    1060    1260    2030    2190
Boundary for River Rch & Prof#=ALUMRN,Main            , 1
Up Type= 0
Dn Type= 3
Dn Slope=0.008838
Boundary for River Rch & Prof#=ALUMRN,Main            , 2
Up Type= 0
Dn Type= 3
Dn Slope=0.008838
Boundary for River Rch & Prof#=ALUMRN,Main            , 3
Up Type= 0
Dn Type= 3
Dn Slope=0.008838
Boundary for River Rch & Prof#=ALUMRN,Main            , 4
Up Type= 0
Dn Type= 3
Dn Slope=0.008838
Boundary for River Rch & Prof#=ALUMRN,Main            , 5
Up Type= 0
Dn Type= 3
Dn Slope=0.008838
Boundary for River Rch & Prof#=ALUMRN,Main            , 6
Up Type= 0
Dn Type= 3
Dn Slope=0.008838
Boundary for River Rch & Prof#=KTCHNCK,Main            , 1
Up Type= 0
Dn Type= 3
Dn Slope=0.005801
Boundary for River Rch & Prof#=KTCHNCK,Main            , 2
Up Type= 0
Dn Type= 3
Dn Slope=0.005801
Boundary for River Rch & Prof#=KTCHNCK,Main            , 3
Up Type= 0
Dn Type= 3
Dn Slope=0.005801
Boundary for River Rch & Prof#=KTCHNCK,Main            , 4
Up Type= 0
Dn Type= 3
Dn Slope=0.005801
Boundary for River Rch & Prof#=KTCHNCK,Main            , 5
Up Type= 0
Dn Type= 3
Dn Slope=0.005801
Boundary for River Rch & Prof#=KTCHNCK,Main            , 6
Up Type= 0
Dn Type= 3
Dn Slope=0.005801
Boundary for River Rch & Prof#=KTCHNCKT1,Main            , 1
Up Type= 0
Dn Type= 3
Dn Slope=0.024951
Boundary for River Rch & Prof#=KTCHNCKT1,Main            , 2
Up Type= 0
Dn Type= 3
Dn Slope=0.024951
Boundary for River Rch & Prof#=KTCHNCKT1,Main            , 3
Up Type= 0
Dn Type= 3
Dn Slope=0.024951
Boundary for River Rch & Prof#=KTCHNCKT1,Main            , 4
Up Type= 0
Dn Type= 3
Dn Slope=0.024951
Boundary for River Rch & Prof#=KTCHNCKT1,Main            , 5
Up Type= 0
Dn Type= 3
Dn Slope=0.024951
Boundary for River Rch & Prof#=KTCHNCKT1,Main            , 6
Up Type= 0
Dn Type= 3
Dn Slope=0.024951
Boundary for River Rch & Prof#=MILLCK1,Main            , 1
Up Type= 0
Dn Type= 3
Dn Slope=0.000839
Boundary for River Rch & Prof#=MILLCK1,Main            , 2
Up Type= 0
Dn Type= 3
Dn Slope=0.000839
Boundary for River Rch & Prof#=MILLCK1,Main            , 3
Up Type= 0
Dn Type= 3
Dn Slope=0.000839
Boundary for River Rch & Prof#=MILLCK1,Main            , 4
Up Type= 0
Dn Type= 3
Dn Slope=0.000839
Boundary for River Rch & Prof#=MILLCK1,Main            , 5
Up Type= 0
Dn Type= 3
Dn Slope=0.000839
Boundary for River Rch & Prof#=MILLCK1,Main            , 6
Up Type= 0
Dn Type= 3
Dn Slope=0.000839
Boundary for River Rch & Prof#=MILLCK1T1,Main            , 1
Up Type= 0
Dn Type= 3
Dn Slope=0.000001
Boundary for River Rch & Prof#=MILLCK1T1,Main            , 2
Up Type= 0
Dn Type= 3
Dn Slope=0.000001
Boundary for River Rch & Prof#=MILLCK1T1,Main            , 3
Up Type= 0
Dn Type= 3
Dn Slope=0.000001
Boundary for River Rch & Prof#=MILLCK1T1,Main            , 4
Up Type= 0
Dn Type= 3
Dn Slope=0.000001
Boundary for River Rch & Prof#=MILLCK1T1,Main            , 5
Up Type= 0
Dn Type= 3
Dn Slope=0.000001
Boundary for River Rch & Prof#=MILLCK1T1,Main            , 6
Up Type= 0
Dn Type= 3
Dn Slope=0.000001
Boundary for River Rch & Prof#=RENICKCK,Main            , 1
Up Type= 0
Dn Type= 3
Dn Slope=0.003087
Boundary for River Rch & Prof#=RENICKCK,Main            , 2
Up Type= 0
Dn Type= 3
Dn Slope=0.003087
Boundary for River Rch & Prof#=RENICKCK,Main            , 3
Up Type= 0
Dn Type= 3
Dn Slope=0.003087
Boundary for River Rch & Prof#=RENICKCK,Main            , 4
Up Type= 0
Dn Type= 3
Dn Slope=0.003087
Boundary for River Rch & Prof#=RENICKCK,Main            , 5
Up Type= 0
Dn Type= 3
Dn Slope=0.003087
Boundary for River Rch & Prof#=RENICKCK,Main            , 6
Up Type= 0
Dn Type= 3
Dn Slope=0.003087
Boundary for River Rch & Prof#=SNAKERN,Main            , 1
Up Type= 0
Dn Type= 3
Dn Slope=0.008894
Boundary for River Rch & Prof#=SNAKERN,Main            , 2
Up Type= 0
Dn Type= 3
Dn Slope=0.008894
Boundary for River Rch & Prof#=SNAKERN,Main            , 3
Up Type= 0
Dn Type= 3
Dn Slope=0.008894
Boundary for River Rch & Prof#=SNAKERN,Main            , 4
Up Type= 0
Dn Type= 3
Dn Slope=0.008894
Boundary for River Rch & Prof#=SNAKERN,Main            , 5
Up Type= 0
Dn Type= 3
Dn Slope=0.008894
Boundary for River Rch & Prof#=SNAKERN,Main            , 6
Up Type= 0
Dn Type= 3
Dn Slope=0.008894
DSS Import GetInterval= 0
DSS Import GetPeak= 0
DSS Import FillOption= 0

--- MILLCK1.g01 (geometry) ---

Geom Title=Geometry
Program Version=5.07

River Reach=MILLCK1         ,Main
Reach XY= 30
2102014.89342803297291.3588332982101350.31011152298400.733911127
2099788.59145018298653.0342595432098813.76498777296953.381490871
2098600.22342011293000.2565231322098007.34140378292586.194031045
2096937.02891186290061.8883841342095218.71312279288439.752848879
2094000.65748802288064.4058305472093223.92118061286991.836125299
2092811.07423729287101.5583467932092431.56023252286474.475283384
2091522.53252304286080.3779744652088296.49074677286419.614172623
2087952.74077812285933.1558279542087481.21284977286501.558562547
2087226.59590495 285446.687968882085863.85191128285297.044567376
2085784.68507487 284826.21119146 2086551.3518486284155.377887458
2086151.35199243 283328.989120292085826.35198626282912.322302714
2085182.60196143283122.7392047052085298.57417044282702.600281209
2084904.82397369282604.6834822892084234.16750661281228.017600462
2082545.79621145280175.5167527052081999.26843309279213.016709208
2081995.10177478278317.8780795482080882.78805453277451.993000299

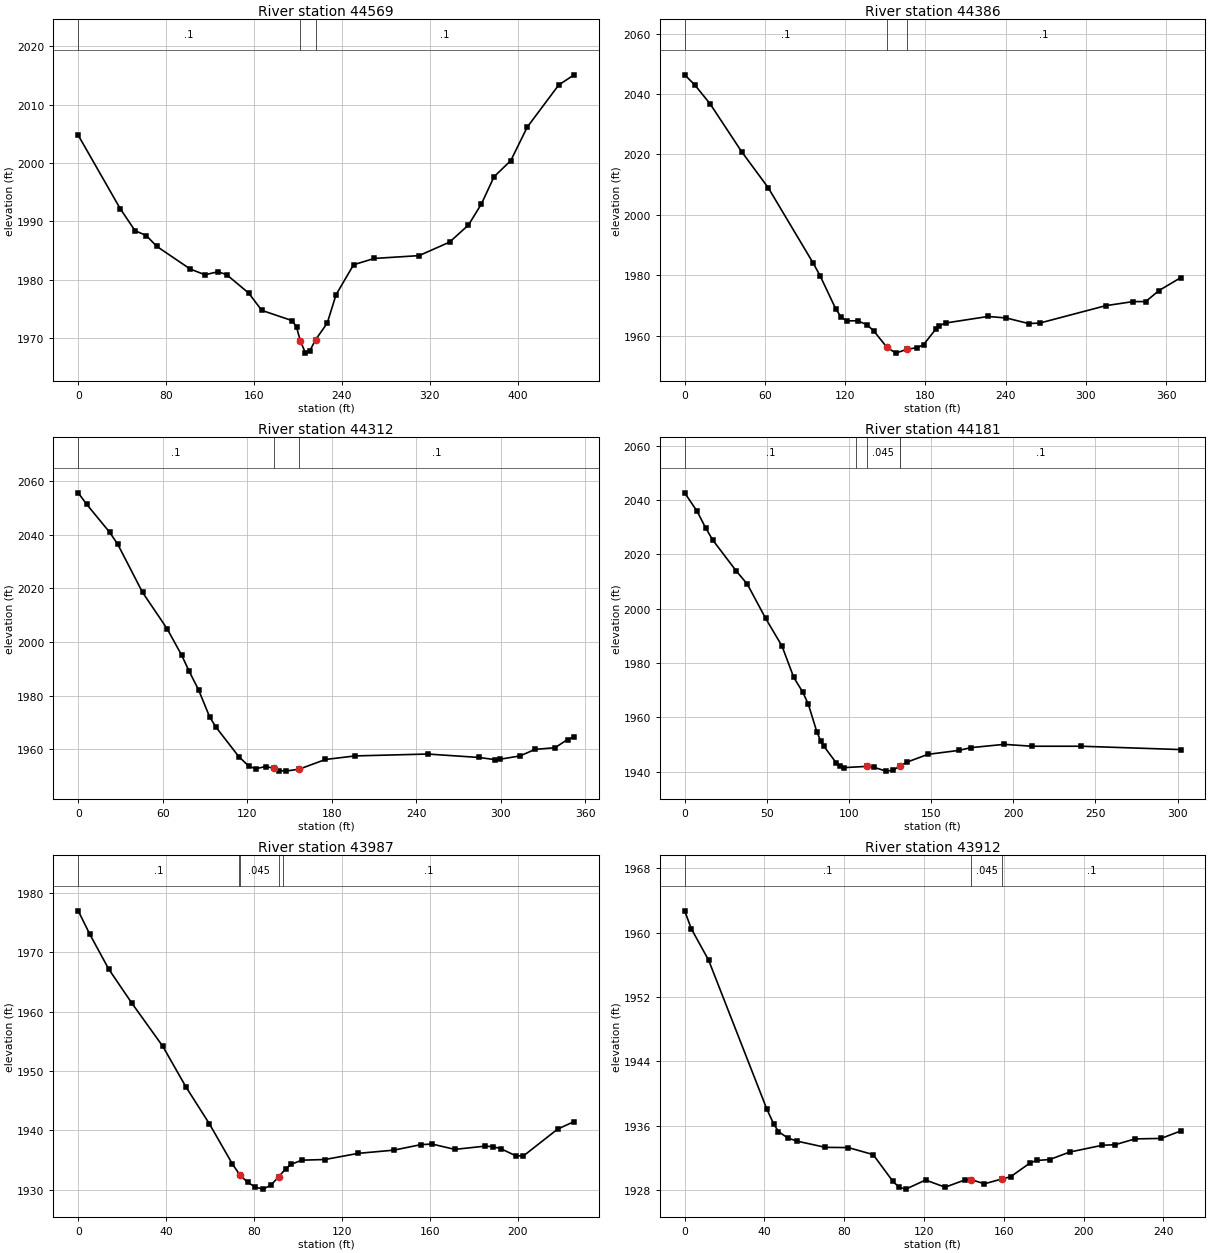
Type RM Length L Ch R = 1 ,44569   ,182.5,182.6,182.9
XS GIS Cut Line= 2
2101835.91117445297187.0250524582102208.30708319 297442.23353155
#Sta/Elev= 30
       0 2004.75    38.3 1992.14    51.7 1988.39    61.9 1987.56    71.6 1985.69
     102 1981.81   115.4 1980.83   127.3 1981.35   135.1 1980.85   155.2 1977.69
   167.1 1974.73   194.9 1972.96   198.8 1971.85  202.141969.538   206.9  1967.4
   210.6  1967.7   216.1  1969.7   226.7 1972.54   234.7  1977.4   250.7 1982.55
   269.6 1983.63   310.3 1984.11   338.1 1986.43   355.3 1989.36     367 1992.95
   378.6 1997.64   393.8 2000.39   408.8 2006.14   437.5 2013.37   451.5  2015.1
#Mann= 3 , 0 , 0
       0      .1       0  202.14    .045       0   216.1      .1       0
Bank Sta=202.14,216.1
XS Rating Curve= 0 ,0
Exp/Cntr=0.3,0.1

Type RM Length L Ch R = 1 ,44386   ,74.4,74.3,73.5
XS GIS Cut Line= 2
2101770.80697393297357.5978740452102070.28636184297576.348092705
#Sta/Elev= 30
       0 2046.33     7.5 2043.02      19 2036.74    42.5 2020.96    62.5 2008.96
    95.9 1984.19   101.2 1979.92   112.9 1968.96   117.2 1966.05   121.3 1964.93
   129.3 1964.95   136.4 1963.64   141.6 1961.49  151.271956.162   157.9 1954.25
     166 1955.49     174 1956.08   178.7 1957.06     188 1962.31   190.4 1963.33
   195.1 1964.21   226.9 1966.38   240.5 1965.88   257.2 1964.04   265.5 1964.19
   314.8 1969.94   335.1 1971.29   344.8 1971.31   354.7 1974.95   370.9  1979.2
#Mann= 3 , 0 , 0
       0      .1       0  151.27    .045       0     166      .1       0
Bank Sta=151.27,166
XS Rating Curve= 0 ,0
Exp/Cntr=0.3,0.1

Type RM Length L Ch R = 1 ,44312   ,130.4,131.1,131.8
XS GIS Cut Line= 2
2101729.24847657297424.5869490962102020.28657767297622.764644402
#Sta/Elev= 30
       0 2055.67       6 2051.39    22.3 2040.96    28.1 2036.43    45.7 2018.48
    63.1 2004.95    73.5    1995    78.7 1989.12    85.4 1982.18    93.4 1971.91
      98 1968.07   114.1 1957.14   121.2  1953.6     126 1952.67   133.1  1953.5
   138.71952.874   142.5 1952.01   147.2 1951.78   156.9 1952.51   175.5 1956.13
   196.8 1957.46   248.2 1958.16   284.2 1956.89   295.8 1956.09   299.8 1956.25
   313.7 1957.46   324.3 1959.89   338.5 1960.52   347.4 1963.57   352.1 1964.54
#Mann= 3 , 0 , 0
       0      .1       0   138.7    .045       0   156.9      .1       0
Bank Sta=138.7,156.9
XS Rating Curve= 0 ,0
Exp/Cntr(USF)=0,0
Exp/Cntr=0.3,0.1

Type RM Length L Ch R = 1 ,44181   ,196.2,193.8,190.4
XS GIS Cut Line= 2
2101671.84883854297530.7750211212101906.22369787297720.879299715
#Sta/Elev= 30
       0  2042.6     7.6 2035.76    12.7 2029.76      17  2025.3    31.4 2013.83
    38.1 2009.02    49.2 1996.48    59.2 1986.25    66.4 1974.66    71.9 1969.23
    75.3 1964.74    80.4  1954.7    82.7 1951.45    84.6 1949.46    92.1 1943.35
    94.4 1942.09    97.2 1941.51   110.7 1941.95   115.4 1941.57   122.6 1940.21
   126.8 1940.52     131 1942.09   135.3 1943.52     148 1946.38   166.7 1947.82
   174.2 1948.85   194.4 1950.06   211.3 1949.37   241.3 1949.37   301.8 1948.14
#Mann= 5 ,-1 , 0
       0      .1       0  104.17      .1       0   110.7    .045       0
     131      .1       0  131.21      .1       0
Bank Sta=110.7,131
XS Rating Curve= 0 ,0
Exp/Cntr=0.3,0.1

Type RM Length L Ch R = 1 ,43987   ,78,75.1,71.1
XS GIS Cut Line= 3
2101570.28637761297728.6916200522101690.07780468297774.264691621
2101782.43974083297805.394382088
#Sta/Elev= 30
       0 1977.01     5.3 1973.04    13.9 1967.18    24.5 1961.39    38.5 1954.16
      49 1947.33    59.6 1941.15    70.1 1934.36    73.6 1932.45    77.1 1931.25
    80.6 1930.42    84.2  1930.1    87.7  1930.8    91.2 1932.17    94.3  1933.5
    96.9 1934.28   101.7 1934.98   112.2 1935.09   127.4 1936.13   143.6 1936.67
   155.9  1937.6   160.9  1937.7   171.3  1936.8   185.2 1937.35   188.6 1937.25
   192.1 1936.94     199 1935.73   202.5 1935.69   218.1 1940.22   225.6 1941.49
#Mann= 5 ,-1 , 0
       0      .1       0   73.07      .1       0    73.6    .045       0
    91.2      .1       0   93.08      .1       0
Bank Sta=73.6,91.2
XS Rating Curve= 0 ,0
Exp/Cntr=0.3,0.1

Type RM Length L Ch R = 1 ,43912   ,86.4,92.2,100.3
XS GIS Cut Line= 3
2101511.66461006297778.1334298172101589.61765777297831.111229235
2101744.01010179297828.083926411
#Sta/Elev= 30
       0  1962.7     3.3 1960.48      12 1956.57    41.2 1938.06    44.6 1936.24
      47 1935.28    51.7 1934.47    56.4 1934.08    70.6 1933.31    82.1 1933.28
    94.5 1932.41   104.4 1929.09   107.6 1928.34   110.9 1928.12   120.8 1929.25
   130.6 1928.36   140.5 1929.26   143.7  1929.3   150.3 1928.78   159.2 1929.39
   163.4 1929.65   173.3 1931.39   176.6 1931.68   183.1  1931.8     193 1932.72
   209.4 1933.57   215.9 1933.64   225.8 1934.36   238.9 1934.42   248.7 1935.34
#Mann= 3 , 0 , 0
       0      .1       0   143.7    .045       0   159.2      .1       0
Bank Sta=143.7,159.2
XS Rating Curve= 0 ,0
Exp/Cntr(USF)=0,0
Exp/Cntr=0.3,0.1

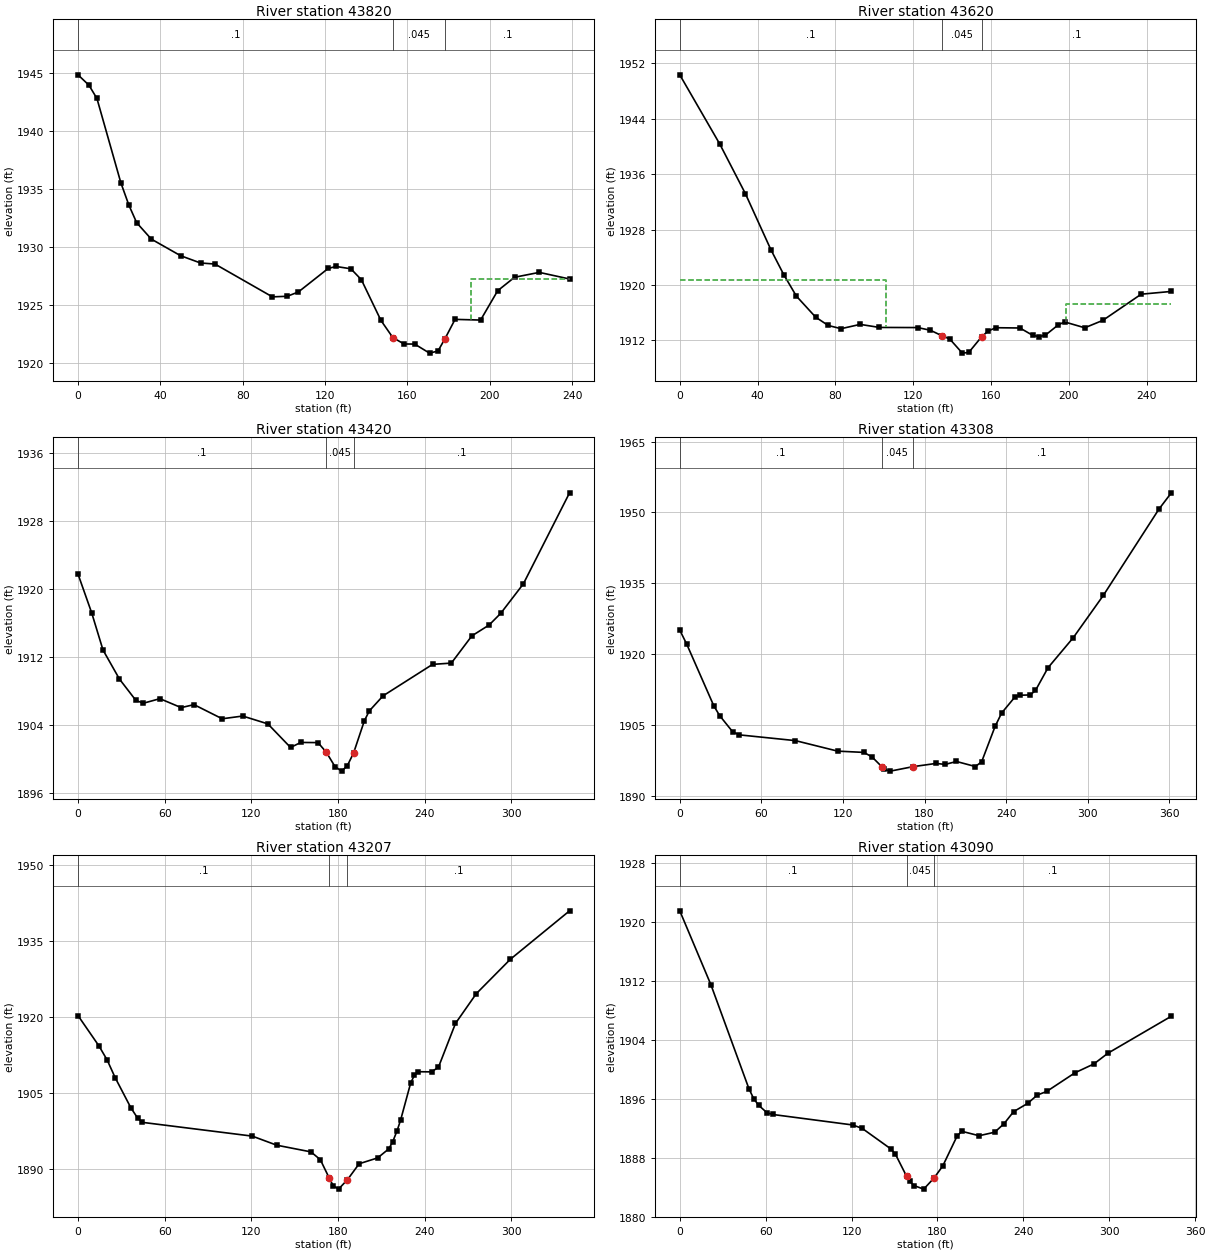
Type RM Length L Ch R = 1 ,43820   ,203.9,199.9,191.9
XS GIS Cut Line= 4
2101486.95288286297828.9522462932101595.02582943297896.660444215
2101667.94267836297952.6501616242101684.86948177297961.764644712
#Sta/Elev= 30
       0  1944.8     5.3 1943.91     9.2 1942.76    20.8  1935.5    24.7 1933.57
    28.5 1932.05    35.6 1930.64    49.8 1929.21    59.5 1928.58    66.5 1928.49
    94.4 1925.66   101.6 1925.71     107 1926.08   121.5 1928.11   125.3 1928.28
   132.5 1928.08   137.6 1927.14   147.1 1923.63  152.89 1922.15   158.3  1921.6
   163.5 1921.59   170.7 1920.81   174.8 1920.99  178.251922.068   183.1 1923.72
   195.5 1923.66   203.8 1926.19     212 1927.35     224 1927.77   238.7  1927.2
#Mann= 3 ,-1 , 0
       0      .1       0  152.89    .045       0  178.25      .1       0
#XS Ineff= 2 , 0
                             191         1927.22
Permanent Ineff=
       F       F
Bank Sta=152.89,178.25
XS Rating Curve= 0 ,0
Exp/Cntr=0.3,0.1

Type RM Length L Ch R = 1 ,43620   ,194.2,200.3,205.2
XS GIS Cut Line= 2
2101359.34880736298049.0042996262101611.95296094298050.306462377
#Sta/Elev= 30
       0 1950.34    20.6 1940.32    33.7 1933.19    46.8  1925.1    53.4  1921.5
    59.9 1918.39    69.8 1915.35    76.3 1914.14    82.9 1913.68    92.7  1914.3
   102.6 1913.86   122.3 1913.84   128.8 1913.45  134.981912.625   138.7  1912.2
   145.2 1910.15   148.5 1910.25  155.081912.503   158.4 1913.33   162.4 1913.82
   174.8 1913.78   181.3 1912.73   184.6 1912.53   187.9 1912.75   194.4 1914.21
   197.7 1914.66   208.1 1913.81   217.4 1914.88   237.1 1918.66   252.6 1919.06
#Mann= 3 ,-1 , 0
       0      .1       0  134.98    .045       0  155.08      .1       0
#XS Ineff= 2 , 0
          106.11 1920.74  198.64         1917.22
Permanent Ineff=
       F       F
Bank Sta=134.98,155.08
XS Rating Curve= 0 ,0
Exp/Cntr=0.3,0.1

Type RM Length L Ch R = 1 ,43420   ,109.3,112,113.2
XS GIS Cut Line= 2
2101335.91119018298146.6606003792101619.76560935298334.160553455
#Sta/Elev= 30
       0 1921.75     9.5 1917.18    17.3 1912.83    28.7 1909.41    40.1  1906.9
    45.3 1906.58    56.7 1907.11    71.4 1906.06    80.3 1906.41    99.8 1904.75
     114 1905.07   131.4 1904.15   147.1 1901.38   154.2 1901.97   166.1 1901.95
  171.85 1900.82   177.9 1899.12   182.5  1898.6   186.4 1899.24  190.741900.735
   198.2 1904.52   201.6 1905.67   211.1 1907.44   245.4 1911.14   258.4 1911.29
   272.6 1914.49   284.5 1915.76   292.6 1917.14   308.2 1920.59   340.2 1931.29
#Mann= 3 ,-1 , 0
       0      .1       0  171.85    .045       0  190.74      .1       0
Bank Sta=171.85,190.74
XS Rating Curve= 0 ,0
Exp/Cntr=0.3,0.1

Type RM Length L Ch R = 1 ,43308   ,102.1,100.1,100.1
XS GIS Cut Line= 2
2101291.08567648298193.0394256882101536.97834835298458.004105345
#Sta/Elev= 30
       0 1925.11     5.2 1922.08      25 1909.11    29.3 1907.03    38.9  1903.6
    43.8 1902.95    85.1 1901.73   116.1 1899.51   135.4 1899.24   141.4 1898.28
  148.461896.249   150.1 1895.65   154.8 1895.28   171.51896.224   188.5 1896.91
   195.1  1896.7   203.5 1897.32   217.4 1896.25     222 1897.26   231.9 1904.75
   236.7 1907.57   246.3  1910.9     250 1911.33   257.8  1911.4   261.6 1912.35
   270.8 1917.15   289.4 1923.52   311.5 1932.46   352.4 1950.71   361.5 1954.15
#Mann= 3 ,-1 , 0
       0      .1       0  148.46    .045       0   171.5      .1       0
Bank Sta=148.46,171.5
XS Rating Curve= 0 ,0
Exp/Cntr(USF)=0,0
Exp/Cntr=0.3,0.1

Type RM Length L Ch R = 1 ,43207   ,114.8,117.8,121
XS GIS Cut Line= 3
2101249.97369802298250.8270587182101335.91119018298369.316651121
2101437.47365111298534.681477875
#Sta/Elev= 30
       0 1920.24    14.6 1914.21    20.2 1911.47    25.7 1908.01    36.6 1902.05
    41.3    1900    44.5 1899.17   120.7 1896.45   137.6 1894.66   161.3 1893.34
   167.8 1891.81     174 1888.16   176.7 1886.68   180.4 1885.99   186.6 1887.85
   194.7    1891   207.5 1892.15   215.2 1893.93   217.9 1895.31     221 1897.55
   223.4 1899.61   230.4 1906.96   232.9 1908.43   235.3 1909.16   244.8 1909.13
   249.6 1910.04   261.4 1918.69   275.8 1924.56   299.4 1931.35   340.4 1940.91
#Mann= 3 , 0 , 0
       0      .1       0     174    .045       0   186.6      .1       0
Bank Sta=174,186.6
XS Rating Curve= 0 ,0
Exp/Cntr=0.3,0.1

Type RM Length L Ch R = 1 ,43090   ,166.4,172.3,178.1
XS GIS Cut Line= 2
2101222.62992069298265.1501927972101261.69250661298606.295835957
#Sta/Elev= 30
       0 1921.53    21.8 1911.47    48.3 1897.38    51.6 1896.04      55 1895.14
    60.9 1894.12    64.8 1893.88   120.9 1892.45   127.5 1891.98   147.3 1889.22
   150.6  1888.5  158.391885.507   160.5 1884.81   163.8 1884.21   170.4 1883.74
  177.611885.245   183.7 1886.88   193.6 1890.89   196.9  1891.6   209.1 1890.99
     220 1891.47   226.6 1892.64   233.2 1894.26   243.1 1895.39   249.7 1896.51
   256.3    1897   276.1 1899.54   289.3 1900.74   299.2 1902.21   343.4 1907.22
#Mann= 3 ,-1 , 0
       0      .1       0  158.39    .045       0  177.61      .1       0
Bank Sta=158.39,177.61
XS Rating Curve= 0 ,0
Exp/Cntr=0.3,0.1

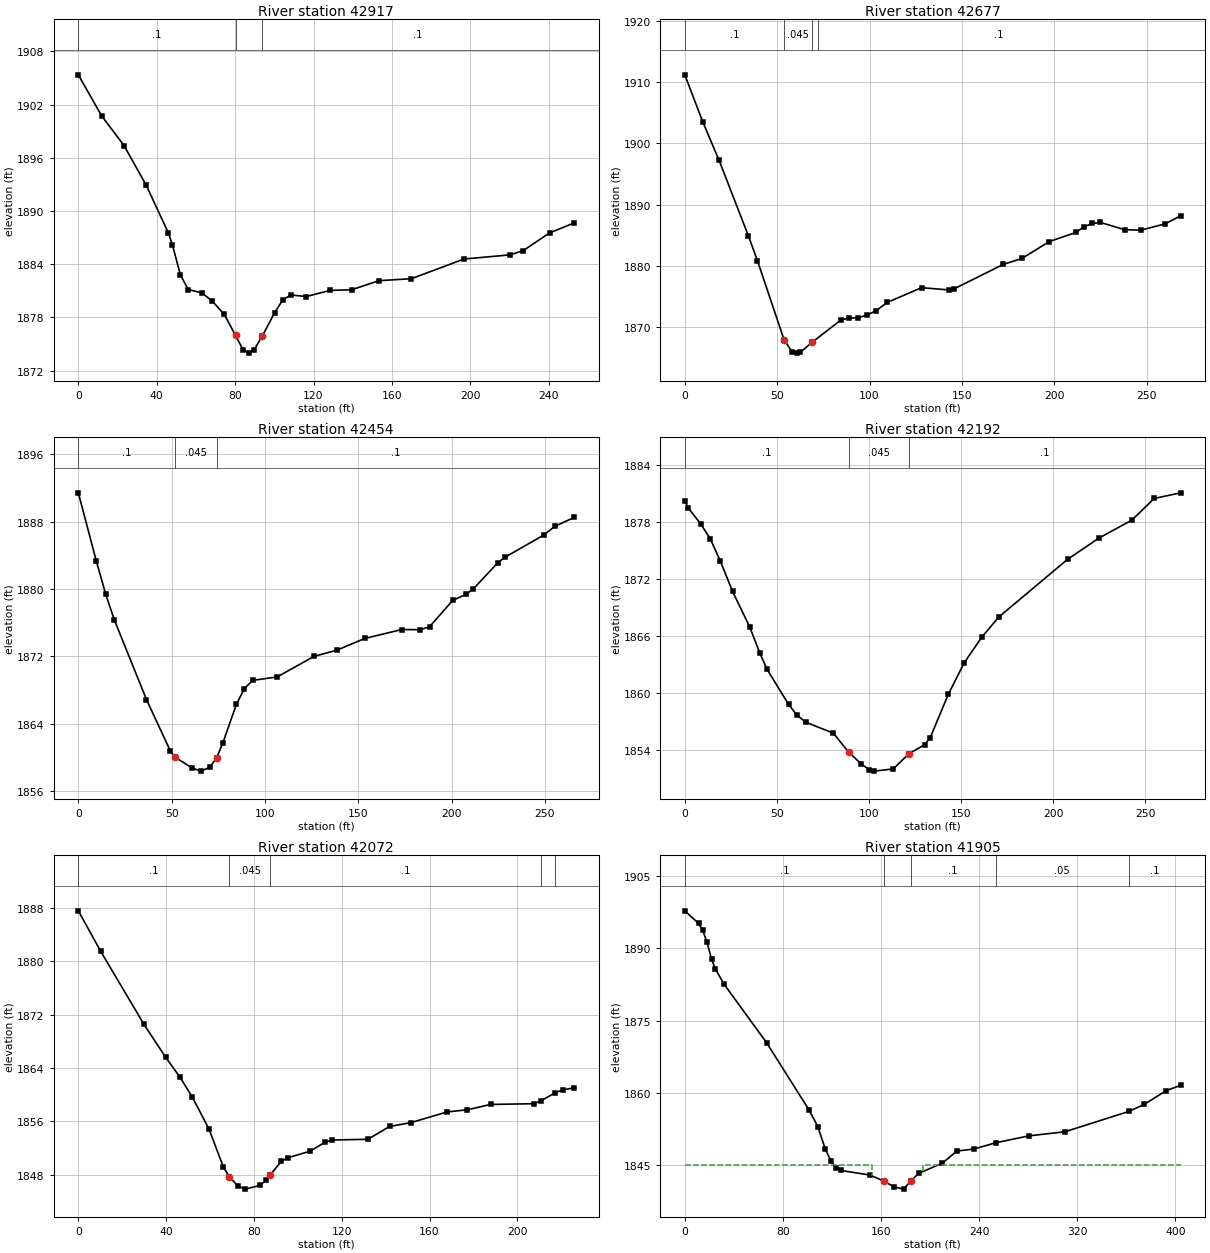
Type RM Length L Ch R = 1 ,42917   ,247.7,240.1,228
XS GIS Cut Line= 3
2101127.57794544 298326.347905042101049.45310169298437.025177121
2101023.41115904298551.608281299
#Sta/Elev= 30
       0 1905.35    11.9 1900.72    23.3 1897.38    34.6 1892.91      46  1887.5
      48 1886.18    52.1 1882.77    56.1 1881.14    63.1 1880.76    68.4 1879.82
    74.5 1878.33    80.2 1875.97    80.2 1875.96    84.2  1874.3    87.2 1873.97
    89.6 1874.32    93.8 1875.87   100.2 1878.54   104.3 1879.96   108.4 1880.53
   116.3 1880.35   128.4 1881.04   139.6 1881.12   153.3 1882.14   169.9 1882.36
   196.8 1884.58   220.3 1885.05   227.1 1885.54   240.5 1887.53     253 1888.65
#Mann= 3 , 0 , 0
       0      .1       0    80.2    .045       0    93.8      .1       0
Bank Sta=80.2,93.8
XS Rating Curve= 0 ,0
Exp/Cntr=0.3,0.1

Type RM Length L Ch R = 1 ,42677   ,223.7,223.7,223.5
XS GIS Cut Line= 2
2100818.98407444298354.9938451352100997.36954445298555.514769539
#Sta/Elev= 30
       0 1911.21     9.8 1903.48    18.6 1897.22    34.4 1884.93    39.3 1880.88
   53.691867.979    58.1 1865.96    60.9 1865.76    62.5 1865.89      69 1867.55
    84.4 1871.15    88.7 1871.49    93.6 1871.52    98.6 1871.97   103.5 1872.68
   109.7 1874.06   128.2 1876.45     143 1876.08   145.9 1876.28   172.4 1880.25
   182.5 1881.22   197.3 1883.98   211.8 1885.47   216.2 1886.42   220.6 1886.93
     225  1887.1   238.1 1885.92   246.9 1885.84   260.1 1886.88   268.4 1888.19
#Mann= 4 ,-1 , 0
       0      .1       0   53.69    .045       0      69      .1       0
   72.01      .1       0
Bank Sta=53.69,69
XS Rating Curve= 0 ,0
Exp/Cntr=0.3,0.1

Type RM Length L Ch R = 1 ,42454   ,264,261.7,259.2
XS GIS Cut Line= 2
2100641.90076718 298489.108406292100817.68223977298688.327167958
#Sta/Elev= 30
       0  1891.4     9.6 1883.34    14.7 1879.36    19.3 1876.33    36.5 1866.89
    49.3  1860.8    51.8 1860.06    61.1 1858.75    65.8  1858.4    70.4 1858.85
    74.1 1859.97    77.4 1861.72    84.7 1866.32      89 1868.19    93.4 1869.16
   106.6 1869.57   126.2    1872   138.6 1872.75   153.5 1874.13   173.3 1875.19
   183.2 1875.17   188.2 1875.52   200.6 1878.64   207.6 1879.35   211.6 1879.99
   224.7 1883.09   228.5 1883.75   249.4 1886.39   255.3 1887.42   265.7 1888.48
#Mann= 3 , 0 , 0
       0      .1       0    51.8    .045       0    74.1      .1       0
Bank Sta=51.8,74.1
XS Rating Curve= 0 ,0
Exp/Cntr=0.3,0.1

Type RM Length L Ch R = 1 ,42192   ,103,119.6,132.8
XS GIS Cut Line= 3
2100416.64039093298629.7334531252100453.09865135298676.608359382
2100613.25515518298812.025083289
#Sta/Elev= 30
       0 1880.23       2 1879.44     8.6  1877.8    13.9 1876.21    19.3 1873.88
    25.9 1870.71    35.3 1866.94    40.6 1864.27    44.6 1862.53    56.3 1858.84
      61 1857.67    65.7 1856.96    80.7  1855.8   88.881853.816    95.9 1852.56
   100.2 1851.96   102.9 1851.82   113.1 1852.05  121.651853.646   130.2  1854.6
   133.2 1855.34   143.1 1859.93   151.7 1863.22   161.1 1865.87   170.4 1868.01
   207.8 1874.08   224.8 1876.31   242.6 1878.19   254.8 1880.47   269.1 1881.06
#Mann= 3 ,-1 , 0
       0      .1       0   88.88    .045       0  121.65      .1       0
Bank Sta=88.88,121.65
XS Rating Curve= 0 ,0
Exp/Cntr=0.3,0.1

Type RM Length L Ch R = 1 ,42072   ,173.5,167.5,160.2
XS GIS Cut Line= 2
2100391.90093911298631.035615876 2100374.9738076298856.295992121
#Sta/Elev= 30
       0 1887.59    10.2 1881.51    29.9 1870.55    39.8  1865.6    46.4 1862.58
    51.9 1859.65    59.5 1854.86    66.1 1849.13   68.751847.661    72.7  1846.3
      76 1845.82    82.6 1846.37    85.5 1847.13    87.31847.889    92.4 1849.97
    95.7 1850.55   105.6 1851.52   112.2 1852.82   115.5 1853.19   131.9  1853.3
   141.8 1855.22   151.6 1855.81   168.1 1857.41   177.3 1857.73   187.8 1858.53
   207.6 1858.64   210.9  1859.1   217.1 1860.25   220.7 1860.72   225.9 1861.02
#Mann= 5 ,-1 , 0
       0      .1       0   68.75    .045       0    87.3      .1       0
   210.9     .05       0   217.1      .1       0
Bank Sta=68.75,87.3
XS Rating Curve= 0 ,0
Exp/Cntr=0.5,0.3

Type RM Length L Ch R = 1 ,41905   ,30.2,30.7,31.1
XS GIS Cut Line= 4
2100155.20784295298591.2650261222100192.70776793298699.598470882
 2100285.0688037298838.487300709 2100335.7632561298950.292851374
#Sta/Elev= 30
       0 1897.79    11.2 1895.18    14.6 1893.76    18.1 1891.23    21.9  1887.7
      25 1885.68      32 1882.57    66.7 1870.41   101.4 1856.41   108.4 1853.02
   114.6 1848.29   119.3 1845.84   123.3 1844.47   127.2  1843.9   150.9 1842.96
  162.311841.698   170.6 1840.49   178.4 1840.03   184.21841.723   190.8 1843.32
     210 1845.43   221.8 1847.94   235.5 1848.34   253.3 1849.64   280.4 1851.08
   309.8 1851.93   362.2 1856.17   374.5 1857.61   392.6 1860.49   404.2 1861.57
#Mann= 5 ,-1 , 0
       0      .1       0  162.31    .045       0   184.2      .1       0
   253.3     .05       0   362.2      .1       0
#XS Ineff= 2 , 0
           152.3    1845   194.2            1845
Permanent Ineff=
       F       F
Bank Sta=162.31,184.2
XS Rating Curve= 0 ,0
Exp/Cntr=0.5,0.3

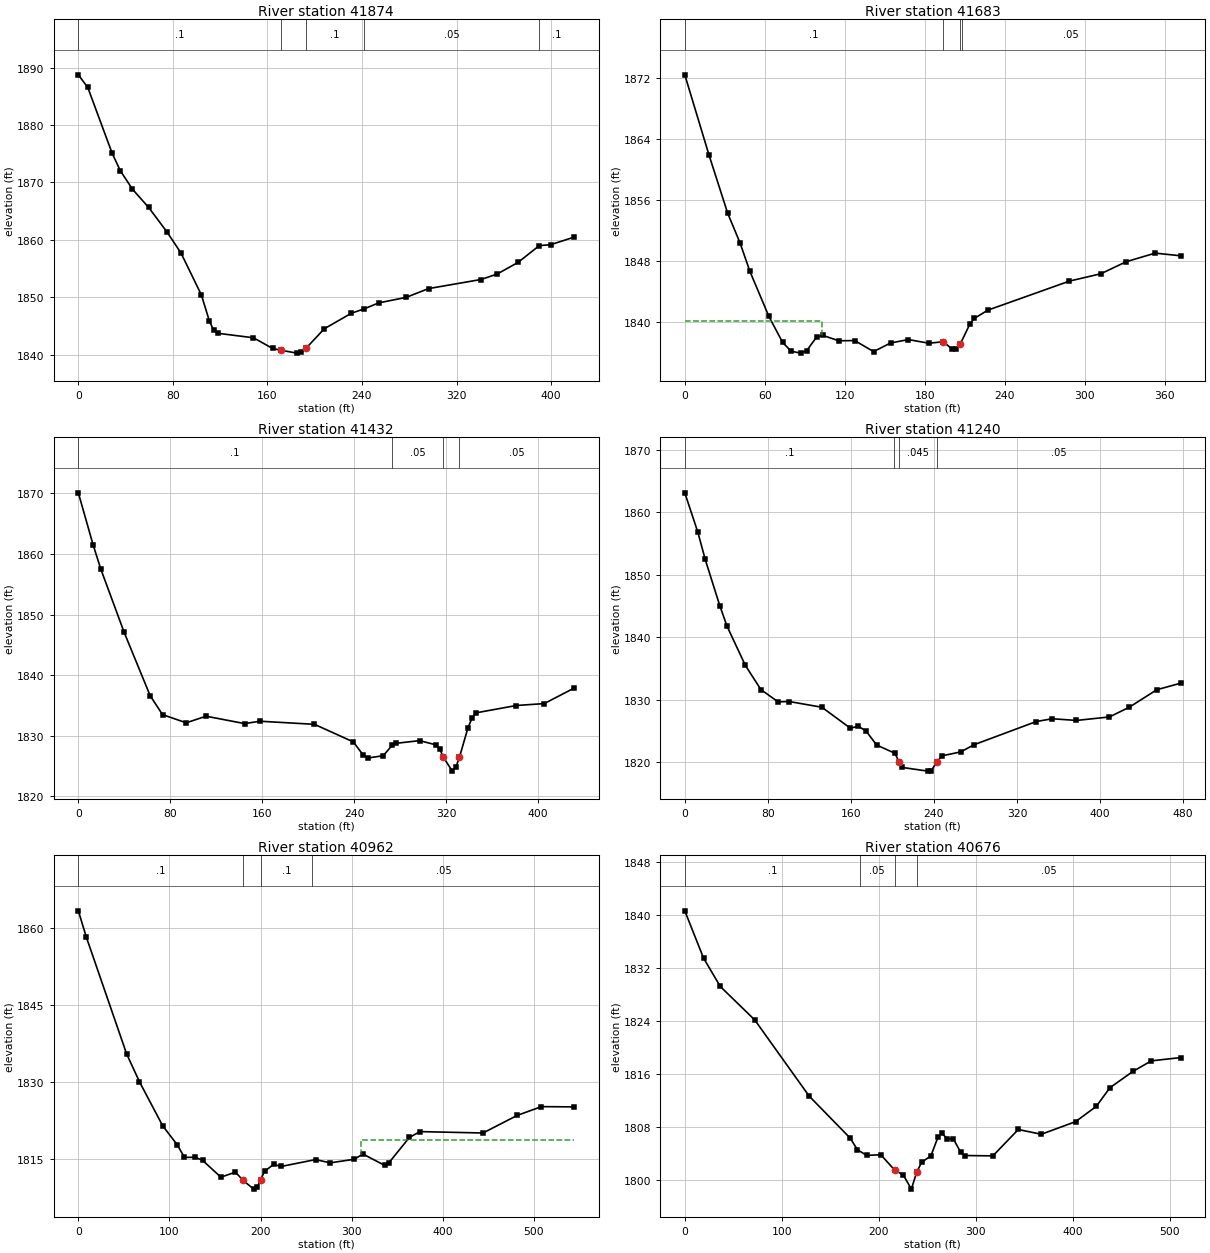
Type RM Length L Ch R = 1 ,41874   ,183.8,191.6,199.2
XS GIS Cut Line= 4
2100130.90211728298584.3208142972100170.48537144298713.487222627
2100253.12431377298848.9039465492100310.76330611298960.709497213
#Sta/Elev= 30
       0 1888.73       8 1886.53    28.6 1875.08    35.5 1872.05    45.7 1868.85
    59.5 1865.65      75 1861.39    86.8 1857.74   104.1 1850.43   110.9 1845.87
   114.4 1844.33   117.8 1843.76   148.2 1842.97   164.3 1841.12  171.261840.809
   184.9  1840.3   188.8 1840.44  192.791841.176   208.1 1844.54     231 1847.24
   241.5 1847.98   254.1 1849.04   277.3    1850   296.3 1851.53   340.6 1853.11
   354.2 1854.05     372 1856.08     390 1859.01   399.6 1859.17   419.5 1860.49
#Mann= 5 ,-1 , 0
       0      .1       0  171.26    .045       0  192.79      .1       0
   241.5     .05       0     390      .1       0
Bank Sta=171.26,192.79
XS Rating Curve= 0 ,0
Exp/Cntr=0.5,0.3

Type RM Length L Ch R = 1 ,41683   ,246,250.2,259
XS GIS Cut Line= 3
2100096.32803944298563.327089876 2100018.2028676 298689.62933071
2099960.91131553298905.775223881
#Sta/Elev= 30
       0 1872.41    18.2 1861.86    32.2 1854.23    41.4 1850.37    48.8 1846.63
    63.1 1840.69    73.4 1837.28    79.8 1836.12      87 1835.87    91.5  1836.2
    98.9 1837.98   103.7 1838.19   115.6 1837.49   127.5 1837.52   141.7 1836.07
   154.4  1837.2   167.8 1837.65   183.2 1837.17  193.881837.365   200.2 1836.47
   203.6 1836.46  206.851837.109   213.8 1839.64   217.2 1840.42   227.4 1841.51
   288.7 1845.33   312.2 1846.29   331.4 1847.88     353    1849   372.1 1848.65
#Mann= 4 ,-1 , 0
       0      .1       0  193.88    .045       0  206.85      .1       0
  207.98     .05       0
#XS Ineff= 2 , 0
          102.63 1840.03
Permanent Ineff=
       F       F
Bank Sta=193.88,206.85
XS Rating Curve= 0 ,0
Exp/Cntr=0.3,0.1

Type RM Length L Ch R = 1 ,41432   ,201.4,192.8,188.2
XS GIS Cut Line= 3
2100089.81755379298558.1187669632099808.56746012298628.431290373
2099675.75506169298677.910522133
#Sta/Elev= 30
       0 1870.07    12.8 1861.53    19.5 1857.53    39.8  1847.1    62.5 1836.62
    73.3 1833.49    93.9 1832.14   111.2 1833.23   144.7 1832.01   158.2  1832.4
   205.5 1831.89   239.4 1828.99   247.8 1826.86   251.9 1826.33   265.4 1826.71
   273.2 1828.43   276.2 1828.75   297.1  1829.2   311.1 1828.51   314.6 1827.84
  317.521826.533   325.5 1824.17   328.6  1824.8  331.78 1826.48   339.1 1831.27
   342.6 1832.87   346.1 1833.78   381.1 1834.99   405.6 1835.31   431.6 1837.87
#Mann= 4 ,-1 , 0
       0      .1       0   272.8     .05       0  317.52    .045       0
  331.78     .05       0
Bank Sta=317.52,331.78
XS Rating Curve= 0 ,0
Exp/Cntr=0.3,0.1

Type RM Length L Ch R = 1 ,41240   ,284.1,277.2,271.2
XS GIS Cut Line= 3
 2100003.8800616298381.0354597122099716.11948228298491.712731794
 2099596.3280552298611.504158884
#Sta/Elev= 30
       0 1863.11    12.6 1856.79    19.6 1852.49    33.7 1845.06    40.7 1841.76
    58.3 1835.51    73.3 1831.63    89.9 1829.66   100.5 1829.72   132.1  1828.8
   159.6 1825.44   167.2 1825.78   174.9 1824.94   184.8 1822.76   202.4 1821.44
  206.631820.031   209.5 1819.17   234.1 1818.58   237.6 1818.67  242.711820.064
   248.1 1821.04   265.7 1821.65   278.9 1822.82   338.7 1826.52   354.1 1826.96
   377.3 1826.69   409.1 1827.25   428.4 1828.82   454.7  1831.6   477.7 1832.65
#Mann= 4 ,-1 , 0
       0      .1       0  201.98     .05       0  206.63    .045       0
  242.71     .05       0
Bank Sta=206.63,242.71
XS Rating Curve= 0 ,0
Exp/Cntr=0.3,0.1

Type RM Length L Ch R = 1 ,40962   ,279.4,286.4,288.3
XS GIS Cut Line= 2
2099773.41136244 298069.837591292099462.21349403298516.452183634
#Sta/Elev= 30
       0 1863.32     8.6  1858.3      53 1835.49    67.1 1830.07    92.6  1821.5
   108.6  1817.8   116.5 1815.36   128.5 1815.37   136.5 1814.76   156.5  1811.5
   172.5 1812.49  180.35 1810.96   192.5 1809.18   196.5 1809.55  200.031811.022
   204.5 1812.65   214.3 1813.98   222.7 1813.59   260.5 1814.93   276.5 1814.29
   302.8 1814.99   312.5    1816   336.5 1813.78   340.5 1814.22   363.5 1819.24
     375 1820.37   444.2  1820.1   481.9 1823.53   508.4 1825.23   544.3 1825.18
#Mann= 4 ,-1 , 0
       0      .1       0  180.35    .045       0  200.03      .1       0
  257.06     .05       0
#XS Ineff= 2 , 0
                          310.02         1818.66
Permanent Ineff=
       F       F
Bank Sta=180.35,200.03
XS Rating Curve= 0 ,0
Exp/Cntr=0.3,0.1

Type RM Length L Ch R = 1 ,40676   ,303.6,312.8,329.3
XS GIS Cut Line= 2
2099622.36966977297939.629190296 2099196.5883691298222.181446716
#Sta/Elev= 30
       0 1840.67    19.3 1833.54    36.6 1829.25    72.1  1824.2   128.1 1812.72
   170.5 1806.36   177.8 1804.64   187.3 1803.76     202 1803.86  216.191801.561
   225.2  1800.8   233.5 1798.67  239.121801.276   244.1 1802.72   253.6 1803.69
   261.1 1806.57     265 1807.12   270.1 1806.31   276.8 1806.24   284.3 1804.24
   288.6 1803.74   317.5 1803.69   343.7 1807.67   367.4 1806.95   402.7 1808.85
     424 1811.15   438.2 1813.98   461.9 1816.44   480.8 1818.03     511 1818.52
#Mann= 4 ,-1 , 0
       0      .1       0  180.55     .05       0  216.19    .045       0
  239.12     .05       0
Bank Sta=216.19,239.12
XS Rating Curve= 0 ,0
Exp/Cntr=0.3,0.1