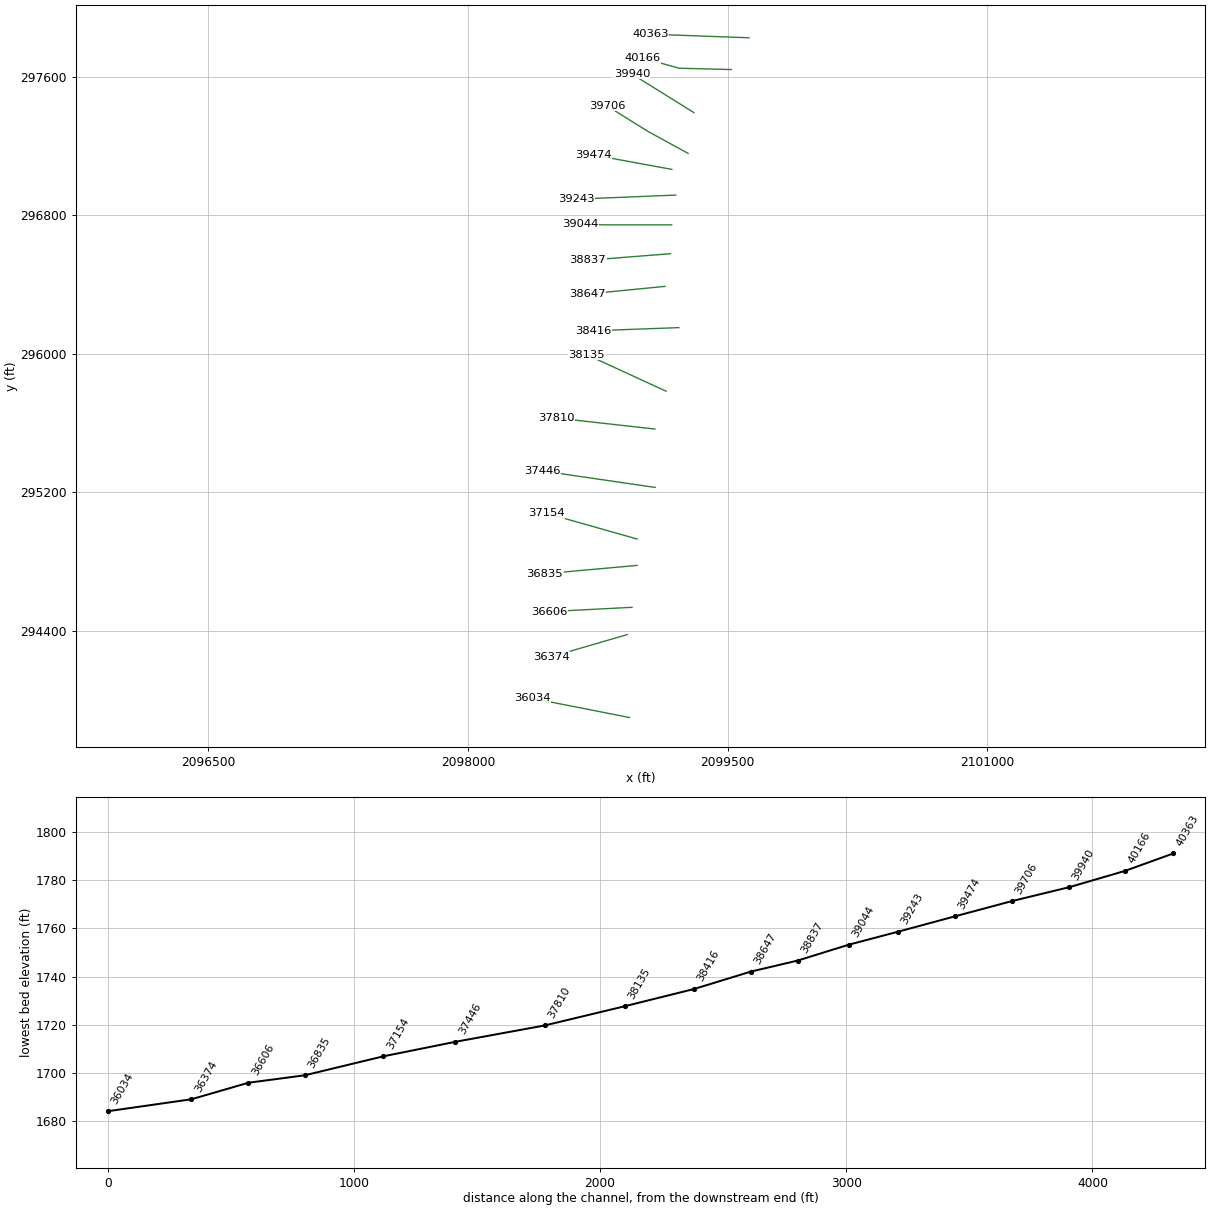
HEC-RAS study MILLCK1.prj: MILLCK1

--- MILLCK1.g01 (geometry) --- (continued)

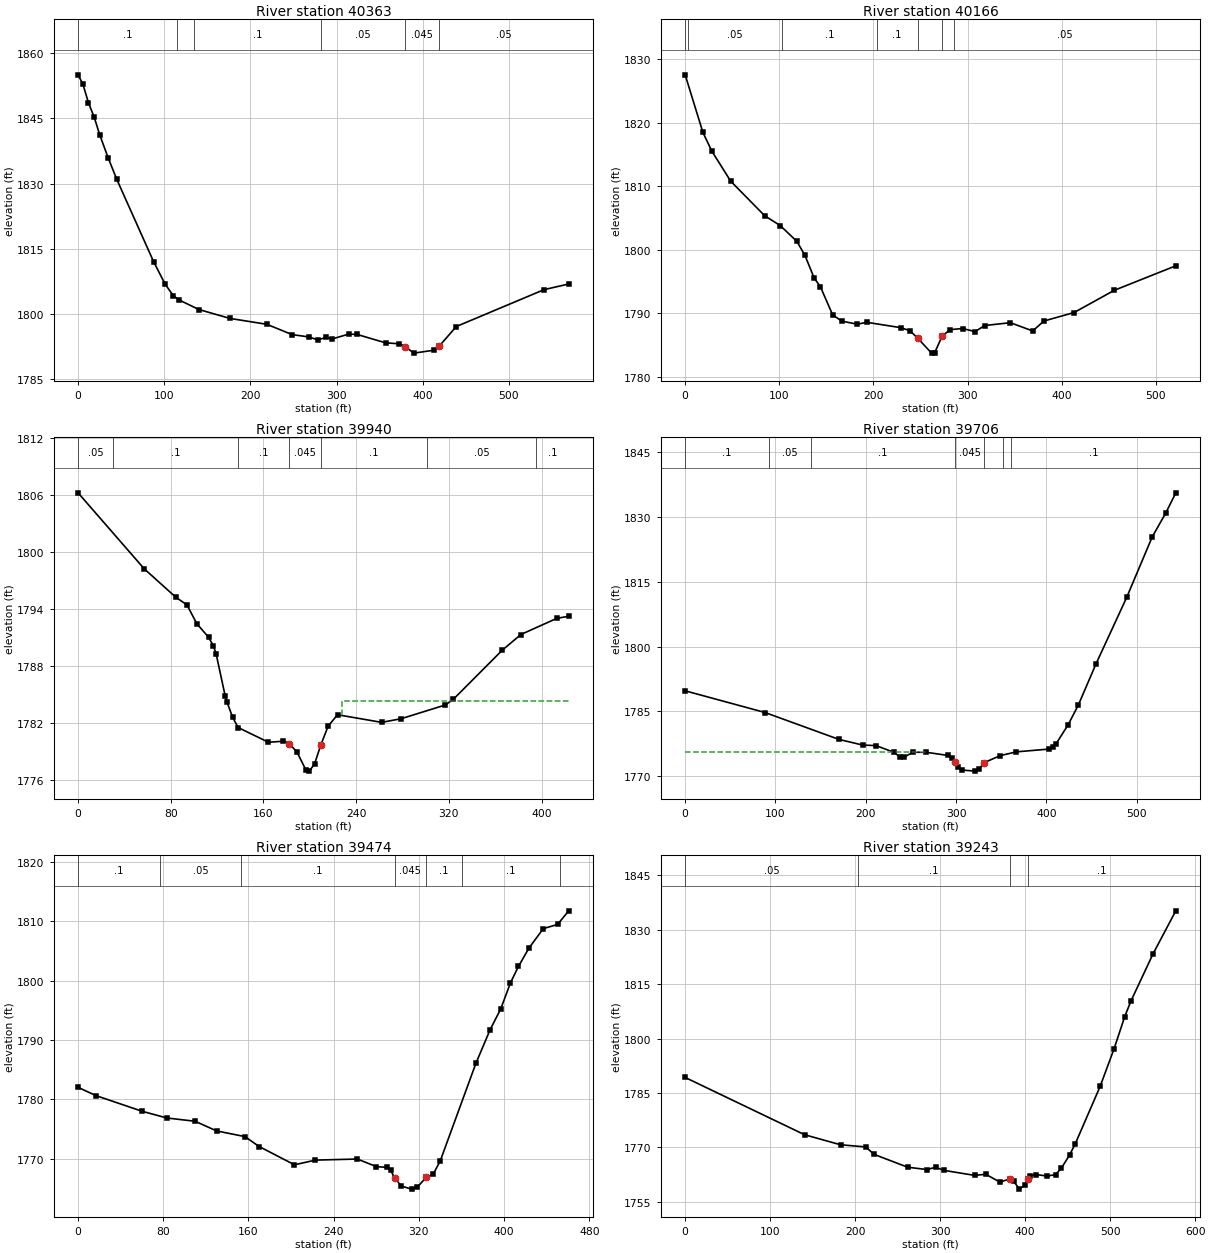
Type RM Length L Ch R = 1 ,40363   ,195.8,196.9,199.8
XS GIS Cut Line= 2
2099623.67183253 297826.347920792099054.66115952297847.181212455
#Sta/Elev= 30
       0 1855.05     5.6 1852.91    12.1 1848.59    18.7  1845.3    25.3 1841.14
    35.1 1835.83      45 1830.95    87.6 1812.06   100.8 1806.93   110.6 1804.17
   117.2 1803.22   140.2 1801.01   176.3 1798.96     219 1797.61   248.5 1795.23
   268.2 1794.69   278.1 1794.01   287.9 1794.59   294.5 1794.21   314.2 1795.36
     324 1795.26   356.9 1793.34   372.6 1793.12  379.591792.467   389.7 1790.97
   412.7 1791.63  418.861792.512   438.9 1797.09   540.7 1805.58   569.4 1806.89
#Mann= 6 ,-1 , 0
       0      .1       0  114.48      .1       0  134.97      .1       0
   281.8     .05       0  379.59    .045       0  418.86     .05       0
Bank Sta=379.59,418.86
XS Rating Curve= 0 ,0
Exp/Cntr=0.3,0.1

Type RM Length L Ch R = 1 ,40166   ,231.9,226.6,218.7
XS GIS Cut Line= 3
 2099522.1093716297642.7541278752099220.02598628297650.566776291
2099009.08841601297709.160491124
#Sta/Elev= 30
       0 1827.51    18.8 1818.46    28.4 1815.48    48.4 1810.77    84.5 1805.33
   100.9  1803.8   118.6 1801.31   127.1 1799.14     137 1795.54   143.6 1794.17
   156.7 1789.72   166.5 1788.75   182.9 1788.27   192.8 1788.57   228.9 1787.73
   238.7 1787.25  246.951786.075   261.7 1783.72     265 1783.78  272.941786.397
   281.4 1787.42   294.6 1787.59   307.9 1787.11   318.1 1788.06   345.3 1788.51
   369.1 1787.21     381 1788.77   413.1 1790.11   455.7  1793.6   521.1 1797.46
#Mann= 7 ,-1 , 0
       0      .1       0    3.02     .05       0  103.26      .1       0
   203.5      .1       0  246.95    .045       0  272.94      .1       0
  286.04     .05       0
Bank Sta=246.95,272.94
XS Rating Curve= 0 ,0
Exp/Cntr=0.3,0.1

Type RM Length L Ch R = 1 ,39940   ,233.8,233.6,234.2
XS GIS Cut Line= 3
2099305.96347845297394.0564625412099054.66115952297550.306478128
2098946.58821294297618.014676049
#Sta/Elev= 30
       0  1806.2    57.1 1798.22    84.5 1795.22      94 1794.43   102.4 1792.47
   112.6 1791.04   116.7 1790.15   119.1 1789.31   126.9  1784.9   128.6  1784.2
   133.4 1782.63   138.1 1781.56   164.3 1780.01   177.2 1780.12   182.11779.874
   188.8 1779.01   196.5 1777.13   199.6 1776.98   204.2 1777.77  209.391779.707
   215.8  1781.7   223.9  1782.9     262  1782.1   278.7 1782.48   316.8 1783.92
   323.9 1784.53     366 1789.67   382.1 1791.32   413.1 1793.02   423.4 1793.24
#Mann= 7 ,-1 , 0
       0     .05       0   30.48      .1       0  138.12      .1       0
   182.1    .045       0  209.39      .1       0  300.77     .05       0
  395.33      .1       0
#XS Ineff= 2 , 0
                          227.33         1784.33
Permanent Ineff=
       F       F
Bank Sta=182.1,209.39
XS Rating Curve= 0 ,0
Exp/Cntr=0.3,0.1

Type RM Length L Ch R = 1 ,39706   ,225.9,231.6,236.5
XS GIS Cut Line= 3
2099272.10921544297158.3791123782099041.64051628297284.681353211
2098803.35916868297433.118720382
#Sta/Elev= 30
       0 1789.77    88.5 1784.75   170.4 1778.53   196.6 1777.23   211.5  1777.1
   230.8 1775.58   238.1 1774.49   242.9  1774.5   252.7 1775.57     267 1775.56
     291 1774.83   295.6 1774.17  298.721773.292   302.7 1772.07   306.5 1771.45
   321.5  1771.2   325.8 1771.76  331.36 1773.18     349 1774.78     367 1775.66
   403.1  1776.3     407 1776.71   410.8  1777.5   424.2  1781.9   435.4 1786.42
   455.1    1796   489.1 1811.37   517.4 1825.37   532.5 1830.93   543.5 1835.55
#Mann= 7 ,-1 , 0
       0      .1       0   93.07     .05       0  139.81      .1       0
  298.72    .045       0  331.36      .1       0  352.49      .1       0
  360.69      .1       0
#XS Ineff= 2 , 0
          266.49 1775.67
Permanent Ineff=
       F       F
Bank Sta=298.72,331.36
XS Rating Curve= 0 ,0
Exp/Cntr=0.3,0.1

Type RM Length L Ch R = 1 ,39474   ,229.6,231.7,233.3
XS GIS Cut Line= 2
2099178.35907486297065.9314626312098725.23432493 297149.26462929
#Sta/Elev= 30
       0 1782.03    16.6 1780.65    59.9 1778.01    83.3 1776.87     110 1776.31
     130 1774.69   156.7 1773.73     170 1772.06   203.2 1768.98   222.9 1769.77
   262.3 1769.95   280.1 1768.67   290.1 1768.55   293.4 1768.05  297.351766.791
   303.4 1765.41   313.1 1764.88   318.7 1765.24  326.751766.843   333.5 1767.41
   340.1 1769.64   373.5 1786.05   386.8  1791.7   396.9 1795.25     406 1799.63
   413.5  1802.4   423.5 1805.53   436.9 1808.78   450.2 1809.47   460.7 1811.77
#Mann= 7 ,-1 , 0
       0      .1       0   76.61     .05       0  153.42      .1       0
  297.35    .045       0  326.75      .1       0  360.73      .1       0
  452.21      .1       0
Bank Sta=297.35,326.75
XS Rating Curve= 0 ,0
Exp/Cntr=0.3,0.1

Type RM Length L Ch R = 1 ,39243   ,198.1,198.4,199.1
XS GIS Cut Line= 2
2099200.49452928296917.4937673812098623.67186403296894.056478292
#Sta/Elev= 30
       0 1789.27   140.6 1773.48   182.9 1770.72   212.5 1770.13   222.3 1768.07
   261.7 1764.55   284.7 1763.88   294.7 1764.55   304.4 1763.67   340.5 1762.29
   353.7 1762.59   370.1 1760.47  381.871761.246   386.5 1760.72   393.1  1758.5
   399.6  1759.6  403.451761.417   406.2 1762.17   412.8 1762.52   425.9  1762.1
   435.8  1762.5   442.8 1764.32   452.3 1767.91   458.8 1770.88   488.3 1786.83
   504.7  1797.2   517.1 1805.96   524.4 1810.28   550.7 1823.42   577.3 1835.19
#Mann= 4 ,-1 , 0
       0     .05       0  203.12      .1       0  381.87    .045       0
  403.45      .1       0
Bank Sta=381.87,403.45
XS Rating Curve= 0 ,0
Exp/Cntr=0.3,0.1

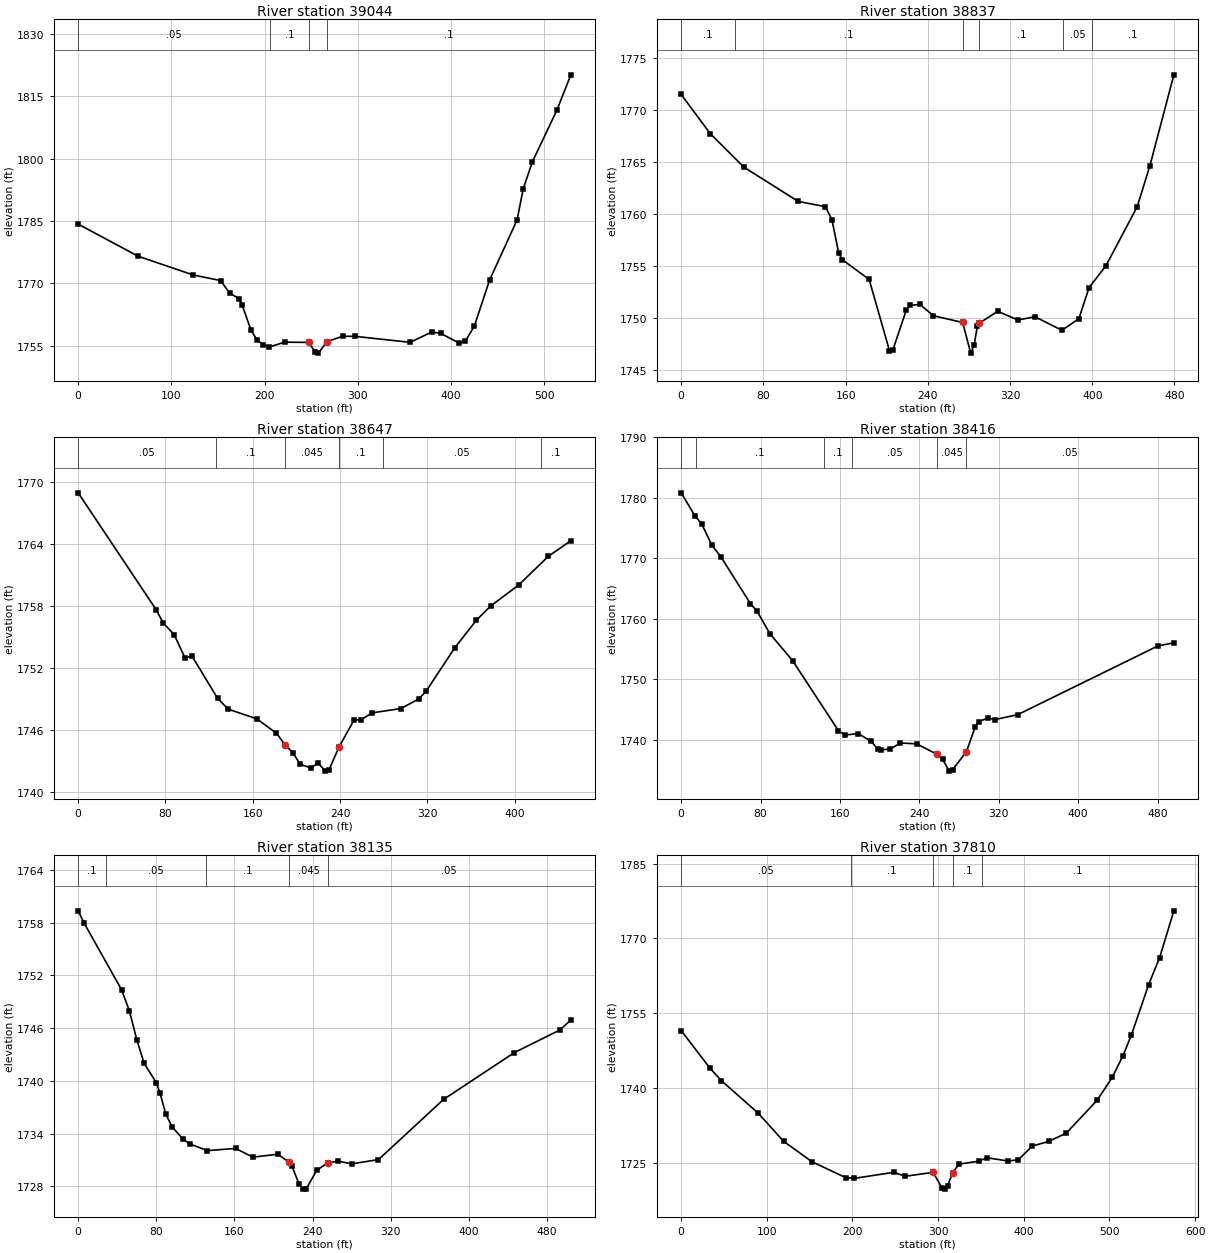
Type RM Length L Ch R = 1 ,39044   ,204.5,207.2,204.9
XS GIS Cut Line= 3
2099177.05724019296745.6187830422098799.45300853296745.618783042
2098648.41131586296748.223108545
#Sta/Elev= 30
       0 1784.22    64.2  1776.5   123.3 1771.99   152.8 1770.63   162.6  1767.6
   172.5 1766.29   175.8 1764.84   185.6 1758.62   192.2 1756.26   198.7 1755.22
   205.3 1754.67   221.7 1755.81  247.34 1755.75   254.5 1753.39   257.8 1753.17
  266.931755.948     284 1757.23   297.1 1757.21   356.2 1755.77   379.2 1758.22
     389 1757.93   408.7  1755.6   415.3 1755.99   425.1 1759.67   441.5 1770.75
     471 1785.23   477.6 1792.74   487.4 1799.21   513.7 1811.64   528.7 1820.15
#Mann= 4 ,-1 , 0
       0     .05       0  206.07      .1       0  247.34    .045       0
  266.93      .1       0
Bank Sta=247.34,266.93
XS Rating Curve= 0 ,0
Exp/Cntr=0.3,0.1

Type RM Length L Ch R = 1 ,38837   ,193.6,190.6,190.5
XS GIS Cut Line= 2
2099170.54675451 296578.952121632098692.68222469296541.191698462
#Sta/Elev= 30
       0 1771.46    28.3  1767.7      61 1764.48   113.8 1761.19   140.4 1760.68
   146.7 1759.42   153.3 1756.22   156.6  1755.6   182.9 1753.69   202.7 1746.84
     206 1746.92   219.1 1750.76   222.4 1751.19   232.3 1751.29   245.5  1750.2
  273.921749.556   281.7 1746.61     285 1747.36   288.2 1749.21  290.221749.491
     308 1750.63   327.7 1749.79   344.2 1750.11   370.5  1748.8     387 1749.93
   396.9 1752.91   413.3    1755   443.7 1760.67   456.1 1764.62   479.4 1773.35
#Mann= 6 ,-1 , 0
       0      .1       0   52.34      .1       0  273.92    .045       0
  290.22      .1       0  371.88     .05       0  400.05      .1       0
Bank Sta=273.92,290.22
XS Rating Curve= 0 ,0
Exp/Cntr=0.3,0.1

Type RM Length L Ch R = 1 ,38647   ,231.2,230.7,228.9
XS GIS Cut Line= 2
2099137.99465427296390.1500057882098688.77573645296345.879425049
#Sta/Elev= 30
       0 1768.96    71.4 1757.66      78 1756.36    87.9 1755.25    97.8    1753
   104.4 1753.14   127.7 1749.08   137.4 1748.03   163.7 1747.09   181.7 1745.69
  189.721744.559   196.7 1743.81   203.3 1742.71   213.2 1742.33   219.8 1742.83
   226.4 1742.03   229.7 1742.12  238.78 1744.32   252.7 1746.97   259.3    1747
   269.2 1747.67   295.6 1748.08   312.1 1749.02   318.7 1749.75     345 1753.96
   364.8 1756.63     378 1758.01   403.8 1760.06   430.7 1762.81   451.4 1764.33
#Mann= 6 ,-1 , 0
       0     .05       0  126.68      .1       0  189.72    .045       0
  238.78      .1       0  278.96     .05       0  424.38      .1       0
Bank Sta=189.72,238.78
XS Rating Curve= 0 ,0
Exp/Cntr=0.3,0.1

Type RM Length L Ch R = 1 ,38416   ,287.1,281.4,268.7
XS GIS Cut Line= 2
2099218.72382352296151.8689862942098722.62999943296133.639692038
#Sta/Elev= 30
       0 1780.84      14    1777    20.6 1775.72    30.7 1772.26    40.3 1770.18
    69.8 1762.51    76.4 1761.28    89.5 1757.52   112.2  1753.1   158.5  1741.5
     165 1740.78   178.2 1741.03   191.3 1739.77   197.9 1738.51   201.2 1738.34
   210.7 1738.46   220.8 1739.47   237.3 1739.33  257.631737.613   263.5 1736.75
   270.1 1734.82   273.4 1735.04  287.411738.047   296.2  1742.1   299.6 1743.01
   308.8 1743.58   316.1 1743.35     339 1744.15   480.2 1755.51   496.4 1756.05
#Mann= 6 ,-1 , 0
       0      .1       0   14.68      .1       0  143.77      .1       0
  172.31     .05       0  257.63    .045       0  287.41     .05       0
Bank Sta=257.63,287.41
XS Rating Curve= 0 ,0
Exp/Cntr=0.3,0.1

Type RM Length L Ch R = 1 ,38135   ,321,325,327
XS GIS Cut Line= 2
2099144.50513995295784.6814004632098686.17173901295995.618970707
#Sta/Elev= 30
       0 1759.35     5.9 1757.99    44.4 1750.38    52.3 1748.01    60.1 1744.66
    67.5 1742.01    79.9 1739.82    83.7 1738.65    89.8  1736.2    96.2 1734.77
   107.1 1733.41   114.3 1732.83   132.4 1732.07   161.2 1732.32   178.8 1731.33
   204.6 1731.66  216.231730.723     219 1730.29   226.3 1728.22   229.9 1727.69
   233.5 1727.72   244.3 1729.83  255.551730.682     266 1730.87   280.4 1730.57
   307.5 1731.05   374.3 1737.91   446.6 1743.22     493 1745.78   504.5 1746.92
#Mann= 5 ,-1 , 0
       0      .1       0   28.22     .05       0  131.29      .1       0
  216.23    .045       0  255.55     .05       0
Bank Sta=216.23,255.55
XS Rating Curve= 0 ,0
Exp/Cntr=0.3,0.1

Type RM Length L Ch R = 1 ,37810   ,364.1,363.4,362.4
XS GIS Cut Line= 2
 2099080.7031022295565.9315098822098509.08843178295629.733547628
#Sta/Elev= 30
       0 1751.51    33.7 1743.96    46.9 1741.48    89.8 1734.98   119.5 1729.33
   152.5 1725.24   192.1 1722.03     202 1721.89   248.3  1723.1   261.5 1722.31
  294.121723.088   304.4 1720.03   307.7 1719.73     311 1720.39  316.991723.001
   324.2 1724.75   347.3 1725.32   357.2 1726.01   381.7 1725.37   393.5 1725.61
     410 1728.38   429.2 1729.29   449.6 1730.96   485.7 1737.55   503.5 1742.21
   515.7 1746.45   525.6  1750.6   545.7  1760.7   558.6 1766.15   575.2 1775.52
#Mann= 5 ,-1 , 0
       0     .05       0  198.15      .1       0  294.12    .045       0
  316.99      .1       0  351.64      .1       0
Bank Sta=294.12,316.99
XS Rating Curve= 0 ,0
Exp/Cntr=0.3,0.1

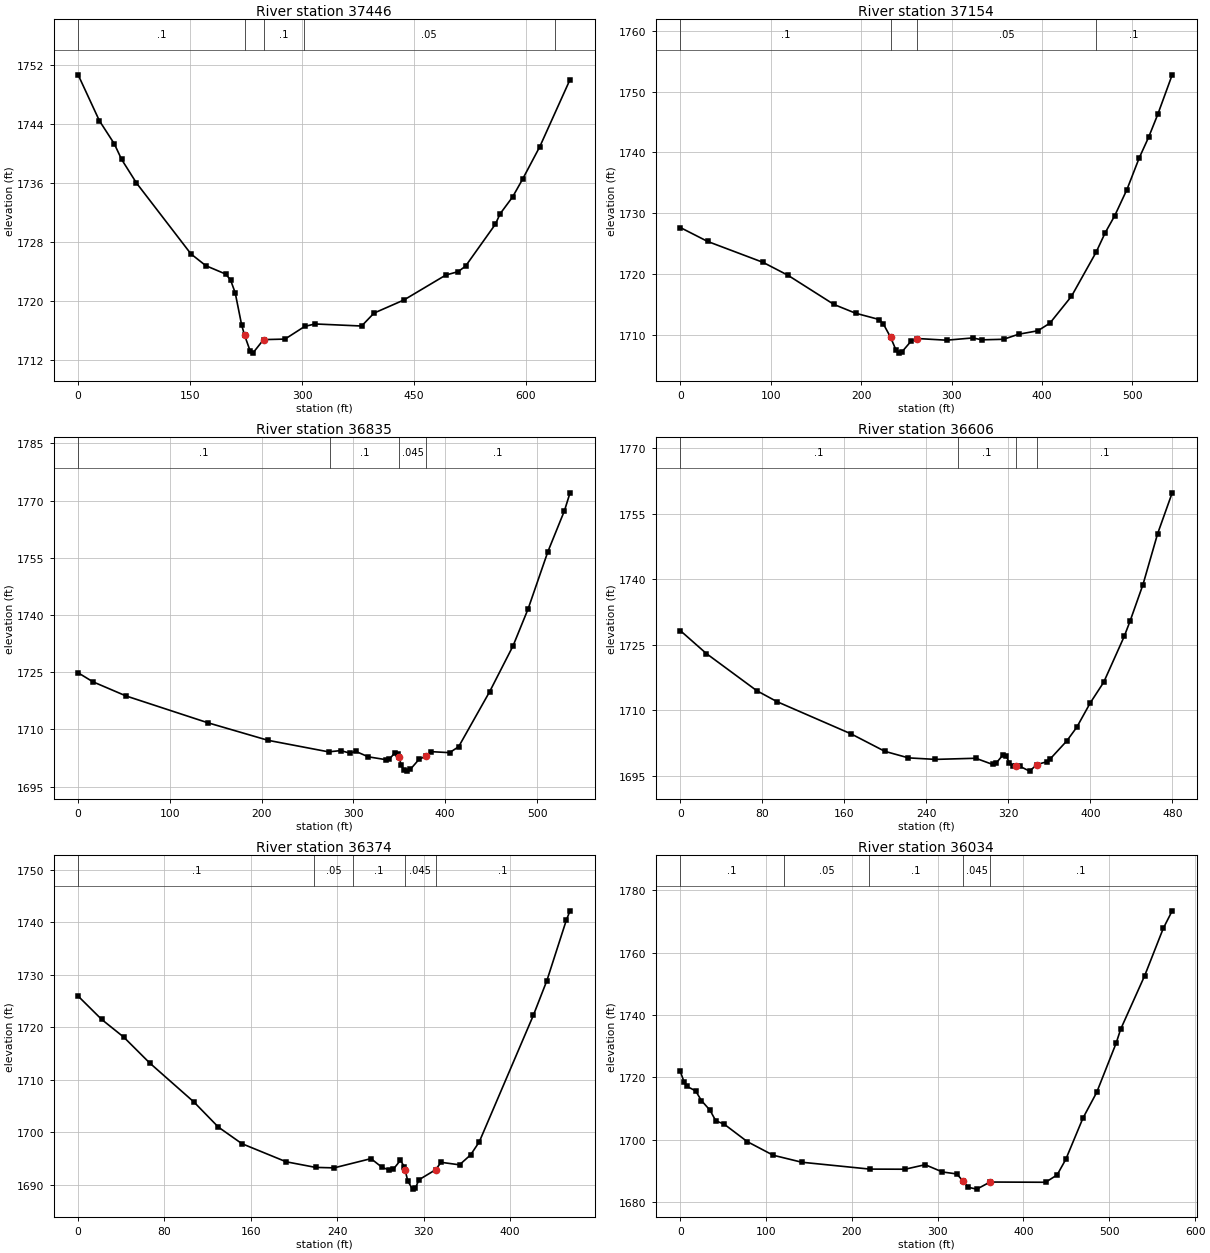
Type RM Length L Ch R = 1 ,37446   ,292.8,292.1,290
XS GIS Cut Line= 2
2099082.00493684 295228.691698792098429.66142526295323.744002134
#Sta/Elev= 30
       0 1750.63    28.5 1744.41    48.4  1741.3    58.3 1739.17    78.2 1735.98
   151.2 1726.38   171.1 1724.79   197.6 1723.66   204.2 1722.87   210.5 1721.11
   219.1 1716.77  223.021715.374   230.7 1713.19   234.1 1712.95  248.461714.779
   277.2 1714.85   303.7 1716.57   317.5  1716.9   379.9 1716.62   396.5 1718.37
   436.5 1720.14   492.7 1723.52   509.2 1723.98   519.2 1724.73     559 1730.38
   565.6 1731.83   582.2 1734.09   595.5 1736.48   618.7 1740.91   659.2 1749.99
#Mann= 5 ,-1 , 0
       0      .1       0  223.02    .045       0  248.46      .1       0
  302.19     .05       0  638.57      .1       0
Bank Sta=223.02,248.46
XS Rating Curve= 0 ,0
Exp/Cntr=0.3,0.1

Type RM Length L Ch R = 1 ,37154   ,314.8,319.6,324.5
XS GIS Cut Line= 2
2098977.83847854294930.5148017112098454.40087712295078.952168882
#Sta/Elev= 30
       0 1727.63    30.2 1725.34    91.6 1721.89   119.2 1719.76     170 1714.96
   193.9 1713.52   220.1 1712.48   224.6 1711.76  232.711709.531   238.7 1707.41
   241.6 1706.95     245 1707.13   255.2  1708.9  262.211709.354   294.5 1709.08
   323.4 1709.45   333.7 1709.14   357.6 1709.23   374.2 1710.06   395.5 1710.63
   408.8 1711.88   432.7 1716.31   459.9 1723.55   470.1  1726.8   480.5 1729.56
     494 1733.87   507.6 1739.08   518.1 1742.52   528.1 1746.24   544.1 1752.77
#Mann= 4 ,-1 , 0
       0      .1       0  232.71    .045       0  262.21     .05       0
   459.7      .1       0
Bank Sta=232.71,262.21
XS Rating Curve= 0 ,0
Exp/Cntr=0.3,0.1

Type RM Length L Ch R = 1 ,36835   ,228.4,228.1,226.5
XS GIS Cut Line= 2
2098977.83847854  294778.17094632098443.98423126294729.993877292
#Sta/Elev= 30
       0 1724.86      16 1722.51    52.2 1718.79   141.1 1711.78     207 1707.16
   272.9 1704.14   286.1 1704.47     296 1703.81   302.6 1704.26   316.1 1702.84
   335.5 1702.09   338.8 1702.14   345.4 1703.96   348.7 1703.53   349.51702.858
     352 1700.76   354.7 1699.42   358.6 1699.09   361.9 1699.54   371.7 1702.24
  379.141702.995   384.9 1704.19   404.7 1703.93   414.6 1705.48   448.4 1719.91
   473.9 1731.92   490.3  1741.6   511.8 1756.57   529.9 1767.33     536 1772.02
#Mann= 4 ,-1 , 0
       0      .1       0  274.78      .1       0   349.5    .045       0
  379.14      .1       0
Bank Sta=349.5,379.14
XS Rating Curve= 0 ,0
Exp/Cntr=0.3,0.1

Type RM Length L Ch R = 1 ,36606   ,230.2,232,236.9
XS GIS Cut Line= 2
 2098947.8903757294535.9834385512098468.72368312294511.243986711
#Sta/Elev= 30
       0 1728.24    25.4 1722.98    74.6 1714.46    94.3 1711.95   166.6 1704.56
   199.5 1700.56   222.5 1699.06   248.8 1698.71   288.2 1698.97   304.6 1697.56
   307.9  1697.8   314.5 1699.67   317.7 1699.51     321 1697.99   324.3 1697.31
   327.51697.174   330.9 1697.16   340.7 1696.02  347.861697.525   357.2 1698.15
   360.7 1698.79   376.9 1702.92   386.7 1706.07   399.9 1711.67     413  1716.4
     433  1726.9   438.8 1730.47   451.3 1738.79   465.6 1750.46   479.8 1759.82
#Mann= 4 ,-1 , 0
       0      .1       0  270.88      .1       0   327.5    .045       0
  347.86      .1       0
Bank Sta=327.5,347.86
XS Rating Curve= 0 ,0
Exp/Cntr=0.3,0.1

Type RM Length L Ch R = 1 ,36374   ,343,339.9,327.5
XS GIS Cut Line= 2
2098920.54659835294378.4312602132098483.04681718294250.827184707
#Sta/Elev= 30
       0 1725.94    21.8  1721.5    42.3 1718.12    66.2 1713.22   107.3 1705.76
   129.9 1700.99   151.7 1697.83   192.7 1694.38     220 1693.31   237.1 1693.22
   271.3 1694.98   281.6 1693.31   288.4  1692.8   291.8 1692.92   298.6 1694.66
   302.1 1693.45  302.941692.759   305.5 1690.66   309.8 1689.17   312.5 1689.38
   315.7 1690.95  331.141692.863   336.2 1694.28   353.3  1693.8   363.6  1695.7
   371.6 1698.17   421.7 1722.28   434.2 1728.87   452.4  1740.5   455.7 1742.19
#Mann= 5 ,-1 , 0
       0      .1       0  218.84     .05       0  254.79      .1       0
  302.94    .045       0  331.14      .1       0
Bank Sta=302.94,331.14
XS Rating Curve= 0 ,0
Exp/Cntr=0.3,0.1

Type RM Length L Ch R = 1 ,36034   ,324.1,333.6,341.3
XS GIS Cut Line= 3
 2098933.5675697293899.2645676292098656.22363618293953.952122301
2098371.06738237 294009.94183971
#Sta/Elev= 30
       0 1721.94     4.5 1718.52     7.9 1717.14    17.9  1715.7    24.6 1712.61
    34.6 1709.52    41.3 1706.15    51.3 1705.01    78.1 1699.44   108.2 1695.09
   141.6 1692.84   220.8 1690.64     262  1690.6   285.4 1692.05   305.5 1689.72
   322.2 1689.09  329.461686.836   335.6  1684.8   345.6 1684.22  361.051686.495
   425.8 1686.42   439.2 1688.78   449.3 1693.77   469.3 1706.99   485.3 1715.22
     508 1731.03   513.2 1735.45   541.2 1752.61   562.9  1767.8   573.3 1773.42
#Mann= 5 ,-1 , 0
       0      .1       0  121.02     .05       0  220.41      .1       0
  329.46    .045       0  361.05      .1       0
Bank Sta=329.46,361.05
XS Rating Curve= 0 ,0
Exp/Cntr=0.3,0.1