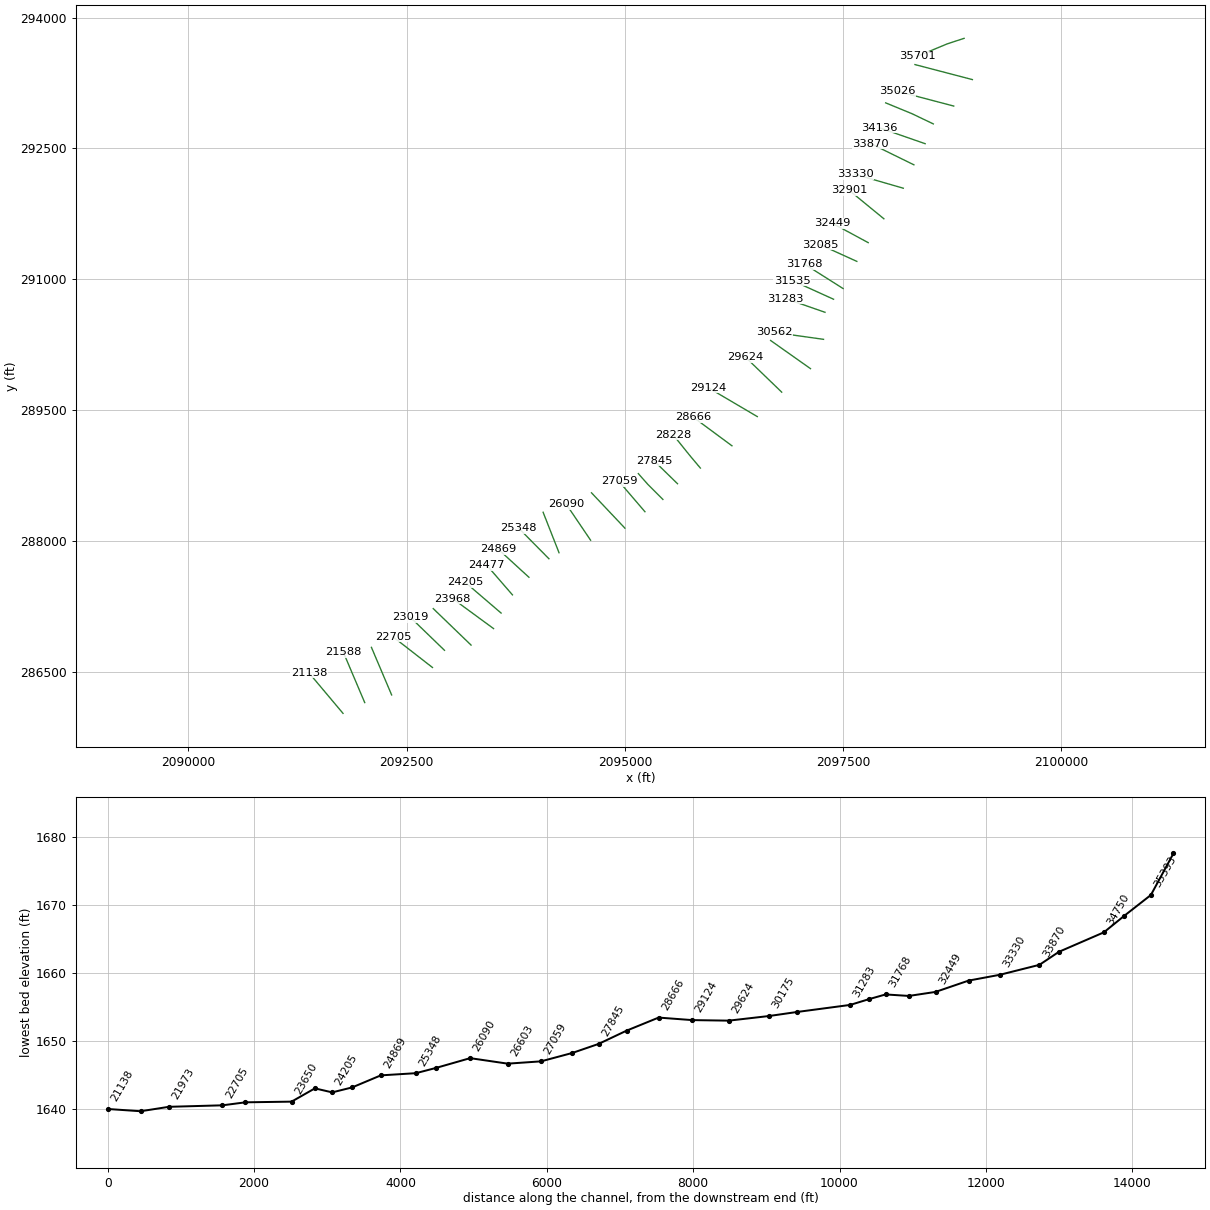
HEC-RAS study MILLCK1.prj: MILLCK1

--- MILLCK1.g01 (geometry) --- (continued)

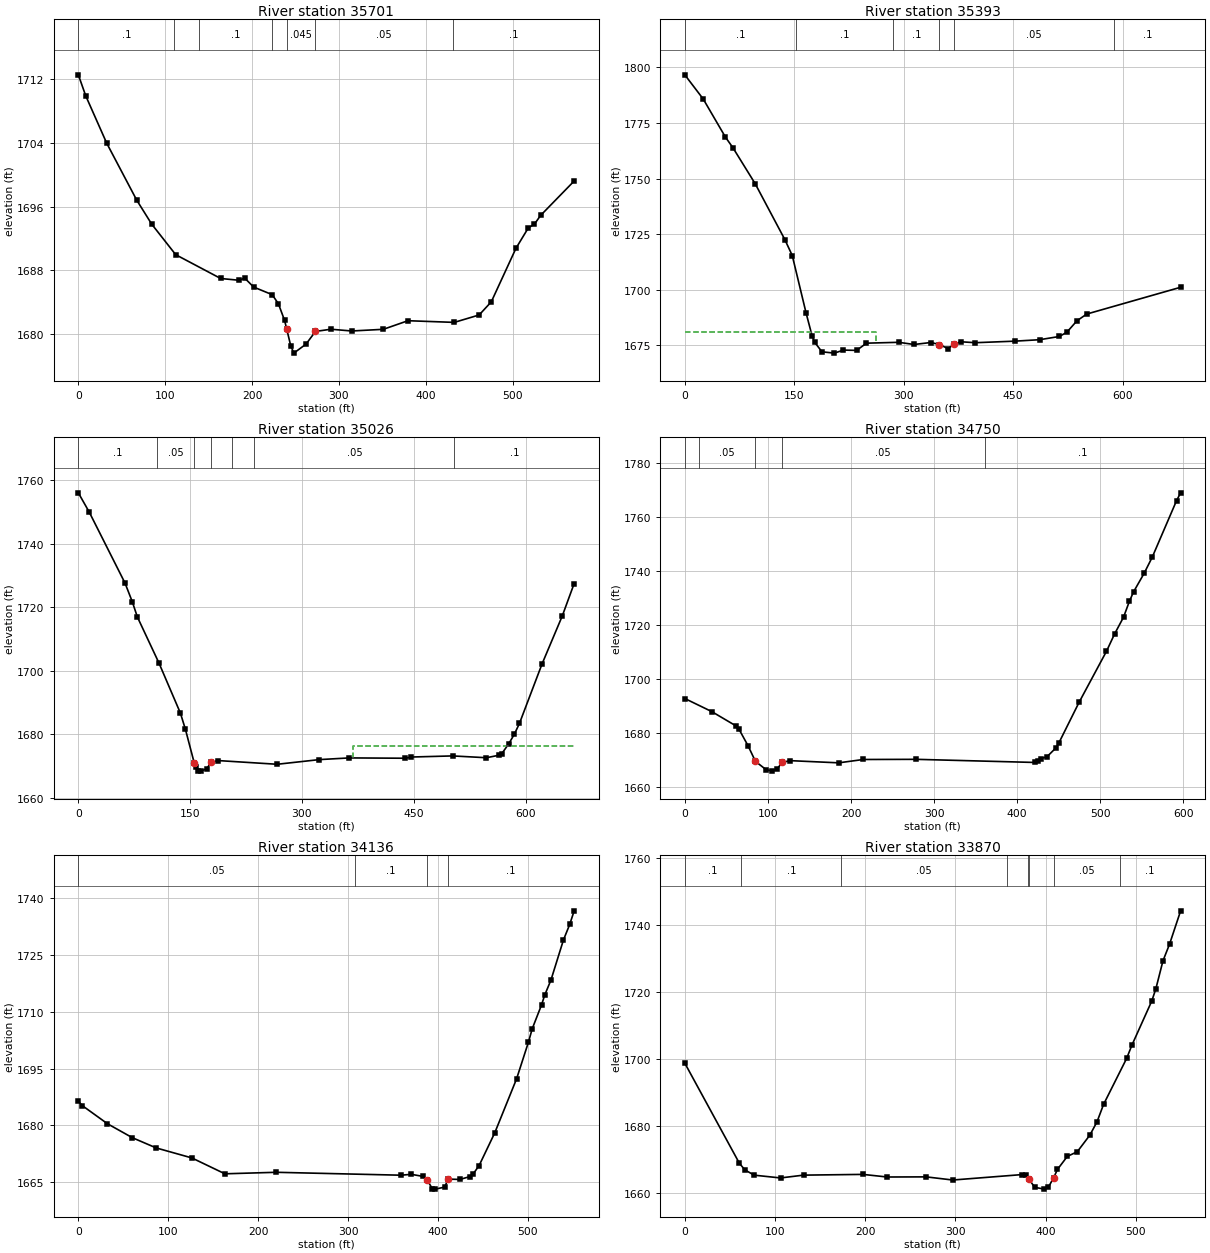
Type RM Length L Ch R = 1 ,35701   ,314.2,308.2,295.6
XS GIS Cut Line= 3
 2098887.9944981293761.2438462972098693.98405936293697.441808552
 2098355.4424136293556.816761717
#Sta/Elev= 30
       0 1712.54     8.5 1709.91    32.7 1703.95    67.2 1696.81    84.5 1693.79
   112.1 1689.96   163.9 1686.97   184.8 1686.75   191.6 1687.01   201.9 1685.89
   223.2 1684.94   230.3  1683.8   237.4 1681.72  240.031680.567   244.5 1678.53
   248.1  1677.6   262.2 1678.74  272.971680.322   290.7  1680.6   314.7 1680.38
   351.1 1680.59   379.5 1681.67   432.8 1681.46   461.4 1682.39   475.4 1684.04
   503.8 1690.76     518 1693.32   525.1  1693.8   532.2 1694.89   570.8 1699.21
#Mann= 7 ,-1 , 0
       0      .1       0  110.49     .05       0  138.81      .1       0
  223.19     .05       0  240.03    .045       0  272.97     .05       0
  430.76      .1       0
Bank Sta=240.03,272.97
XS Rating Curve= 0 ,0
Exp/Cntr=0.3,0.1

Type RM Length L Ch R = 1 ,35393   ,365.6,366.5,365.2
XS GIS Cut Line= 2
2098983.04680145293288.5876393772098325.49463886293460.462623715
#Sta/Elev= 30
       0  1796.7    25.2 1785.84    55.7 1768.67    65.9 1763.93    96.5  1747.7
   137.1  1722.6   147.3 1715.39   166.4 1689.33   174.4 1679.36   177.8 1676.44
     188 1672.09   204.9 1671.49   217.5 1672.86   235.5 1672.72     249 1675.97
   293.1 1676.36   314.3 1675.38   337.2 1676.27  349.031675.371   360.9 1673.51
   369.11675.505   377.9 1676.61   398.2 1676.18   452.5 1676.88   486.5 1677.53
   513.5 1678.99   523.7 1680.91   537.4    1686   550.8 1689.06   679.6 1701.12
#Mann= 6 ,-1 , 0
       0      .1       0  152.78      .1       0   285.9      .1       0
  349.03    .045       0   369.1     .05       0  588.17      .1       0
#XS Ineff= 2 , 0
          261.46 1680.86
Permanent Ineff=
       F       F
Bank Sta=349.03,369.1
XS Rating Curve= 0 ,0
Exp/Cntr=0.3,0.1

Type RM Length L Ch R = 1 ,35026   ,274,276.7,273.5
XS GIS Cut Line= 2
 2098769.5049057292985.2020912922098126.27587718293154.473078206
#Sta/Elev= 30
       0 1756.05    14.7 1749.95    62.6 1727.64    72.4 1721.74    79.2 1716.95
   108.2 1702.43   136.9 1686.69   143.7 1681.53   155.51670.964   157.2 1669.68
   160.6 1668.57   164.6 1668.41   172.7 1669.23  177.54 1671.17   187.8 1671.73
   266.7 1670.57   323.5 1672.04   363.4 1672.57   438.8 1672.47   446.6 1672.85
   502.1  1673.2   547.4 1672.63   564.8 1673.44   568.2 1673.96   577.4 1677.04
   584.7 1679.96   591.7 1683.43     622 1702.15   649.2  1717.3   665.1 1727.49
#Mann= 7 ,-1 , 0
       0      .1       0   105.9     .05       0   155.5    .045       0
  177.54     .05       0   205.7      .1       0  236.17     .05       0
  504.42      .1       0
#XS Ineff= 2 , 0
                          368.81         1676.33
Permanent Ineff=
       F       F
Bank Sta=155.5,177.54
XS Rating Curve= 0 ,0
Exp/Cntr=0.3,0.1

Type RM Length L Ch R = 1 ,34750   ,608.9,613.9,606.1
XS GIS Cut Line= 3
2098535.13004637292780.7750067112098290.33821312292897.962764457
2097989.55699053293021.660679787
#Sta/Elev= 30
       0  1692.9    32.4 1688.06    61.9  1682.7    65.1 1681.59    76.1  1675.4
   85.021669.607    97.9 1666.52   105.2    1666   111.1 1666.64   116.71669.249
     127 1669.88   185.2 1669.07   214.7 1670.31   278.5 1670.37   421.4 1669.21
     425  1669.6   428.5 1670.67   435.6 1671.27   446.3 1674.53   449.8 1676.26
   474.4 1691.48   507.3 1710.35   517.2 1716.85   527.9 1723.02   534.9 1728.85
   539.9 1732.37   552.7 1739.28   562.6 1745.36   591.7  1766.2   596.6 1769.09
#Mann= 5 ,-1 , 0
       0      .1       0   16.99     .05       0   85.02    .045       0
   116.7     .05       0  360.96      .1       0
Bank Sta=85.02,116.7
XS Rating Curve= 0 ,0
Exp/Cntr=0.3,0.1

Type RM Length L Ch R = 1 ,34136   ,258.8,265.9,251.8
XS GIS Cut Line= 2
2098441.37990576292554.2124677152097920.54662985292735.202263206
#Sta/Elev= 30
       0 1686.34     4.6 1685.18    32.4 1680.42    60.2 1676.72    86.7 1674.02
   126.2 1671.39     163 1667.19     220 1667.59   358.9 1666.82   370.3 1667.05
   383.2 1666.51  387.981665.528   393.6 1663.29   397.1 1663.14   407.5 1663.69
  411.09 1665.79   424.4  1665.7   435.3 1666.45   438.8 1667.05   445.7 1669.37
   463.1 1678.02   487.4 1692.31   500.5 1701.95   504.8 1705.55   515.2 1711.88
   518.7 1714.46   525.6 1718.41   539.5 1729.01   546.5 1733.13   551.4  1736.7
#Mann= 4 ,-1 , 0
       0     .05       0  307.94      .1       0  387.98    .045       0
  411.09      .1       0
Bank Sta=387.98,411.09
XS Rating Curve= 0 ,0
Exp/Cntr=0.3,0.1

Type RM Length L Ch R = 1 ,33870   ,527.5,540,530.5
XS GIS Cut Line= 2
2098312.47366753292312.0249599672097818.98416895292554.212467715
#Sta/Elev= 30
       0 1698.86    60.5 1668.96    66.6 1666.98    76.9  1665.4   106.1 1664.57
   131.7 1665.41   197.5 1665.63   224.4 1664.85   267.6 1664.89   297.1 1663.95
   373.3 1665.56     378 1665.34   381.21664.377   387.8 1661.79   398.5 1661.23
   403.1 1661.82  409.011664.665   413.1  1667.1   424.1 1671.01   435.1 1672.39
   449.1 1677.37     457 1681.33   464.3 1686.55   489.9  1700.3   495.6 1704.18
   517.7 1717.41   522.3 1721.12   530.1  1729.4   537.4 1734.38   549.7 1744.35
#Mann= 8 ,-1 , 0
       0      .1       0   62.81      .1       0  173.62     .05       0
  357.14      .1       0  380.52     .05       0   381.2    .045       0
  409.01     .05       0  482.12      .1       0
Bank Sta=381.2,409.01
XS Rating Curve= 0 ,0
Exp/Cntr=0.3,0.1

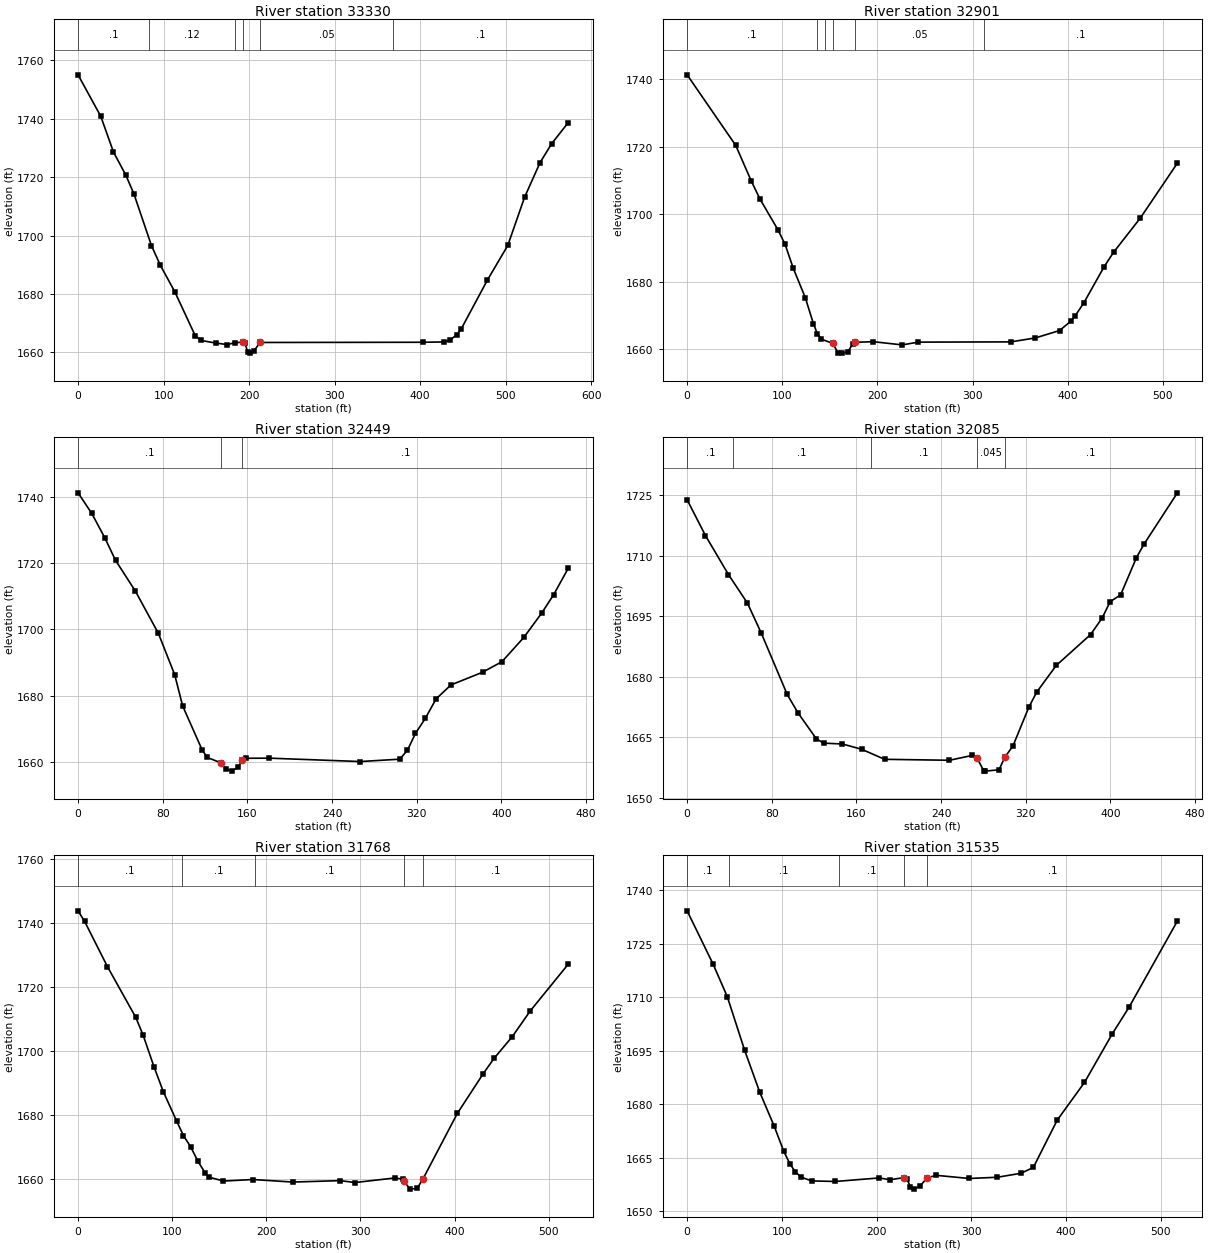
Type RM Length L Ch R = 1 ,33330   ,421.3,429,409.6
XS GIS Cut Line= 2
2098191.38007769292043.7958376262097640.59869894292202.650178716
#Sta/Elev= 30
       0 1755.09    26.6 1740.85    41.4 1728.65    55.7 1720.82    65.3 1714.32
    85.8 1696.61    96.1 1689.92   113.1 1680.79     137 1665.74   143.9 1664.11
   160.9 1663.23   174.6 1662.69   183.5 1663.36  193.26 1663.51   195.1 1663.21
   198.5 1660.01   201.5 1659.77   205.3  1660.4  212.91 1663.42   403.4 1663.49
   427.3  1663.6   434.7 1664.16   442.7 1666.08   447.8 1667.97   478.5 1684.75
   502.4 1696.65   522.1  1713.2     540 1724.94   553.6 1731.47   573.2 1738.76
#Mann= 6 ,-1 , 0
       0      .1       0   83.45     .12       0   183.5     .05       0
  193.26    .045       0  212.91     .05       0  368.09      .1       0
Bank Sta=193.26,212.91
XS Rating Curve= 0 ,0
Exp/Cntr=0.3,0.1

Type RM Length L Ch R = 1 ,32901   ,443,451.4,446.2
XS GIS Cut Line= 2
2097968.72369885291693.5353832992097570.28617552292020.358548552
#Sta/Elev= 30
       0 1741.36    51.1 1720.44    67.4  1709.9    76.7 1704.49    95.4 1695.46
     103  1691.1   111.5 1684.07   124.2 1675.34   132.7 1667.66   136.9  1664.6
   141.2 1663.03   153.11661.786   158.5 1659.03   162.4 1658.91   168.9 1659.25
   174.1 1661.72  176.131662.107   195.6  1662.3     226 1661.35     243 1662.17
   340.2 1662.24   366.1 1663.42   391.5 1665.61   403.1 1668.34   407.8 1669.94
   417.1 1673.88   438.2 1684.48   448.2 1688.79   476.4 1698.96   515.3 1715.21
#Mann= 6 ,-1 , 0
       0      .1       0  136.26     .12       0  145.11     .05       0
   153.1    .045       0  176.13     .05       0  312.29      .1       0
Bank Sta=153.1,176.13
XS Rating Curve= 0 ,0
Exp/Cntr=0.3,0.1

Type RM Length L Ch R = 1 ,32449   ,354.9,363.9,359.6
XS GIS Cut Line= 2
2097789.03639418291420.0979380462097381.48405969291640.149991378
#Sta/Elev= 30
       0 1741.13      13  1734.9    25.4 1727.49    35.4 1720.79    54.1 1711.54
    75.9 1698.77    91.3 1686.32    98.8 1676.91   117.4 1663.52   122.2 1661.36
  135.141659.728   139.8 1657.95     145 1657.25     151 1658.36  155.211660.605
   158.5 1661.12   180.8 1661.16   266.6 1660.14   303.9 1660.85   311.1 1663.49
   318.8 1668.63   328.1 1673.16   338.3 1679.03   352.3 1683.23   382.2 1687.06
   400.5 1690.24   421.2 1697.56   438.1 1704.92   449.3 1710.41   463.2 1718.44
#Mann= 3 ,-1 , 0
       0      .1       0  135.14    .045       0  155.21      .1       0
Bank Sta=135.14,155.21
XS Rating Curve= 0 ,0
Exp/Cntr=0.3,0.1

Type RM Length L Ch R = 1 ,32085   ,318.6,317.8,314.5
XS GIS Cut Line= 2
2097658.82799318291205.254207626 2097236.9528527291396.660648957
#Sta/Elev= 30
       0 1723.93    17.3 1715.07      39 1705.41      57 1698.31    70.1 1690.85
    94.5  1675.7   104.8 1671.08   122.1 1664.67     129  1663.6   146.7 1663.39
     165 1662.07   186.6 1659.59   247.9 1659.35   269.5 1660.56  274.041659.889
   280.3 1656.72   281.7 1656.66   294.7 1656.99  300.141660.054     308 1662.97
   322.9 1672.51   330.3 1676.24   348.8 1682.86   381.2 1690.51   392.3 1694.67
   399.7 1698.68   409.6 1700.34   424.6  1709.6   431.6 1712.88   463.3 1725.66
#Mann= 5 ,-1 , 0
       0      .1       0   43.71      .1       0  173.39      .1       0
  274.04    .045       0  300.14      .1       0
Bank Sta=274.04,300.14
XS Rating Curve= 0 ,0
Exp/Cntr=0.3,0.1

Type RM Length L Ch R = 1 ,31768   ,230,232.6,231.5
XS GIS Cut Line= 2
2097501.27581486290894.056339204 2097061.1717082291172.702107385
#Sta/Elev= 30
       0 1743.75       7 1740.44    31.2 1726.34    61.3  1710.5    69.1 1704.98
    80.7 1695.06    90.6 1687.29   104.9 1678.02     112 1673.57   119.6 1670.11
   127.3  1665.6   135.1 1661.89     139 1660.63   154.5  1659.4   185.7 1659.88
   228.3 1659.09   278.5 1659.53   294.3 1658.94     337 1660.38   344.8 1659.98
  346.65  1659.3   352.5 1656.88   360.3 1657.11  366.681660.172     403 1680.53
   430.6 1692.97   441.9 1697.66   461.3 1704.46   480.4 1712.49   520.9 1727.13
#Mann= 5 ,-1 , 0
       0      .1       0  110.63      .1       0  187.56      .1       0
  346.65    .045       0  366.68      .1       0
Bank Sta=346.65,366.68
XS Rating Curve= 0 ,0
Exp/Cntr=0.3,0.1

Type RM Length L Ch R = 1 ,31535   ,249.4,251.9,249.2
XS GIS Cut Line= 2
2097391.90103361290771.6605866252096920.54666135290985.202154294
#Sta/Elev= 30
       0 1734.24    27.5 1719.23    42.4 1710.14    60.7 1695.12    76.6 1683.38
    91.7 1673.96   101.8  1666.9   108.4 1663.31   114.2 1660.98   120.5  1659.5
   131.6 1658.47   156.5 1658.32   202.9 1659.31   214.1  1658.8  229.261659.416
   232.1 1658.89   235.7 1656.86   239.4 1656.17   245.6 1656.98  253.521659.372
     263 1660.04   297.7 1659.16   327.4  1659.5   352.2 1660.61   365.4 1662.24
   390.6 1675.51   419.4  1686.1   448.9  1699.8   466.3 1707.13   517.5  1731.4
#Mann= 5 ,-1 , 0
       0      .1       0   44.34      .1       0  160.42      .1       0
  229.26    .045       0  253.52      .1       0
Bank Sta=229.26,253.52
XS Rating Curve= 0 ,0
Exp/Cntr=0.3,0.1

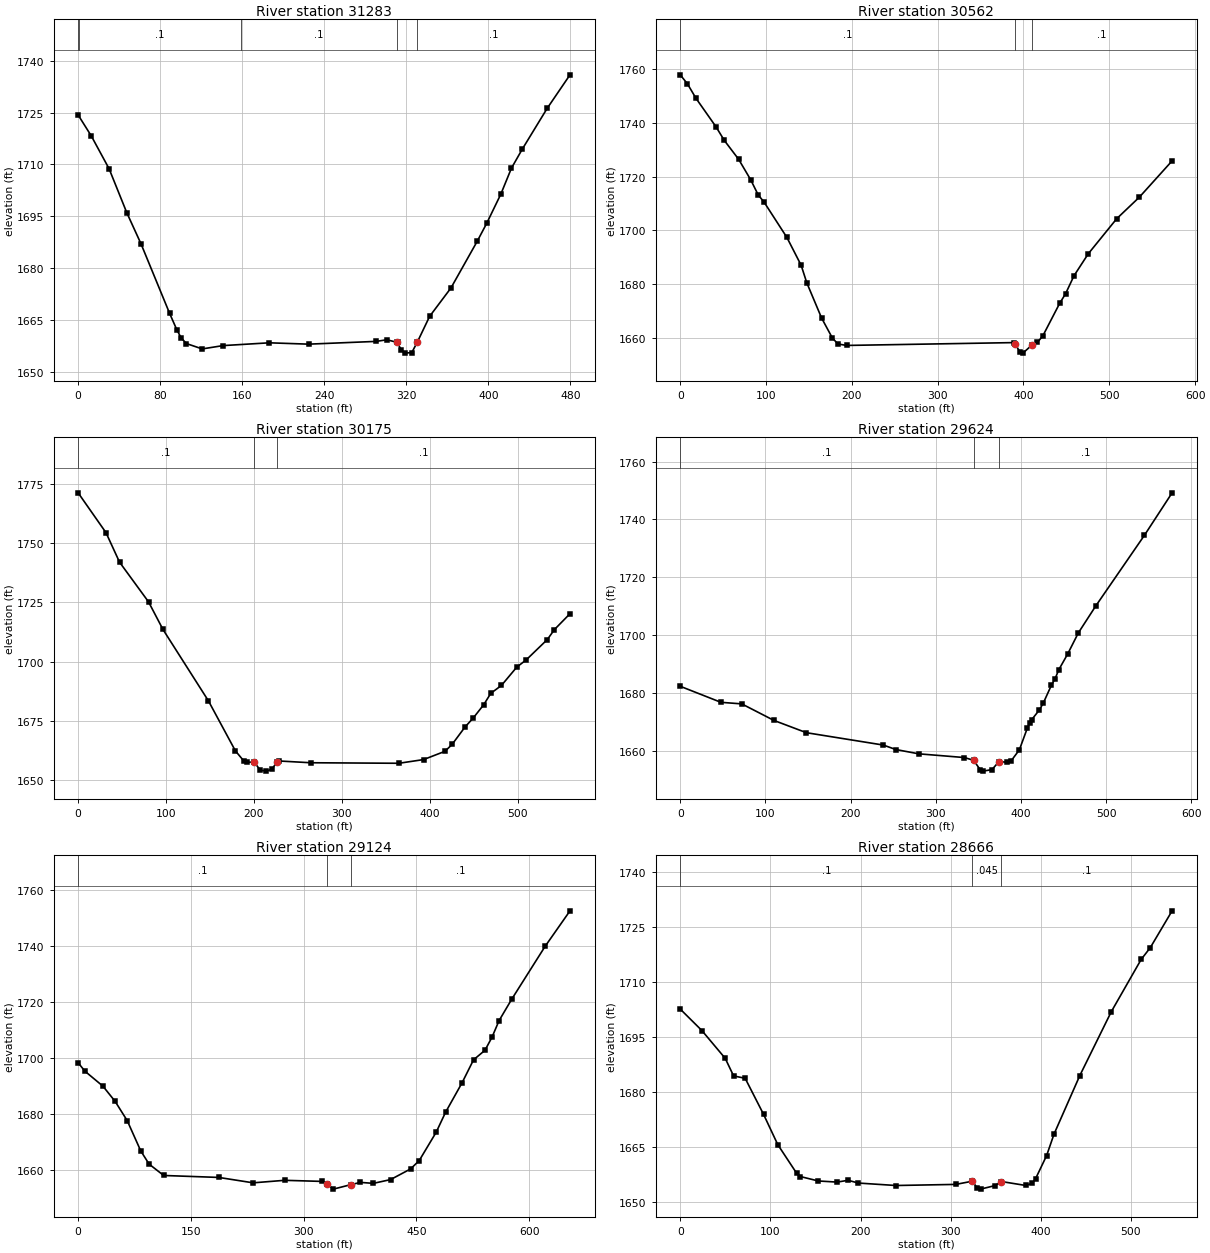
Type RM Length L Ch R = 1 ,31283   ,706.5,721.2,710.8
XS GIS Cut Line= 2
2097294.24473286290621.9210567182096841.11965486290779.472906962
#Sta/Elev= 30
       0 1724.34    12.8 1718.28    30.2 1708.75    47.5 1695.99    61.4 1686.95
    89.2 1666.87    96.2 1662.14   100.4 1659.79   105.6 1658.11     121 1656.56
   141.3 1657.52   186.5 1658.33   224.7 1657.94   290.7 1658.74   301.1 1659.21
  310.811658.487   311.5 1658.44     315 1656.24   318.5 1655.34   325.4  1655.5
   330.91658.591   342.8 1665.99   363.6 1674.22   389.1 1687.69   398.4 1692.91
   412.3 1701.44   422.6 1708.93   433.1 1714.41   457.4 1726.24   479.7 1735.97
#Mann= 5 ,-1 , 0
       0      .1       0     .63      .1       0  158.81      .1       0
  310.81    .045       0   330.9      .1       0
Bank Sta=310.81,330.9
XS Rating Curve= 0 ,0
Exp/Cntr=0.3,0.1

Type RM Length L Ch R = 1 ,30562   ,389.2,386.9,372.9
XS GIS Cut Line= 2
2097277.31760135290312.025022954 2096709.6090911290391.452029467
#Sta/Elev= 30
       0 1757.84     8.4 1754.48    18.3 1749.13    41.6 1738.54    51.4 1733.42
      68 1726.44    82.1  1718.8    90.8  1713.2    97.8 1710.44   124.3 1697.34
   140.9 1686.99   147.5 1680.45   164.8 1667.32   177.3 1659.93   183.8 1657.71
   193.9 1657.17   389.3 1658.23  390.291657.767   395.9 1654.68   399.3 1654.31
  410.351657.456   416.3 1658.35   422.5  1660.7   442.3 1672.91     449 1676.37
   458.9 1683.11   475.5 1691.27   508.6  1704.3   535.1 1712.35   573.2 1725.83
#Mann= 3 ,-1 , 0
       0      .1       0  390.29    .045       0  410.35      .1       0
Bank Sta=390.29,410.35
XS Rating Curve= 0 ,0
Exp/Cntr=0.3,0.1

Type RM Length L Ch R = 1 ,30175   ,543.3,551.2,540.2
XS GIS Cut Line= 2
2097127.57807145289976.0877027062096670.54683328290299.004379705
#Sta/Elev= 30
       0 1771.34    31.7  1754.5    47.1 1742.04    80.1 1725.25    96.5  1713.6
   148.2 1683.43   178.9 1662.29   188.3 1658.09   192.4 1657.44  200.321657.534
   207.2 1654.12   214.2 1653.71   220.5 1654.56   225.81657.362   228.5    1658
   264.7 1657.25   364.9 1657.03     393 1658.59   417.3 1662.08   425.4 1664.97
   440.2 1672.37   449.5 1676.16   461.4 1681.76   469.5  1686.6   481.6 1689.93
   499.1 1697.69   509.7  1700.7   533.8 1709.33   541.9 1713.55   559.6 1720.25
#Mann= 3 ,-1 , 0
       0      .1       0  200.32    .045       0   225.8      .1       0
Bank Sta=200.32,225.8
XS Rating Curve= 0 ,0
Exp/Cntr=0.3,0.1

Type RM Length L Ch R = 1 ,29624   ,495.2,500,501.9
XS GIS Cut Line= 2
2096798.15090877289706.5564176292096382.78625393290107.597938374
#Sta/Elev= 30
       0 1682.35    47.8 1676.81    72.2 1676.27     110 1670.55   148.1 1666.31
   238.4 1662.04     253  1660.5     280 1659.01   333.6 1657.72  344.461656.769
   352.1 1653.51   355.6 1653.03     366 1653.57  373.981656.275   383.9 1656.11
   388.6 1656.65   398.1 1660.39   407.5 1667.94   410.1 1669.51   412.4 1670.76
   421.7 1674.21   426.4 1676.69   435.6 1682.65     440 1684.97   444.5 1688.14
   454.8 1693.51   467.3 1700.79   487.8 1710.12   544.9 1734.53   577.4 1749.21
#Mann= 3 ,-1 , 0
       0      .1       0  344.46    .045       0  373.98      .1       0
Bank Sta=344.46,373.98
XS Rating Curve= 0 ,0
Exp/Cntr=0.3,0.1

Type RM Length L Ch R = 1 ,29124   ,456.4,458.3,449
XS GIS Cut Line= 2
2096518.20297787289426.6084867122095954.40095586289758.639646798
#Sta/Elev= 30
       0 1698.29       9 1695.27      33 1689.91    49.2 1684.48    65.3 1677.59
    83.3 1666.77    94.4 1662.06   113.8 1657.99   187.1 1657.29   232.8 1655.36
   274.7 1656.26   324.2 1655.87  330.721655.096   339.4 1653.11  363.14 1654.73
   375.6 1655.52   392.7 1655.17   415.6 1656.52   442.2 1660.32   453.7  1663.3
   476.3 1673.45   488.8  1680.6   510.8 1691.16     526 1699.34   541.2 1702.74
   550.6 1707.44   559.9 1713.32   576.9 1721.05   621.2 1739.89   654.3 1752.59
#Mann= 3 ,-1 , 0
       0      .1       0  330.72    .045       0  363.14      .1       0
Bank Sta=330.72,363.14
XS Rating Curve= 0 ,0
Exp/Cntr=0.3,0.1

Type RM Length L Ch R = 1 ,28666   ,438.2,437.9,427.3
XS GIS Cut Line= 2
2096227.83840111289091.9730011222095789.03645718289416.191840872
#Sta/Elev= 30
       0 1702.66      24  1696.8    49.9  1689.2    59.2  1684.4      72 1683.76
    92.4 1673.92   108.2 1665.63   129.1 1657.82   133.2 1656.92   153.1 1655.71
     174  1655.4   186.2 1655.89   197.6 1655.14   239.2 1654.47   305.6 1654.77
  324.081655.647     329 1653.91   333.1 1653.48   349.4 1654.46   356.1 1655.56
     383 1654.49   390.2 1655.03   394.2 1656.35   406.4 1662.64   414.6  1668.5
   443.2 1684.49   478.1 1701.93   511.3 1716.23   521.4 1719.44   545.6  1729.5
#Mann= 3 ,-1 , 0
       0      .1       0  324.08    .045       0   356.1      .1       0
Bank Sta=324.08,356.1
XS Rating Curve= 0 ,0
Exp/Cntr=0.3,0.1

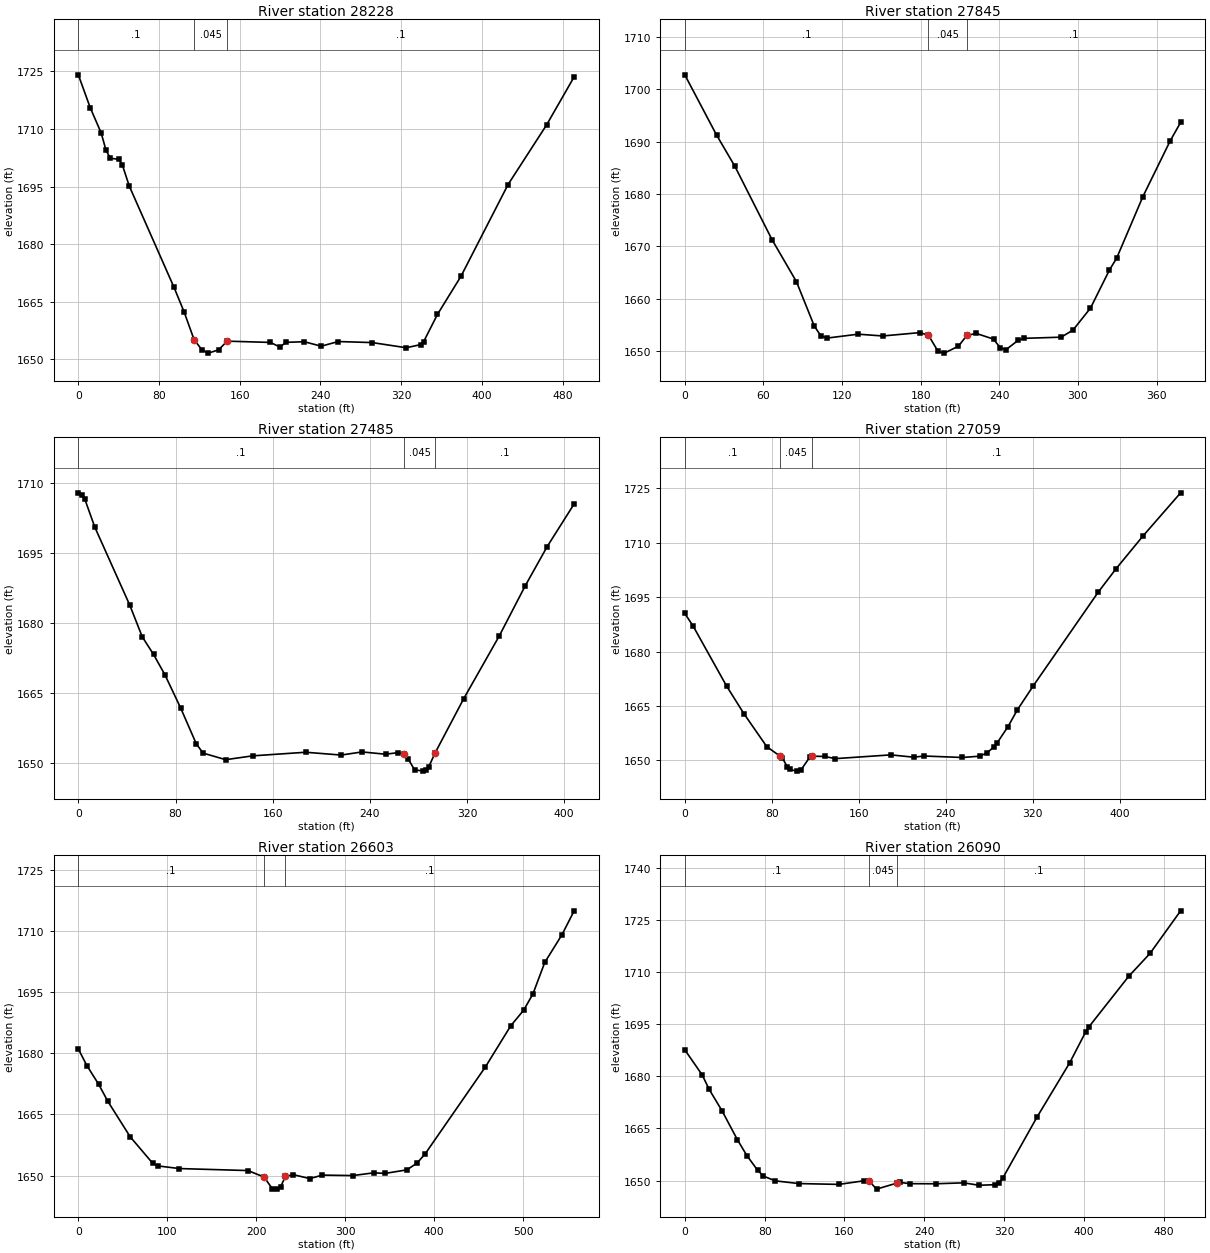
Type RM Length L Ch R = 1 ,28228   ,378.5,382.6,375.6
XS GIS Cut Line= 3
2095865.85913819288836.7648501252095753.88003144288969.577248544
2095554.66126978289216.973079205
#Sta/Elev= 30
       0 1724.12    11.8 1715.54    22.6 1708.99    27.4 1704.48    31.7 1702.35
    40.3 1702.11    43.6 1700.64    50.5 1695.11    94.8 1668.73   104.7 1662.39
  114.72 1655.08   122.7 1652.35   128.8 1651.56     139 1652.41   147.51654.683
   190.4 1654.35   199.6 1653.16   206.1 1654.38   223.9 1654.53   240.7 1653.37
   257.6 1654.58   291.3 1654.31     325 1652.96   339.6  1653.8   342.1 1654.49
   355.9 1661.64   379.3 1671.63   425.9 1695.52     464 1711.03   491.4  1723.6
#Mann= 3 ,-1 , 0
       0      .1       0  114.72    .045       0   147.5      .1       0
Bank Sta=114.72,147.5
XS Rating Curve= 0 ,0
Exp/Cntr=0.3,0.1

Type RM Length L Ch R = 1 ,27845   ,352.1,359.8,320.2
XS GIS Cut Line= 2
2095604.14050153288657.0772173852095333.30705369 288921.40017955
#Sta/Elev= 30
       0  1702.8    24.2 1691.31    38.3 1685.28    66.6 1671.28    85.2 1663.27
    98.8  1654.8   103.7 1652.96   108.4 1652.48   132.3 1653.23   151.1 1652.89
   179.3 1653.53  185.961653.027   193.3 1649.94     198 1649.61   208.8 1650.93
  215.321653.005   222.5 1653.37   235.6 1652.29   240.6 1650.67     245 1650.24
   254.6  1652.1   259.2 1652.44   287.3 1652.66   296.3 1654.03   309.6 1658.21
   324.1 1665.51   329.6 1667.77   349.6 1679.53   370.5 1690.21   378.4 1693.71
#Mann= 3 ,-1 , 0
       0      .1       0  185.96    .045       0  215.32      .1       0
Bank Sta=185.96,215.32
XS Rating Curve= 0 ,0
Exp/Cntr=0.3,0.1

Type RM Length L Ch R = 1 ,27485   ,414.2,426.1,408.2
XS GIS Cut Line= 3
2095436.17167735288477.3895846312095265.59885576288647.962734297
2095154.92158368  288772.9624843
#Sta/Elev= 30
       0 1707.85       3 1707.32     5.3 1706.52    13.6 1700.48    42.4 1683.78
    52.6 1677.04    61.9 1673.27    71.2 1668.94    84.2 1661.82    97.1 1654.13
   102.7 1652.14   121.3 1650.73   143.5 1651.55   187.2 1652.32   216.4 1651.72
   233.6 1652.39   252.9  1651.9   262.8 1652.22  268.131651.931   271.6 1650.84
   276.8 1648.58   283.7 1648.28   286.1 1648.49   288.4 1649.15   293.61652.113
   317.2 1663.75   346.5  1677.2     368 1687.99     386 1696.35   408.2 1705.48
#Mann= 3 ,-1 , 0
       0      .1       0  268.13    .045       0   293.6      .1       0
Bank Sta=268.13,293.6
XS Rating Curve= 0 ,0
Exp/Cntr=0.3,0.1

Type RM Length L Ch R = 1 ,27059   ,445.9,455.9,443.3
XS GIS Cut Line= 2
2095230.44243002288336.7645377962094933.56769568288683.118831962
#Sta/Elev= 30
       0 1690.52     7.7 1687.02    38.5 1670.48    54.5 1662.84    75.5 1653.77
   87.981651.117    89.8 1650.67    94.2 1648.28    96.4 1647.57   102.8 1647.05
   107.1 1647.47     115  1650.9   117.31651.177     129 1651.09   138.3 1650.49
   189.5 1651.53   210.8 1650.89     220 1651.22   255.3 1650.81   271.3 1651.17
   277.9 1652.06   284.9 1653.84   287.2 1654.75   297.3 1659.28   305.9  1663.9
   320.8 1670.64   380.3 1696.36   396.6 1702.78   421.6 1711.89   456.2 1723.78
#Mann= 3 ,-1 , 0
       0      .1       0   87.98    .045       0   117.3      .1       0
Bank Sta=87.98,117.3
XS Rating Curve= 0 ,0
Exp/Cntr=0.3,0.1

Type RM Length L Ch R = 1 ,26603   ,508.9,513.3,502.5
XS GIS Cut Line= 2
 2095001.2758936288147.9627500472094618.46333903288552.910430968
#Sta/Elev= 30
       0 1681.05     9.6 1676.98    22.9 1672.38    33.1 1668.24    58.3 1659.53
    83.8 1652.99    89.7 1652.39   113.6 1651.75   190.6 1651.26  208.761649.673
   218.2 1646.76   223.5 1646.71   227.3 1647.26  232.731649.806   241.7 1650.25
   260.2 1649.29   274.2 1650.15   308.5 1650.03   332.2 1650.71   344.7 1650.56
   369.3 1651.43   380.8 1653.11   389.8 1655.34   457.5 1676.64   486.1 1686.75
   500.5 1690.54   510.9 1694.51   524.3 1702.27   543.4 1708.97   557.3  1714.9
#Mann= 3 ,-1 , 0
       0      .1       0  208.76    .045       0  232.73      .1       0
Bank Sta=208.76,232.73
XS Rating Curve= 0 ,0
Exp/Cntr=0.3,0.1

Type RM Length L Ch R = 1 ,26090   ,460.8,471.2,451.2
XS GIS Cut Line= 2
2094608.04669318288009.9417006222094329.40092501288421.400195301
#Sta/Elev= 30
       0 1687.59    17.5 1680.34    24.4 1676.22    37.3 1670.06    52.8 1661.69
    62.2 1657.18    72.9 1652.98    78.8 1651.27    90.6  1649.9   114.2 1649.12
   154.4 1648.88   179.9 1649.93  184.921649.787   192.2 1647.52   212.51649.255
   215.6 1649.47   225.2 1649.09   251.4 1649.06   279.6 1649.33   294.8 1648.63
   310.7 1648.79     315 1649.34   318.6 1650.67   352.8 1668.15   385.8 1683.89
   401.8 1692.78   404.8 1694.13   444.9 1708.74   466.2 1715.31   496.9 1727.57
#Mann= 3 ,-1 , 0
       0      .1       0  184.92    .045       0   212.5      .1       0
Bank Sta=184.92,212.5
XS Rating Curve= 0 ,0
Exp/Cntr=0.3,0.1

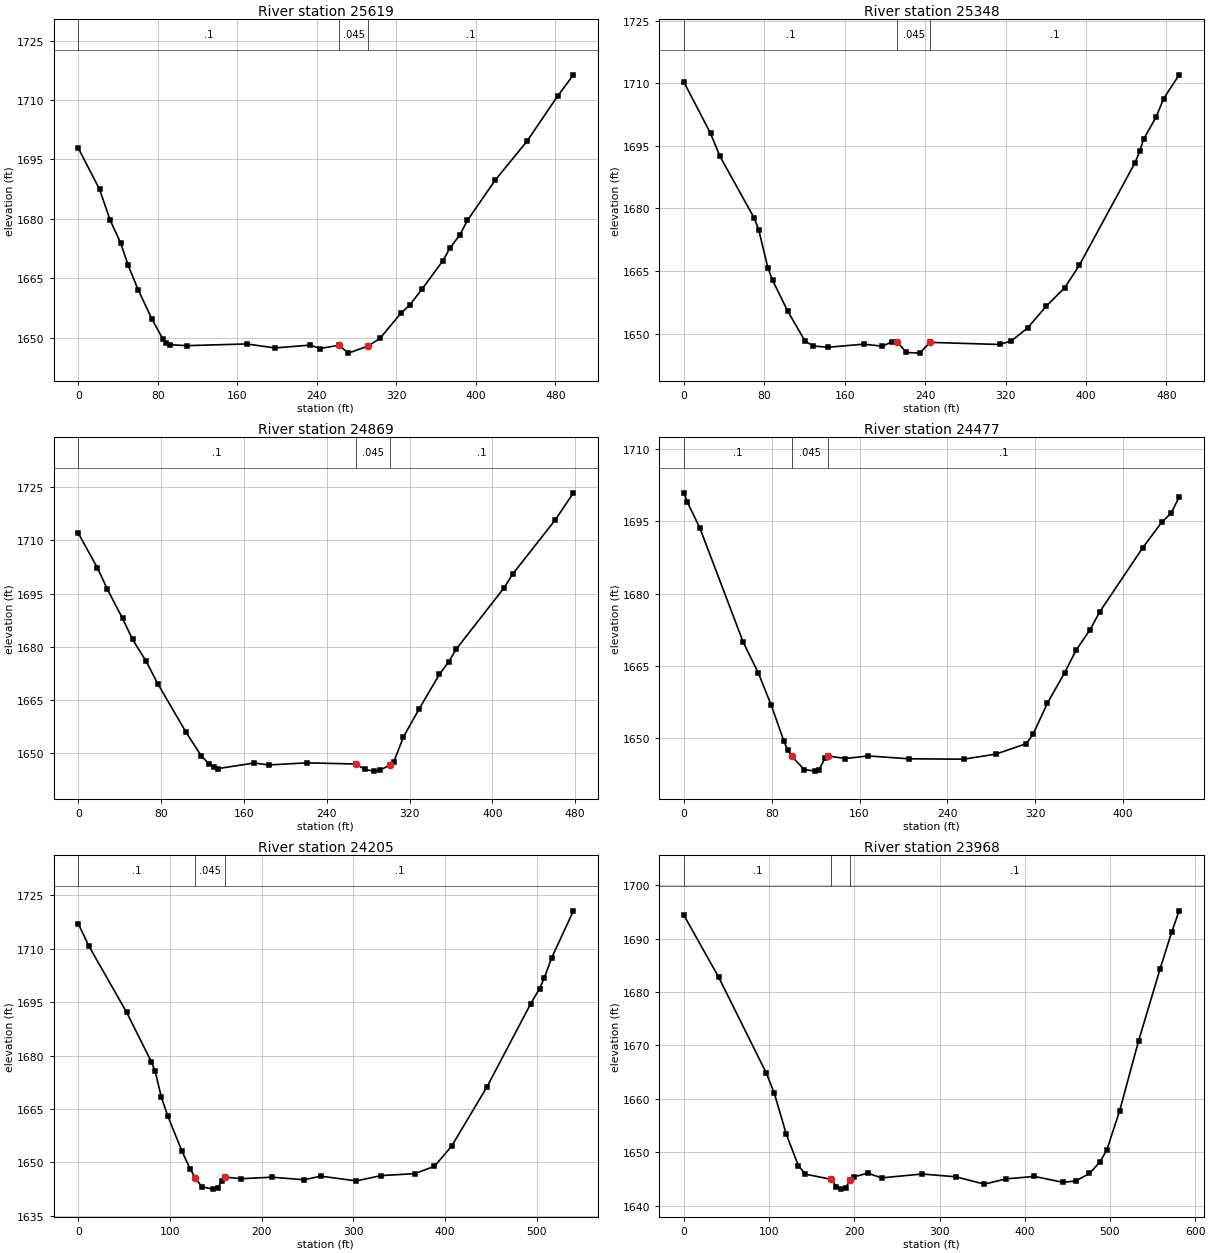
Type RM Length L Ch R = 1 ,25619   ,261.2,270.4,273.4
XS GIS Cut Line= 2
2094246.06743029287866.7126563792094063.77580011288330.254380211
#Sta/Elev= 30
       0 1697.85    21.4 1687.44      32 1679.66    42.5 1673.96    50.2 1668.22
    60.2 1662.08    74.3 1654.57    84.8 1649.76    88.4 1648.68    91.9 1648.19
   109.5 1647.96   169.4 1648.39   197.7 1647.38   232.9 1648.09   243.5 1647.23
  262.161648.073   271.7 1646.07  291.651647.879   303.4 1649.77   324.6 1656.18
   333.2 1658.15   345.7 1662.21   366.9 1669.46   373.9 1672.64   383.8 1675.92
   391.5 1679.62   419.2  1689.7   451.5 1699.64   482.4 1711.08   498.1 1716.37
#Mann= 3 ,-1 , 0
       0      .1       0  262.16    .045       0  291.65      .1       0
Bank Sta=262.16,291.65
XS Rating Curve= 0 ,0
Exp/Cntr=0.3,0.1

Type RM Length L Ch R = 1 ,25348   ,467.4,479.2,464.1
XS GIS Cut Line= 2
2094130.18216336287797.7022957062093783.82786918288147.962750047
#Sta/Elev= 30
       0 1710.23    26.4 1697.98    35.7 1692.51    69.7 1677.74    74.3 1674.86
    83.5 1665.71    88.1 1662.76     103 1655.45   120.4  1648.2   128.5 1647.02
   143.5 1646.72   178.6 1647.46   197.3 1646.97   206.6 1647.99  212.041648.004
   221.3 1645.47   234.6 1645.31  244.66 1647.89   314.2 1647.38   325.7 1648.24
   341.9 1651.37   360.6 1656.63   378.8 1661.01   393.2 1666.34   448.6 1690.91
   453.3 1693.65   457.2 1696.58   469.5 1701.83   477.2 1706.34   492.6 1712.02
#Mann= 3 ,-1 , 0
       0      .1       0  212.04    .045       0  244.66      .1       0
Bank Sta=212.04,244.66
XS Rating Curve= 0 ,0
Exp/Cntr=0.3,0.1

Type RM Length L Ch R = 1 ,24869   ,394.7,391.7,387.9
XS GIS Cut Line= 2
2093901.01529884 287585.462562712093548.15084711287908.379239708
#Sta/Elev= 30
       0    1712    18.4 1702.27    28.1 1696.21    42.7 1688.03    52.4 1682.08
    65.5 1675.95    76.7 1669.63   104.2 1655.88   118.9 1649.24   126.4 1646.99
   130.9 1646.07   135.2 1645.72     170 1647.27     184 1646.73   221.1 1647.33
  267.951646.991   276.8 1645.45   285.7 1644.99     291 1645.17  301.411646.803
   304.7 1647.55     314 1654.58   329.4 1662.59   348.8 1672.22   357.7 1675.72
   365.1 1679.36   411.1 1696.55   419.9  1700.6   460.7 1715.73   478.3 1723.37
#Mann= 3 ,-1 , 0
       0      .1       0  267.95    .045       0  301.41      .1       0
Bank Sta=267.95,301.41
XS Rating Curve= 0 ,0
Exp/Cntr=0.3,0.1

Type RM Length L Ch R = 1 ,24477   ,268.6,272.5,273.6
XS GIS Cut Line= 2
2093712.21351111287383.6398036332093416.64061144287724.785446793
#Sta/Elev= 30
       0 1700.92     2.8 1699.09    14.4 1693.65    53.9 1669.99    67.9  1663.5
    79.6 1656.84    91.1 1649.42    94.6 1647.59   98.131646.334   109.6 1643.54
   119.7 1643.22   122.9 1643.42   128.4 1645.84  130.83 1646.38     147 1645.83
   167.9 1646.37   204.8 1645.78   254.9  1645.7   284.2 1646.74   312.1 1648.92
   318.2 1650.86   331.2 1657.27     347 1663.63   357.3 1668.24   370.2 1672.55
     379 1676.26   418.1  1689.5   435.4 1694.79   444.1 1696.74   451.4 1700.03
#Mann= 3 ,-1 , 0
       0      .1       0   98.13    .045       0  130.83      .1       0
Bank Sta=98.13,130.83
XS Rating Curve= 0 ,0
Exp/Cntr=0.3,0.1

Type RM Length L Ch R = 1 ,24205   ,231.6,236.8,234.3
XS GIS Cut Line= 2
2093582.00511011287175.3062307982093171.84877819287526.868847877
#Sta/Elev= 30
       0 1717.04    11.6 1710.75    52.7 1692.17    79.7 1678.27    83.8  1675.6
    90.7 1668.24    97.7 1662.99   113.2 1653.08   121.8 1648.26  127.691645.639
   134.8 1643.12   146.6 1642.49   152.1 1642.77   156.4 1644.78  160.431645.853
     178 1645.42   210.8 1645.84   246.6 1645.12   264.4 1646.14   303.3  1644.8
   330.4 1646.29     367 1646.84   388.6 1648.91   407.4 1654.61   445.9 1671.23
   493.4 1694.48   503.2 1698.81   508.2 1701.69   516.5  1707.5   540.2 1720.67
#Mann= 3 ,-1 , 0
       0      .1       0  127.69    .045       0  160.43      .1       0
Bank Sta=127.69,160.43
XS Rating Curve= 0 ,0
Exp/Cntr=0.3,0.1

Type RM Length L Ch R = 1 ,23968   ,317.6,318.3,314.9
XS GIS Cut Line= 2
2093496.06761795286996.9210888742093027.31757119287340.671057537
#Sta/Elev= 30
       0 1694.35    40.7 1682.78    96.7 1664.79     106 1661.06   120.1 1653.34
   134.2  1647.5   142.4 1645.89  173.081644.905     179 1643.52   184.1 1643.08
   189.6 1643.35  195.241644.754   199.9 1645.39   215.6 1646.07   231.9 1645.19
   279.7 1645.91   319.6 1645.38   352.5 1644.01   378.2    1645   411.2 1645.46
   444.8 1644.36   459.7  1644.6     476 1646.01   488.2 1648.14   496.4 1650.43
   511.4 1657.75   533.6 1670.81     559 1684.39   572.4 1691.19   581.3 1695.22
#Mann= 3 ,-1 , 0
       0      .1       0  173.08    .045       0  195.24      .1       0
Bank Sta=173.08,195.24
XS Rating Curve= 0 ,0
Exp/Cntr=0.3,0.1

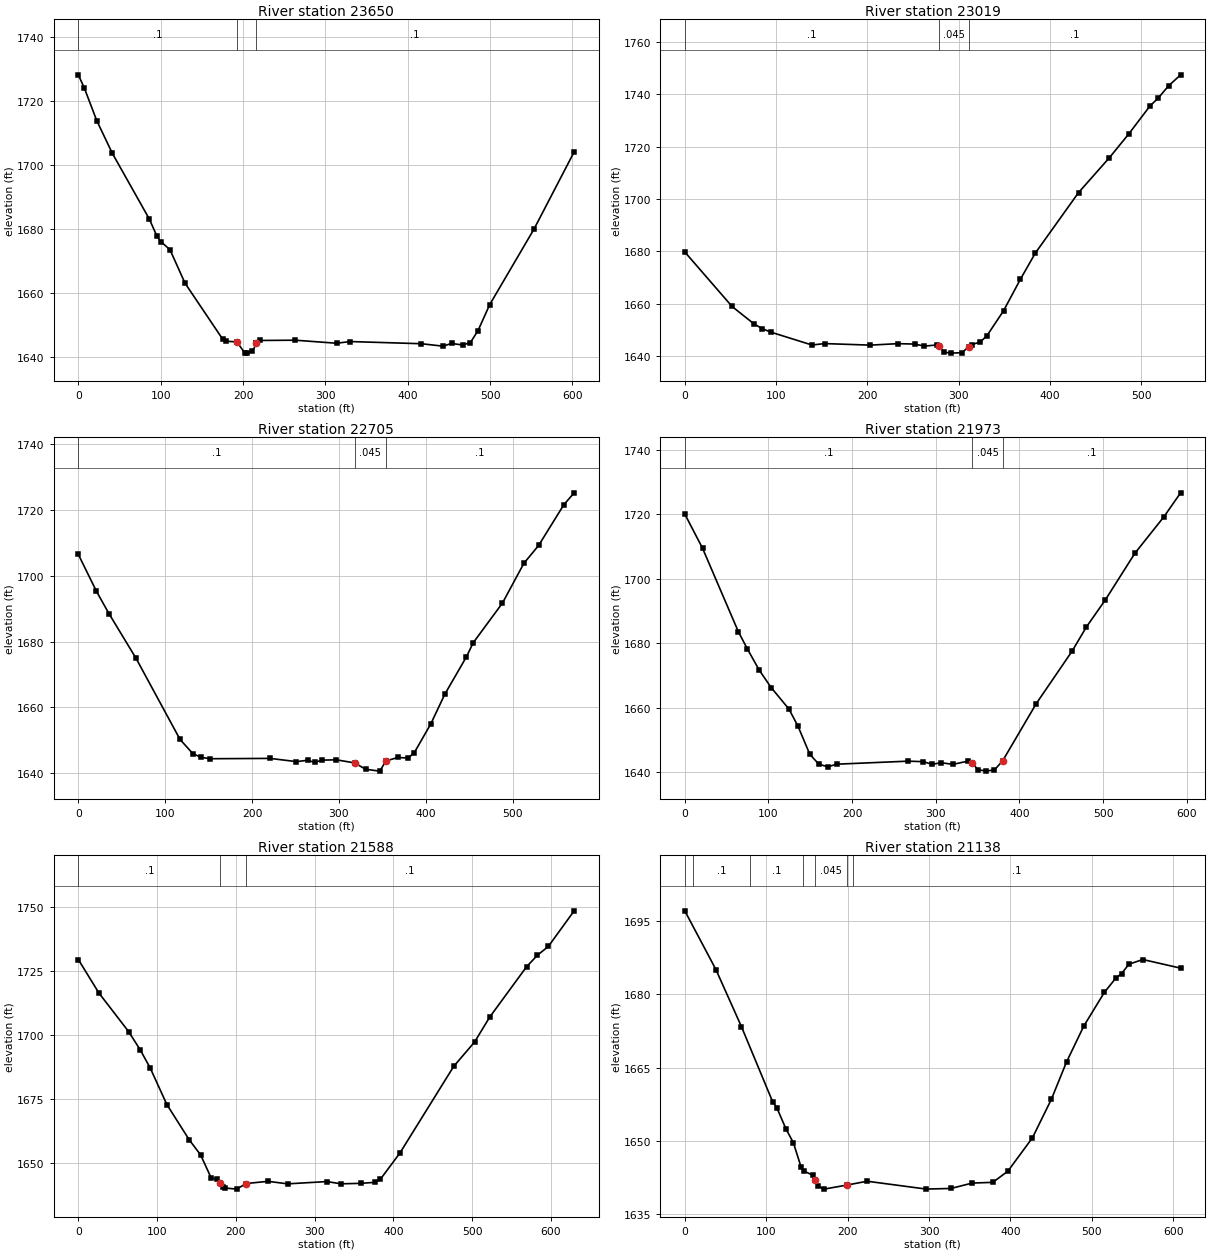
Type RM Length L Ch R = 1 ,23650   ,620.5,630.9,629.3
XS GIS Cut Line= 2
2093238.20822552286808.076322213 2092804.8751027287226.131916538
#Sta/Elev= 30
       0 1728.13     7.3 1723.99    22.4 1713.79    41.3 1703.59    86.2 1683.05
    95.5 1677.67   100.1 1676.02   111.3 1673.46   129.5 1663.02   175.1 1645.56
     179 1644.83  192.411644.671     202 1641.23   204.5 1641.13   211.4 1641.68
   216.1 1644.15   216.1 1644.16   220.8 1645.09   263.4 1645.17   313.6 1644.22
   330.1 1644.75   416.7 1644.07   442.9  1643.3   453.2 1644.17   466.6 1643.67
     476  1644.4   485.3 1648.15   499.6 1656.32   553.5 1679.98   602.1 1704.04
#Mann= 3 ,-1 , 0
       0      .1       0  192.41    .045       0   216.1      .1       0
Bank Sta=192.41,216.1
XS Rating Curve= 0 ,0
Exp/Cntr=0.3,0.1

Type RM Length L Ch R = 1 ,23019   ,307.5,313.7,309.9
XS GIS Cut Line= 2
2092933.56743062286748.223095462 2092542.9425557287125.827327132
#Sta/Elev= 30
       0 1679.72    51.8 1658.87    75.4 1652.32    84.6 1650.43      94 1649.09
   139.4 1644.13   153.1 1644.68   203.3 1644.09   233.3 1644.65   251.8  1644.5
   262.6 1643.71   276.3 1644.16  278.191643.701   284.3  1641.4   291.3 1641.03
   303.7  1641.2  310.921643.435   314.5 1644.32   323.7 1645.26   331.1 1647.71
   349.3 1657.25   367.8 1669.32   384.1 1679.31   431.4 1702.42   465.3  1715.8
   486.2 1724.75   509.7 1735.55   518.6 1738.54   530.2 1743.31   543.3 1747.48
#Mann= 3 ,-1 , 0
       0      .1       0  278.19    .045       0  310.92      .1       0
Bank Sta=278.19,310.92
XS Rating Curve= 0 ,0
Exp/Cntr=0.3,0.1

Type RM Length L Ch R = 1 ,22705   ,726.4,732.5,698.4
XS GIS Cut Line= 2
2092795.54670927286551.6083312182092345.02595678286901.868785545
#Sta/Elev= 30
       0 1706.49    20.9 1695.26    35.2 1688.51    66.4 1674.91   117.1 1650.21
   131.8 1645.91   141.2 1644.79   151.6 1644.36   220.7 1644.46   251.1 1643.48
   263.8 1643.89   272.1 1643.25   280.4 1643.93   297.1 1644.03  318.131643.084
   330.6 1641.16   346.9 1640.59   354.2  1643.7   367.7 1644.74   379.7 1644.58
   386.7 1646.21   405.8 1655.01   421.7 1663.92   446.7 1675.35   454.5 1679.63
   488.2 1691.72   512.9 1703.82   529.8 1709.23   558.9 1721.64   570.7 1725.23
#Mann= 3 ,-1 , 0
       0      .1       0  318.13    .045       0   354.2      .1       0
Bank Sta=318.13,354.2
XS Rating Curve= 0 ,0
Exp/Cntr=0.3,0.1

Type RM Length L Ch R = 1 ,21973   ,378.2,385.1,376.7
XS GIS Cut Line= 2
2092328.09882528286236.5043026212092096.32796335286782.077030376
#Sta/Elev= 30
       0 1720.02    21.2 1709.44      64 1683.59    74.7 1678.28    88.9 1671.71
   103.2 1666.28   124.6 1659.57   135.3  1654.3   149.5 1645.56   160.2 1642.54
   170.9  1641.7   181.6 1642.52   267.2 1643.46   285.1  1643.3   295.7 1642.48
   306.4 1642.98   320.6 1642.46   338.5 1643.47  343.871642.891   350.1 1640.86
   360.1 1640.37   370.2 1640.76  379.891643.508   420.2 1661.29   463.2 1677.61
   480.2 1685.06   502.8 1693.43   538.1 1707.87   572.8 1719.17   592.8  1726.6
#Mann= 3 ,-1 , 0
       0      .1       0  343.87    .045       0  379.89      .1       0
Bank Sta=343.87,379.89
XS Rating Curve= 0 ,0
Exp/Cntr=0.3,0.1

Type RM Length L Ch R = 1 ,21588   ,435.7,449.9,437.4
XS GIS Cut Line= 2
2092019.50495428286149.2646477072091773.41128635286728.691638455
#Sta/Elev= 30
       0 1729.37    26.2 1716.26    63.8 1701.26    78.8 1693.99    91.3 1686.98
   112.4 1672.76     141 1658.88   155.2 1653.11   168.8    1644   176.6 1643.64
  180.331642.292   183.7 1640.55   186.4 1640.17   200.9 1639.72  213.121641.908
   240.8 1642.77   265.7 1641.78   315.6 1642.67   333.4 1641.79   358.4 1641.98
   376.2 1642.36   383.3  1643.5   408.3 1653.83   476.6 1687.66   503.1 1697.18
   522.4 1706.94   569.1 1726.56   582.9 1731.07   596.7 1734.47   629.5 1748.39
#Mann= 3 ,-1 , 0
       0      .1       0  180.33    .045       0  213.12      .1       0
Bank Sta=180.33,213.12
XS Rating Curve= 0 ,0
Exp/Cntr=0.3,0.1

Type RM Length L Ch R = 1 ,21138   ,448,447.5,418.2
XS GIS Cut Line= 2
2091770.80728894286025.5667323772091378.87992319286491.712453634
#Sta/Elev= 30
       0 1697.14    38.2  1685.1    69.6 1673.37     108 1657.93   112.9 1656.79
   124.3 1652.39   133.3 1649.58   142.9 1644.55   146.8 1643.72   156.9 1642.92
  160.44 1641.93   163.9 1640.65   170.9 1640.05  199.73  1640.9     224 1641.67
   296.6 1640.06     327 1640.19   352.9 1641.29   378.3 1641.44   396.8 1643.73
     427 1650.58   450.3  1658.5   468.9 1666.15   490.1 1673.51   515.4 1680.43
   529.5 1683.36   536.5 1684.27   545.4 1686.18   562.6 1687.15     609 1685.38
#Mann= 7 ,-1 , 0
       0      .1       0   10.34      .1       0   80.32      .1       0
  144.74      .1       0  160.44    .045       0  199.73      .1       0
  206.18      .1       0
Bank Sta=160.44,199.73
XS Rating Curve= 0 ,0
Exp/Cntr=0.3,0.1