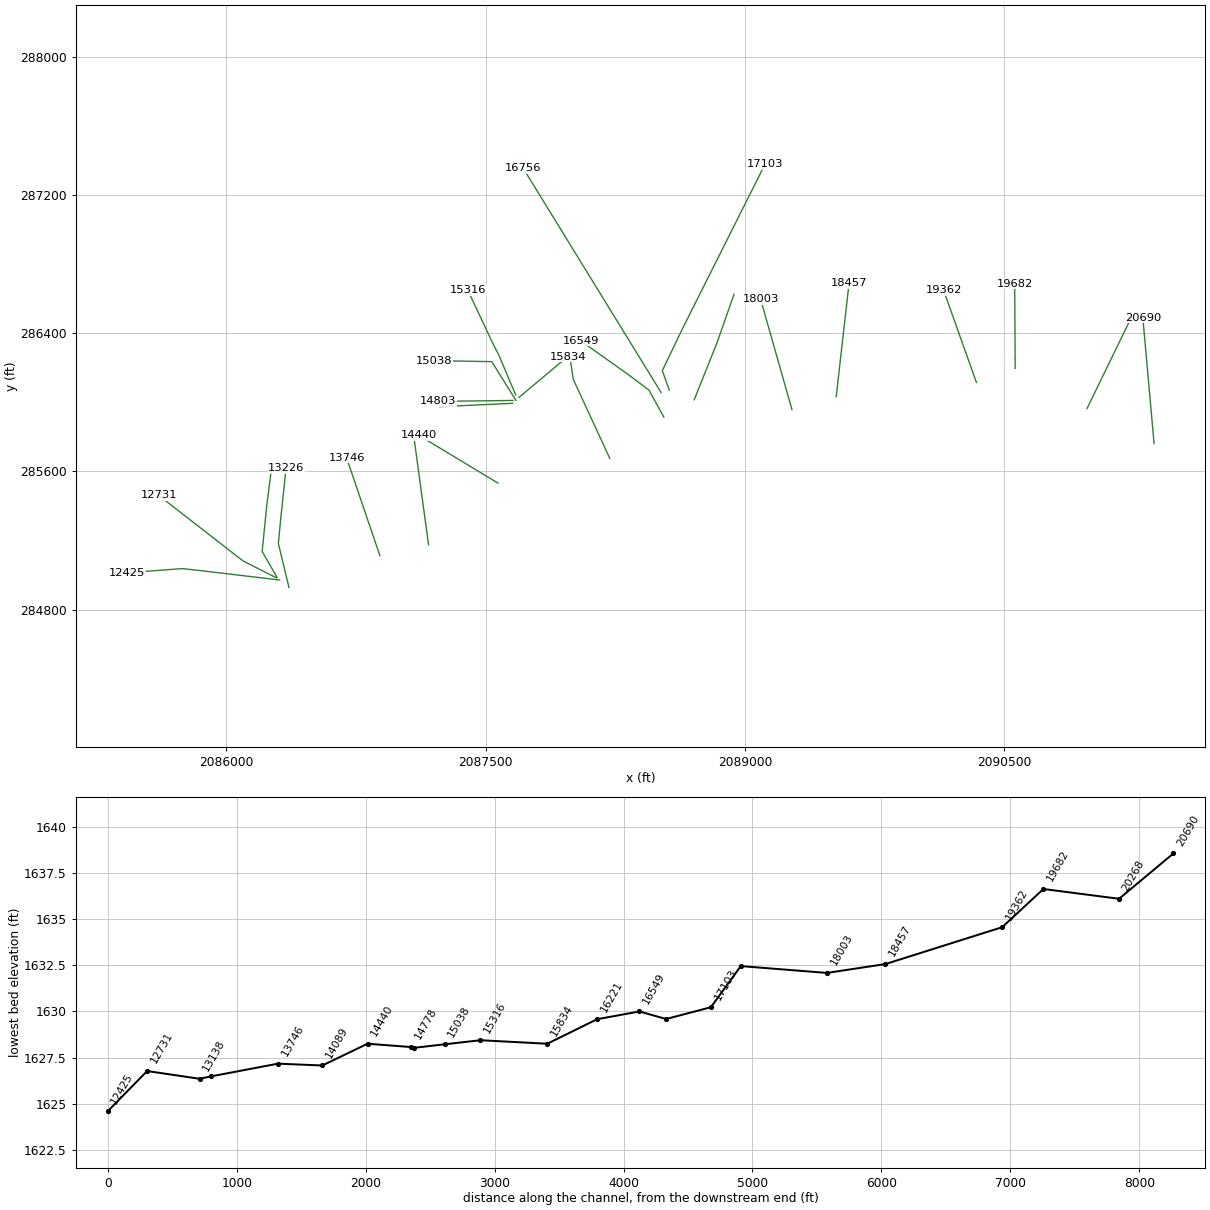
HEC-RAS study MILLCK1.prj: MILLCK1

--- MILLCK1.g01 (geometry) --- (continued)

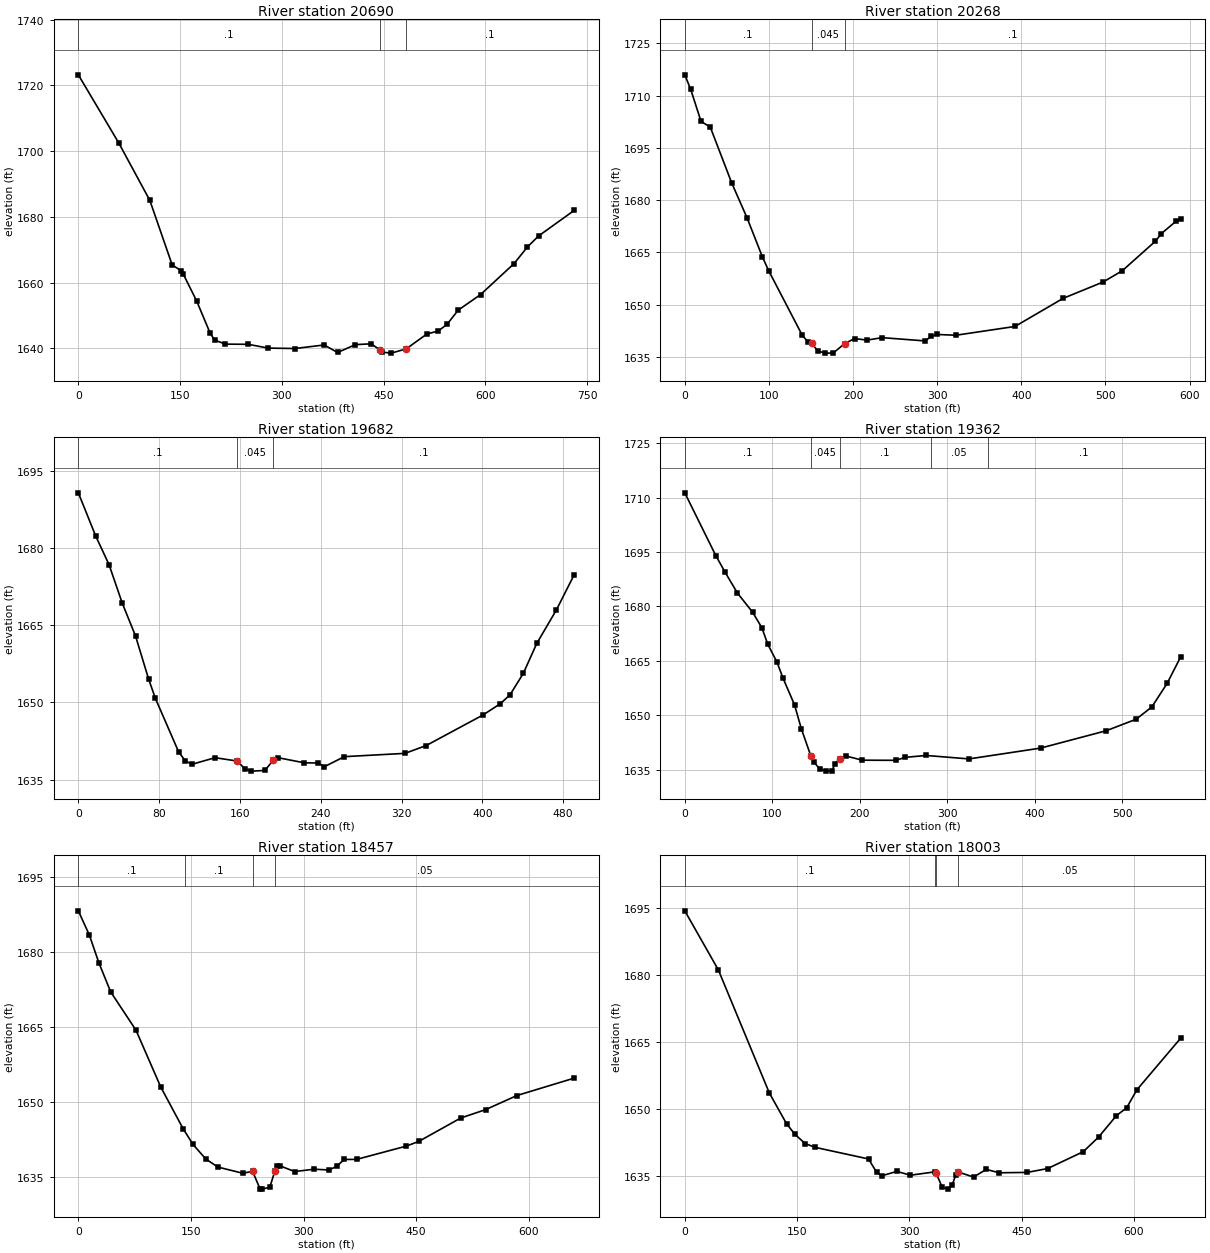
Type RM Length L Ch R = 1 ,20690   ,427,421.8,401.3
XS GIS Cut Line= 2
2091365.88636131285760.6657482692091300.93653114286488.551776077
#Sta/Elev= 30
       0 1723.24    59.3 1702.62   105.4 1685.03   138.3 1665.41   151.5 1663.64
   154.8 1662.56   174.5 1654.39   194.3 1644.63   200.9 1642.54   216.8 1641.31
   250.3 1641.25   279.9  1640.1   319.2 1639.97   362.3 1641.05   382.1 1638.77
   408.4 1641.16   431.6  1641.4   444.11639.605   447.9 1638.86   461.1 1638.57
   483.21639.857   513.8  1644.4   530.3 1645.28   543.5 1647.34   559.9 1651.65
   592.9 1656.39   642.3 1665.83     662 1670.89   678.5 1674.24   730.8 1681.98
#Mann= 3 ,-1 , 0
       0      .1       0   444.1    .045       0   483.2      .1       0
Bank Sta=444.1,483.2
XS Rating Curve= 0 ,0
Exp/Cntr(USF)=0,0
Exp/Cntr=0.3,0.1

Type RM Length L Ch R = 1 ,20268   ,572.1,586.6,587.9
XS GIS Cut Line= 2
2090977.83840245285963.0668573832091235.65087894286493.014616385
#Sta/Elev= 30
       0 1715.94       7 1711.78    19.3 1702.58    30.3 1700.94    55.8  1684.9
    74.1 1674.85    92.3 1663.67    99.6  1659.8   139.7 1641.19   146.7 1639.27
  150.611638.986     158 1636.75   166.5 1636.11   176.4 1636.14   189.9 1638.81
   201.8  1640.3   216.3 1639.84   234.6 1640.55   285.7 1639.61     293 1640.94
   300.3 1641.46   322.2 1641.24   392.4 1643.76   449.8 1651.84   497.3 1656.52
     520 1659.75   559.2 1668.19   566.5 1670.42   583.8 1673.93   589.3 1674.49
#Mann= 3 ,-1 , 0
       0      .1       0  150.61    .045       0   189.9      .1       0
Bank Sta=150.61,189.9
XS Rating Curve= 0 ,0
Exp/Cntr=0.3,0.1

Type RM Length L Ch R = 1 ,19682   ,310.4,319.8,322
XS GIS Cut Line= 2
2090562.47374761286196.139553964 2090559.8697502286687.025055125
#Sta/Elev= 30
       0  1690.7    17.2 1682.31    30.4 1676.75    43.5 1669.26    56.6 1662.91
    69.7 1654.45    76.3 1650.77    99.3 1640.38   105.8 1638.67   112.4 1637.96
   135.4 1639.25  157.091638.604   164.9 1637.12   171.4 1636.64   184.6 1636.77
  193.081638.762   197.7 1639.25   223.9 1638.25   237.1 1638.22   243.6  1637.5
   263.3 1639.45   323.4 1640.09   344.4 1641.61   400.5 1647.53   417.5 1649.69
   427.4 1651.46   440.5 1655.61   453.9 1661.45   473.3 1667.95   490.9 1674.78
#Mann= 3 ,-1 , 0
       0      .1       0  157.09    .045       0  193.08      .1       0
Bank Sta=157.09,193.08
XS Rating Curve= 0 ,0
Exp/Cntr=0.3,0.1

Type RM Length L Ch R = 1 ,19362   ,897.1,905.4,878.7
XS GIS Cut Line= 2
 2090338.5155341286114.1085500422090148.41125554286647.962469205
#Sta/Elev= 30
       0 1711.35    35.5    1694    46.2 1689.39    60.1 1683.72    77.5 1678.41
      88 1674.17    94.9 1669.54   105.4 1664.63   112.3 1660.19   125.4 1652.87
   133.2 1646.25  144.131638.713   147.2  1637.2   154.1 1635.17   161.1 1634.57
   168.1 1634.74   171.6 1636.47  176.89 1638.05   184.5 1638.72   202.9 1637.59
   241.2 1637.55   251.7 1638.37     276 1638.89   324.8 1637.94   406.6 1640.92
   481.5  1645.7   515.8 1648.88   533.8 1652.28   551.2 1658.75   566.7 1666.07
#Mann= 5 ,-1 , 0
       0      .1       0  144.13    .045       0  176.89      .1       0
  281.09     .05       0  346.14      .1       0
Bank Sta=144.13,176.89
XS Rating Curve= 0 ,0
Exp/Cntr=0.3,0.1

Type RM Length L Ch R = 1 ,18457   ,441.3,453.4,452.9
XS GIS Cut Line= 2
2089527.31768143286032.0772180412089601.53636503286688.327217877
#Sta/Elev= 30
       0 1688.31    14.7 1683.45    27.3 1677.92    43.1 1672.07    76.8  1664.4
   109.8 1653.01   139.5 1644.69   152.7 1641.52   169.7 1638.62   185.8 1636.99
   218.8 1635.76  232.131636.112   241.9 1632.67   245.2 1632.57   255.1 1632.97
  261.56 1636.11     265 1637.12   268.3 1637.25   288.1 1636.09   314.2 1636.56
   334.3  1636.4   344.2 1637.17   354.2 1638.51   370.7 1638.53   436.7 1641.18
   453.2 1642.11   509.3 1646.81   542.4 1648.49   584.2 1651.32   660.4  1654.8
#Mann= 4 ,-1 , 0
       0      .1       0  141.84      .1       0  232.13    .045       0
  261.56     .05       0
Bank Sta=232.13,261.56
XS Rating Curve= 0 ,0
Exp/Cntr=0.3,0.1

Type RM Length L Ch R = 1 ,18003   ,652.4,668.6,627.9
XS GIS Cut Line= 2
2089271.42445015285957.0342382962089090.43433524286594.440451479
#Sta/Elev= 30
       0 1694.38    44.8 1681.17     113  1653.6     136 1646.72   147.1 1644.37
   160.8 1642.29   174.4 1641.43   245.6 1638.84   256.2 1635.88   263.1 1635.07
   283.5 1636.06   301.4  1635.2   334.7 1635.97   335.9 1635.63   343.9 1632.55
   351.6 1632.09   357.2 1632.95     362 1635.21   365.4 1635.92   385.9 1634.79
   402.9 1636.51     420 1635.75   457.5 1635.83   484.8 1636.69   532.5 1640.47
     553 1643.75   576.8 1648.54   590.5 1650.29   604.1 1654.31   662.6 1665.86
#Mann= 4 ,-1 , 0
       0      .1       0   334.7      .1       0   335.9    .045       0
   365.4     .05       0
Bank Sta=335.9,365.4
XS Rating Curve= 0 ,0
Exp/Cntr=0.3,0.1

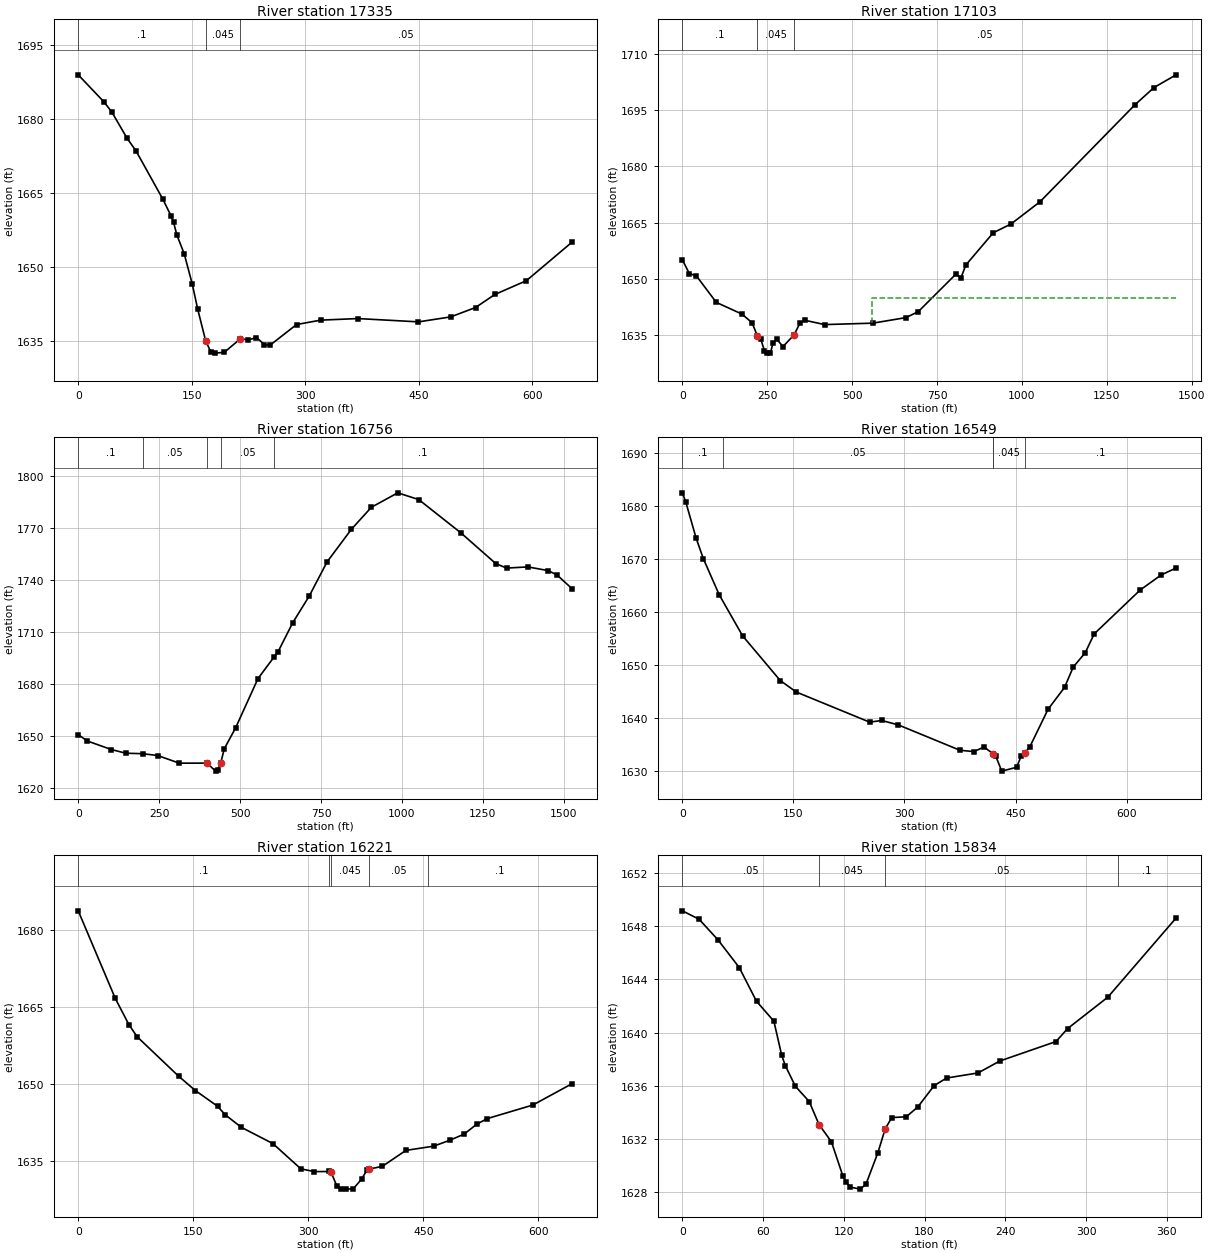
Type RM Length L Ch R = 1 ,17335   ,230.7,231.6,235.6
XS GIS Cut Line= 3
2088706.18234458286014.4640393132088838.51558137286345.879411966
2088936.17155403286624.525180131
#Sta/Elev= 30
       0  1688.9      34 1683.41    44.4 1681.35    64.6 1676.01    76.4 1673.46
   111.7  1663.7   122.7 1660.27   125.9 1659.02   130.2 1656.45     140  1652.6
   150.6 1646.48   157.7 1641.45   168.3 1634.96   175.3 1632.65   180.7 1632.46
     193 1632.63   214.2 1635.38   224.8 1635.14   235.4 1635.62     246 1634.19
   253.1 1634.04   288.4 1638.26   320.2 1639.15   369.4 1639.47   449.4  1638.8
     492 1639.81   524.8 1641.71   550.2 1644.35   591.9 1647.15   652.1 1654.95
#Mann= 3 ,-1 , 0
       0      .1       0   168.3    .045       0   214.2     .05       0
Bank Sta=168.3,214.2
XS Rating Curve= 0 ,0
Exp/Cntr=0.3,0.1

Type RM Length L Ch R = 1 ,17103   ,306.4,347.4,360.2
XS GIS Cut Line= 4
2088561.78905841286069.3568564642088521.49262699286182.638773481
2088640.59865436286430.5147413762089115.24631749287377.070091927
#Sta/Elev= 30
       0 1655.09    20.5 1651.41    41.4 1650.79     100 1643.74   175.9 1640.61
   205.5 1638.29   220.6 1634.87   230.8 1633.99   241.7 1630.88     249 1630.23
   259.5 1630.34   267.2 1632.95   278.1 1633.93   296.3 1631.97   329.1 1635.09
   347.3 1638.38   361.8 1638.96   419.1 1637.83   560.9 1638.21   658.7 1639.69
     695 1641.29   805.6 1651.26   820.3 1650.24     835  1653.7   915.7 1662.28
   968.5 1664.65  1053.6 1670.55  1333.3 1696.38  1389.2 1700.95  1454.1 1704.33
#Mann= 3 , 0 , 0
       0      .1       0   220.6    .045       0   329.1     .05       0
#XS Ineff= 2 , 0
                          559.86         1644.94
Permanent Ineff=
       F       F
Bank Sta=220.6,329.1
XS Rating Curve= 0 ,0
Exp/Cntr=0.3,0.1

Type RM Length L Ch R = 1 ,16756   ,186.9,206.5,210.8
XS GIS Cut Line= 2
2088514.81917778286055.3125210262087716.21976213 287354.87835978
#Sta/Elev= 30
       0 1650.62    28.4 1646.94   102.3 1642.04     147 1639.92   198.7 1639.64
   245.4  1638.6   312.2 1634.18   398.1 1634.21   424.3 1629.59   431.5 1630.52
  440.35 1634.31   451.2 1642.48   485.9 1654.41   555.2  1682.9     606 1695.64
   616.8 1698.22     663 1715.24   713.1 1730.34     769 1750.27     844 1769.04
   905.6  1781.7   987.2 1790.04    1052 1786.15  1182.9 1766.85  1290.1 1749.22
  1323.5 1746.66  1389.3 1747.33    1452  1745.2  1479.4 1742.64  1525.3 1734.85
#Mann= 5 ,-1 , 0
       0      .1       0   198.7     .05       0   398.1    .045       0
  440.35     .05       0     606      .1       0
Bank Sta=398.1,440.35
XS Rating Curve= 0 ,0
Exp/Cntr(USF)=0,0
Exp/Cntr=0.3,0.1

Type RM Length L Ch R = 1 ,16549   ,327.4,328.3,300.6
XS GIS Cut Line= 4
2088530.33321093285913.9272432792088444.09450629286070.046827588
2088319.05212924286163.8607053332088048.28764618286356.159431985
#Sta/Elev= 30
       0 1682.55     4.8 1680.74    18.6 1673.99    28.3 1670.13    49.8 1663.29
    81.4 1655.54   132.2 1647.11   153.8 1644.94     253 1639.25   269.2 1639.56
   291.5 1638.74   374.9 1633.94   393.8 1633.69   407.3 1634.55   419.4 1633.32
   420.2 1633.26   423.4 1632.78   431.4    1630   451.5 1630.73   457.4 1632.78
   462.1 1633.38   469.1 1634.53   493.9 1641.68   516.2 1645.81   527.9 1649.65
   544.1 1652.35   556.2 1655.91   618.5 1664.22   646.8 1667.05   666.8 1668.35
#Mann= 5 ,-1 , 0
       0      .1       0   55.25     .05       0   419.4     .05       0
   420.2    .045       0   462.1      .1       0
Bank Sta=420.2,462.1
XS Rating Curve= 0 ,0
Exp/Cntr=0.3,0.1

Type RM Length L Ch R = 1 ,16221   ,405.1,386.6,337.9
XS GIS Cut Line= 3
2088217.76519062285674.4133452182088006.48410895286132.337516218
2087985.65081728286270.358565629
#Sta/Elev= 30
       0 1683.73    48.3  1666.7      66 1661.61    76.9 1659.22   131.1 1651.53
   152.8 1648.76   181.7 1645.71   191.5 1644.07   212.8  1641.6   253.9 1638.44
   290.4 1633.52   308.1 1632.99   327.5 1633.01   329.8 1632.88     337 1630.27
   342.3 1629.69   349.6 1629.58   358.7 1629.65   369.6 1631.53   376.8 1633.34
   379.4 1633.48   396.7 1634.02   427.4 1637.12   463.6 1637.94   485.2 1639.12
   503.2 1640.28   519.9 1642.22   533.2 1643.29   592.9 1645.94   643.9 1650.08
#Mann= 5 ,-1 , 0
       0      .1       0   327.5      .1       0   329.8    .045       0
   379.4     .05       0  455.97      .1       0
Bank Sta=329.8,379.4
XS Rating Curve= 0 ,0
Exp/Cntr=0.3,0.1

Type RM Length L Ch R = 1 ,15834   ,485,518.4,543.8
XS GIS Cut Line= 2
2087692.68224311 286028.171057882087973.93200868286263.848079965
#Sta/Elev= 30
       0 1649.14    12.4 1648.51    26.4 1646.97    42.3 1644.88    55.1 1642.35
      68 1640.86    73.8 1638.31    76.5 1637.52      84 1635.97    94.3 1634.82
  101.561633.098   110.8  1631.8   119.3 1629.23   121.9 1628.75   124.9  1628.4
   132.2 1628.25   136.4 1628.61   145.3 1630.98  150.711632.764   155.6 1633.62
   166.4 1633.68     175 1634.42   187.1 1636.02   196.4 1636.59   219.7 1636.97
     236 1637.87   277.7 1639.33   286.3  1640.3   316.2 1642.66   366.9  1648.6
#Mann= 4 ,-1 , 0
       0     .05       0  101.56    .045       0  150.71     .05       0
  323.41      .1       0
Bank Sta=101.56,150.71
XS Rating Curve= 0 ,0
Exp/Cntr=0.3,0.1

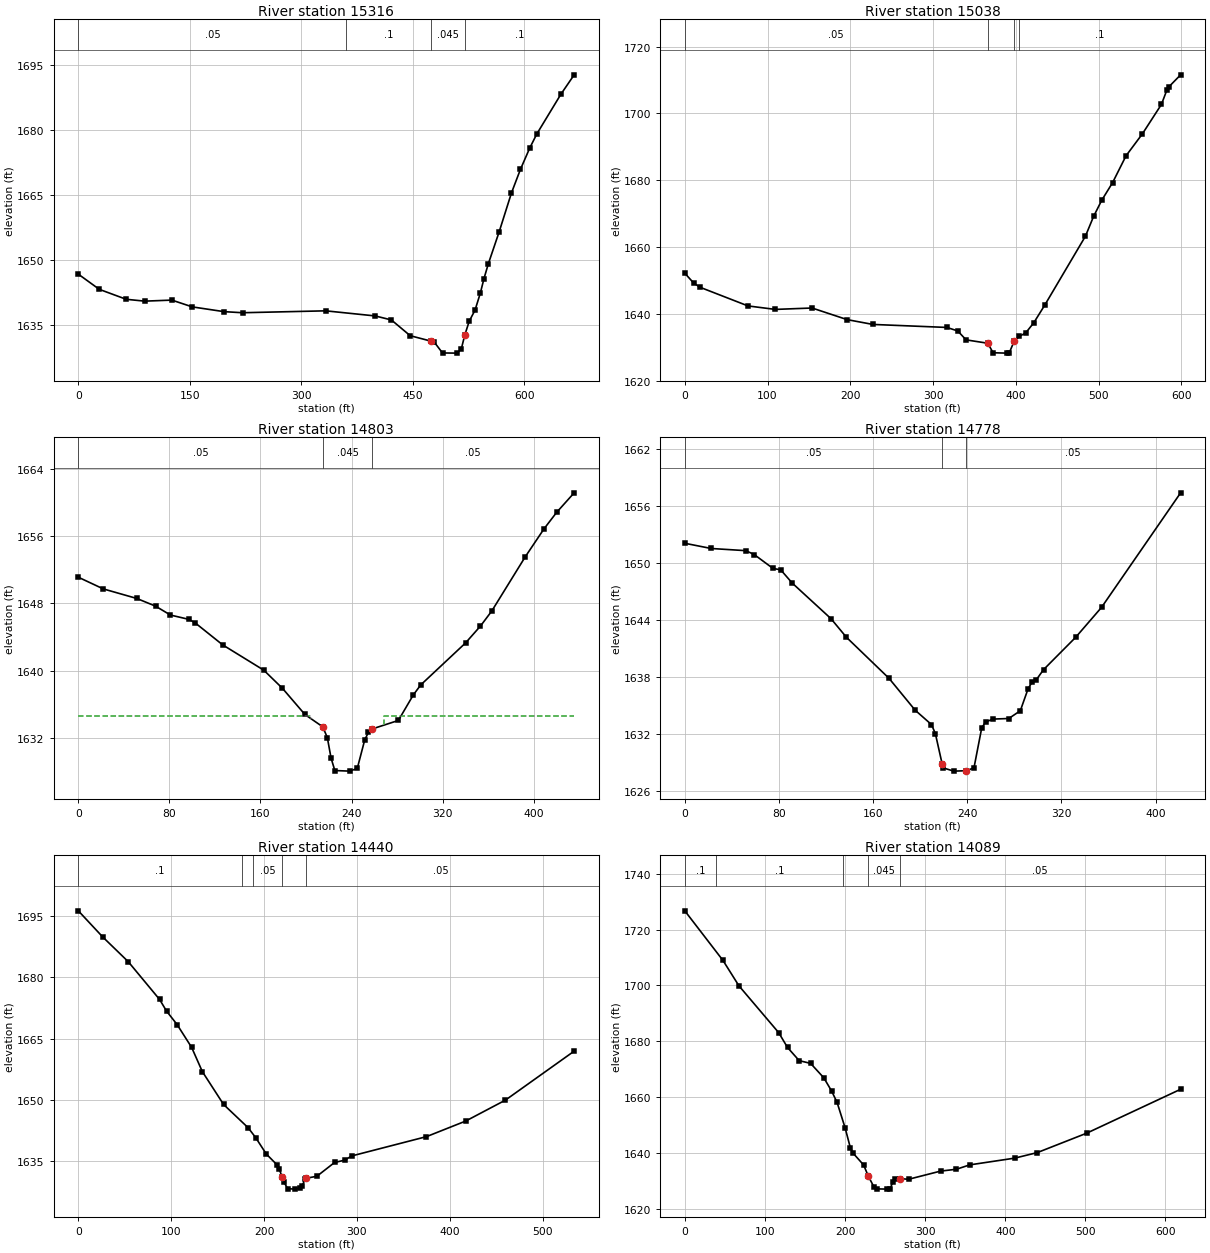
Type RM Length L Ch R = 1 ,15316   ,250.4,277.4,299.4
XS GIS Cut Line= 4
 2087673.1507861286042.4938638812087578.09881085286267.754240125
2087539.03622493286344.577249214 2087395.8071807286649.264631957
#Sta/Elev= 30
       0  1646.7    28.2 1643.19    64.4 1640.89    89.3 1640.46   125.9  1640.7
   153.4 1639.13   196.2 1638.03     221 1637.78   332.9 1638.22   399.6 1637.04
   421.4 1636.11   446.7 1632.47   474.5 1631.22   479.4 1630.91   490.2 1628.48
   510.3 1628.44   515.6 1629.49  520.261632.665   526.2 1635.84     534 1638.39
   541.2 1642.37     546 1645.67   551.9 1649.11   566.4 1656.46     583 1665.48
   595.1 1670.94   607.6 1675.86   617.1 1679.11   649.5 1688.29   667.4 1692.79
#Mann= 4 ,-1 , 0
       0     .05       0   360.8      .1       0   474.5    .045       0
  520.26      .1       0
Bank Sta=474.5,520.26
XS Rating Curve= 0 ,0
Exp/Cntr=0.3,0.1

Type RM Length L Ch R = 1 ,15038   ,234.4,235.5,236.1
XS GIS Cut Line= 3
2087674.75347319286010.7675493812087534.99653485286234.725762874
2087199.92699501286240.802194297
#Sta/Elev= 30
       0 1652.15    10.7 1649.21    18.4 1647.94    76.4 1642.35   109.4 1641.31
   153.8 1641.73   196.2 1638.25   227.3 1636.81   316.7 1635.91   329.8 1634.86
   339.9 1632.19   366.1 1631.18   372.5 1628.33   388.9 1628.22   392.2 1628.39
   397.9 1631.76   404.4 1633.26   411.9 1634.27   421.7 1637.32   434.8 1642.54
     484 1663.19   493.9 1669.13   503.7 1673.96   516.9 1679.27   533.2 1687.33
     553 1693.91   575.9 1702.69   582.5 1707.01   584.9 1707.96   599.1 1711.55
#Mann= 4 ,-1 , 0
       0     .05       0   366.1    .045       0   397.9     .05       0
   404.4      .1       0
Bank Sta=366.1,397.9
XS Rating Curve= 0 ,0
Exp/Cntr=0.5,0.3

Type RM Length L Ch R = 1 ,14803   ,24.9,24.4,30
XS GIS Cut Line= 2
2087658.34700993286010.1599390512087222.93055794286004.604175881
#Sta/Elev= 30
       0  1651.1    21.9 1649.71    51.4 1648.57    67.8 1647.66    80.9  1646.6
    97.3 1646.08   102.8 1645.65   126.8 1643.05   162.9 1640.04   179.3 1637.88
     199 1634.77   214.7  1633.3   218.7 1632.02     222 1629.57   225.3  1628.1
   238.4 1628.03     245 1628.35   251.5 1631.72   254.8 1632.66   258.1 1633.05
   281.1 1634.06   294.2 1637.09   300.7 1638.28   340.1 1643.28   353.2 1645.29
   363.1 1647.07   392.6 1653.54     409 1656.85   420.2 1658.83   435.5 1661.14
#Mann= 3 ,-1 , 0
       0     .05       0   214.7    .045       0   258.1     .05       0
#XS Ineff= 2 , 0
           204.7  1634.6   268.1          1634.6
Permanent Ineff=
       F       F
Bank Sta=214.7,258.1
XS Rating Curve= 0 ,0
Exp/Cntr=0.5,0.3

Type RM Length L Ch R = 1 ,14778   ,343.9,338.1,329.7
XS GIS Cut Line= 2
2087655.56945643285993.4933057132087234.73598051285974.048790798
#Sta/Elev= 30
       0  1652.1    22.4 1651.55    51.9 1651.32      59 1650.91    74.9 1649.45
    81.5  1649.3    91.3  1647.9   124.2 1644.15   137.3 1642.19   173.5 1637.86
   195.7  1634.5   209.6 1632.98   212.9 1632.03   218.61628.865   219.4 1628.42
   228.5 1628.07  238.911628.111   245.7 1628.41   252.3 1632.63   255.6 1633.26
   262.1 1633.56   275.3 1633.62   285.1 1634.44   291.7 1636.76     295 1637.44
   298.3 1637.64   304.8 1638.77   332.1 1642.18   354.1 1645.34   421.3 1657.42
#Mann= 3 ,-1 , 0
       0     .05       0   218.6    .045       0  238.91     .05       0
Bank Sta=218.6,238.91
XS Rating Curve= 0 ,0
Exp/Cntr=0.5,0.3

Type RM Length L Ch R = 1 ,14440   ,362.5,351.3,330.2
XS GIS Cut Line= 2
2087570.28616244285532.0772337912087113.25492427285808.119004548
#Sta/Elev= 30
       0 1696.16    26.1 1689.82    53.7 1683.76    87.5 1674.53    95.1 1671.66
   106.3 1668.42     122 1662.84   133.5 1656.94   156.4 1648.91   182.8 1643.24
   190.9 1640.84   202.4 1636.82   213.8 1634.21   216.2 1633.18   219.61631.166
   221.6 1629.88   225.4 1628.37   233.1 1628.25     239  1628.5   240.8    1629
   244.6 1630.83  245.671630.926   256.8 1631.38   275.9 1634.75   286.8 1635.32
   294.4 1636.35   374.9 1641.06   417.1 1644.86   459.9 1649.97   533.9 1661.92
#Mann= 5 ,-1 , 0
       0      .1       0     176      .1       0  188.17     .05       0
   219.6    .045       0  245.67     .05       0
Bank Sta=219.6,245.67
XS Rating Curve= 0 ,0
Exp/Cntr=0.3,0.1

Type RM Length L Ch R = 1 ,14089   ,338.5,343.2,345.8
XS GIS Cut Line= 2
2087169.24464169  285175.30629382087085.91114694285788.587547541
#Sta/Elev= 30
       0  1726.7    47.7 1708.92    67.6 1699.84   117.2 1683.09   128.2 1677.79
   142.8 1673.06     157 1672.09   173.5 1666.93   183.3 1662.17   190.1  1658.1
     200  1649.1   206.6 1641.95   209.9 1639.99   223.2 1635.72  229.231631.611
   236.4 1627.68   239.7 1627.16     253 1627.07   256.3 1627.24   259.6 1629.51
   262.9 1630.61  268.521630.807   279.5 1630.61   319.2 1633.52   339.1 1634.19
   355.6 1635.75   411.9 1638.17     440 1640.15   501.5 1647.08   618.9 1662.82
#Mann= 5 ,-1 , 0
       0      .1       0   38.69      .1       0  197.85     .05       0
  229.23    .045       0  268.52     .05       0
Bank Sta=229.23,268.52
XS Rating Curve= 0 ,0
Exp/Cntr=0.3,0.1

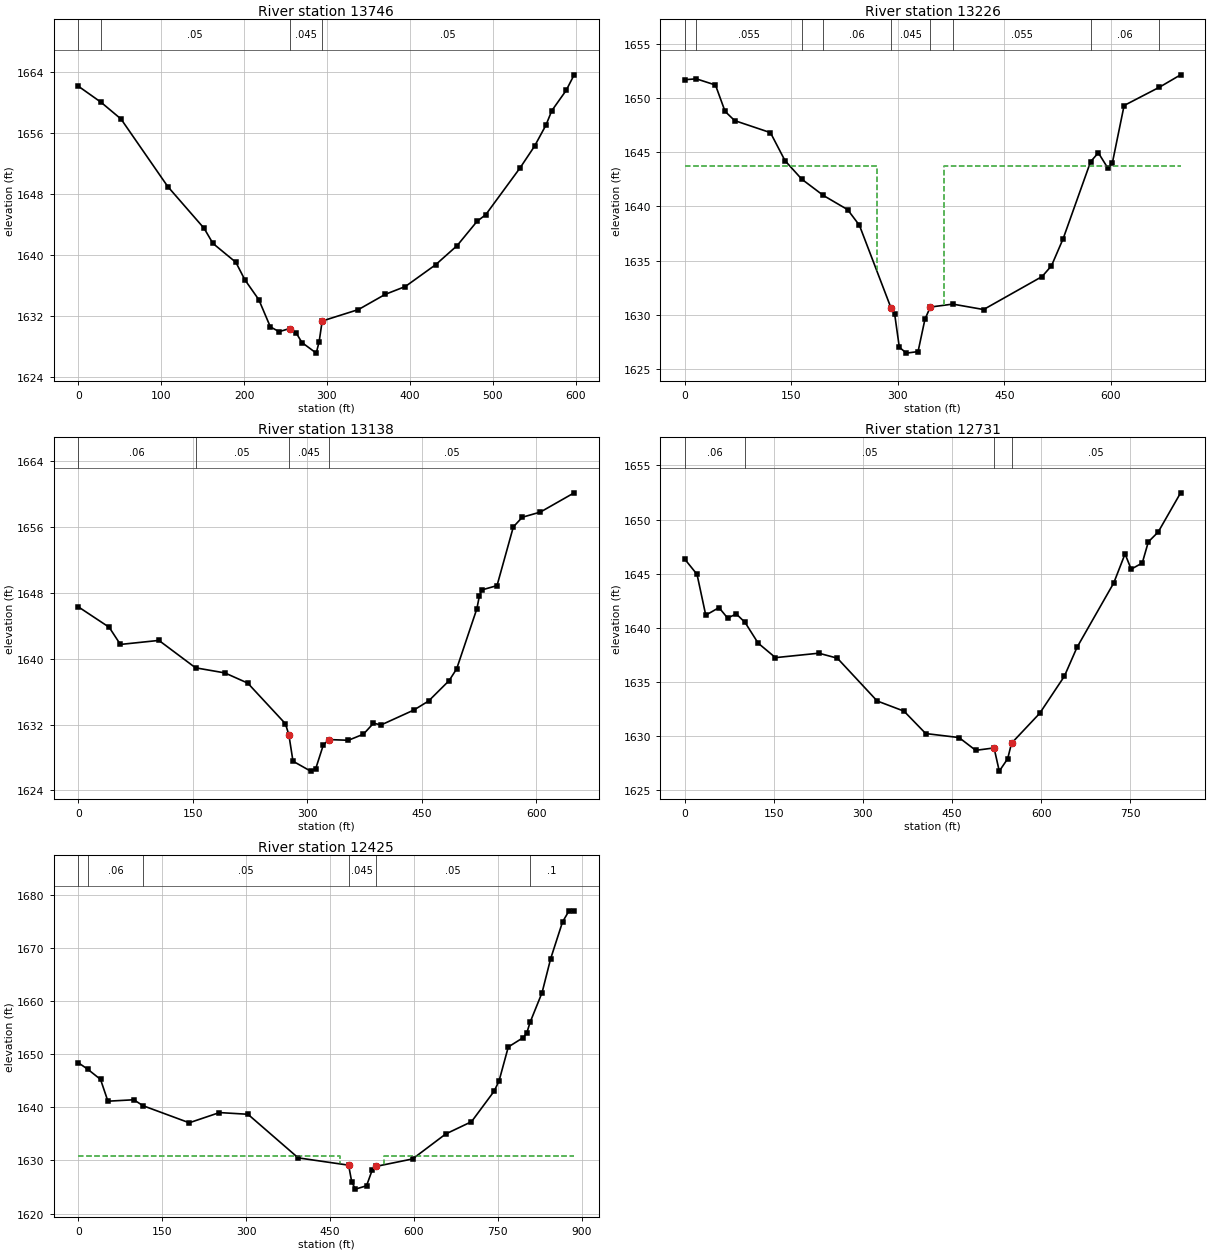
Type RM Length L Ch R = 1 ,13746   ,531.3,519.6,508.7
XS GIS Cut Line= 2
2086887.99454802 285111.504256042086695.28627202285677.910603538
#Sta/Elev= 30
       0 1662.15    27.2 1660.06    51.5 1657.85   107.9    1649   151.8 1643.52
   162.4 1641.55   190.1 1639.07   200.9 1636.79   217.8 1634.17   231.7 1630.61
   242.3 1629.98  255.011630.396   262.9 1629.81   269.8 1628.56   287.1 1627.17
   290.6 1628.68  294.241631.377     338 1632.88   370.3 1634.87   394.6  1635.9
   431.1 1638.75     457 1641.25   481.2 1644.45   491.6 1645.31   533.2 1651.47
   550.5 1654.29   564.4 1657.08   571.3 1658.94   588.6 1661.59   598.3 1663.64
#Mann= 4 ,-1 , 0
       0      .1       0    27.2     .05       0  255.01    .045       0
  294.24     .05       0
Bank Sta=255.01,294.24
XS Rating Curve= 0 ,0
Exp/Cntr=0.5,0.3

Type RM Length L Ch R = 1 ,13226   ,91.1,88.7,90
XS GIS Cut Line= 4
 2086361.9529492284927.9104631252086300.75490886285181.816779464
2086312.47371745285308.1186922042086345.02581769285616.712563217
#Sta/Elev= 30
       0 1651.69    16.2 1651.77    43.2  1651.2    56.7 1648.77    70.2 1647.92
   120.6 1646.81   141.1 1644.23   164.7 1642.52   195.1 1641.02   229.3 1639.71
   245.9 1638.27  290.451630.638   295.5 1630.11   302.1 1627.03     312 1626.48
   328.5 1626.62   338.2  1629.6  345.741630.727   377.4    1631   420.8  1630.5
   503.2 1633.54   516.4 1634.53   532.9 1637.04   571.5 1644.13   582.4 1644.95
   595.9 1643.53   602.2 1644.03   618.7 1649.31   668.2 1650.99   698.3 1652.14
#Mann= 9 ,-1 , 0
       0     .05       0    16.2    .055       0   164.7     .05       0
   195.1     .06       0  290.45    .045       0  345.74     .06       0
   377.4    .055       0   571.5     .06       0   668.2    .055       0
#XS Ineff= 2 , 0
          270.45  1643.7  365.74          1643.7
Permanent Ineff=
       F       F
Bank Sta=290.45,345.74
XS Rating Curve= 0 ,0
Exp/Cntr=0.5,0.3

Type RM Length L Ch R = 1 ,13138   ,389.2,407,418.9
XS GIS Cut Line= 4
2086292.20472911 284987.415593462086207.00509635 285136.24370788
2086233.04671094285399.2648353732086260.39048827285611.504240289
#Sta/Elev= 30
       0 1646.32    40.4 1643.84    55.1 1641.75   105.6 1642.24   153.6 1638.91
     192 1638.29     222 1637.05   271.4 1632.11  275.911630.765   281.3 1627.56
   304.4 1626.35     311 1626.62   320.9 1629.48  328.121630.186   353.9  1630.1
   373.6 1630.84   386.8 1632.17   396.9 1631.97   439.6 1633.77     459 1634.87
   485.9 1637.35   495.8 1638.78   522.3 1646.09   525.6 1647.65   528.9 1648.38
   548.7  1648.9   570.1 1656.04   581.8 1657.21   605.5 1657.84   649.8 1660.18
#Mann= 4 ,-1 , 0
       0     .06       0   153.6     .05       0  275.91    .045       0
  328.12     .05       0
Bank Sta=275.91,328.12
XS Rating Curve= 0 ,0
Exp/Cntr=0.5,0.3

Type RM Length L Ch R = 1 ,12731   ,293.6,305.1,306.9
XS GIS Cut Line= 3
2086290.03445786284983.075379044 2086096.8921276285080.731679797
2085608.61095193285460.505854622
#Sta/Elev= 30
       0 1646.34    20.6 1644.94    35.3 1641.17    57.6 1641.87      72 1640.91
    86.8 1641.28   101.5  1640.5   123.5 1638.59   152.7 1637.25   225.7 1637.66
   256.9  1637.2   323.9 1633.25   369.1 1632.31   405.7 1630.24   461.8 1629.87
   489.9 1628.69  520.811628.912   529.6 1626.77   543.7 1627.91  550.271629.349
   597.7 1632.11   639.2 1635.53   660.5  1638.2   722.4 1644.15   741.4 1646.83
   751.7 1645.42   770.4 1645.99   780.6 1647.94   797.2 1648.85     835 1652.47
#Mann= 4 ,-1 , 0
       0     .06       0   101.5     .05       0  520.81    .045       0
  550.27     .05       0
Bank Sta=520.81,550.27
XS Rating Curve= 0 ,0
Exp/Cntr=0.5,0.3

Type RM Length L Ch R = 1 ,12425   ,36.6,39.7,47.2
XS GIS Cut Line= 4
2086307.82969785284970.9225162122085840.81586811 285026.47817938
2085743.59362161285036.8948252052085425.88526753285012.589427635
#Sta/Elev= 30
       0 1648.36    16.6 1647.16    39.7 1645.23    52.9 1641.13    99.2  1641.4
   115.7 1640.28   198.3 1637.07   252.4 1638.99   303.3 1638.67   393.2 1630.47
  483.341629.097     489 1625.91   495.6 1624.59   515.4 1625.22   525.3 1628.11
  532.231628.864   597.8 1630.27   657.1 1634.97   703.1 1637.27   743.7 1643.03
   752.5 1644.99   768.9 1651.33   795.3 1653.07   801.8 1653.91   807.9 1655.97
   829.3 1661.55   844.6 1667.91   865.9 1674.85   877.5 1676.94   886.7 1676.89
#Mann= 6 ,-1 , 0
       0    .055       0    16.6     .06       0   115.7     .05       0
  483.34    .045       0  532.23     .05       0   807.9      .1       0
#XS Ineff= 2 , 0
          468.34  1630.9  547.23          1630.9
Permanent Ineff=
       F       F
Bank Sta=483.34,532.23
XS Rating Curve= 0 ,0
Exp/Cntr=0.5,0.3