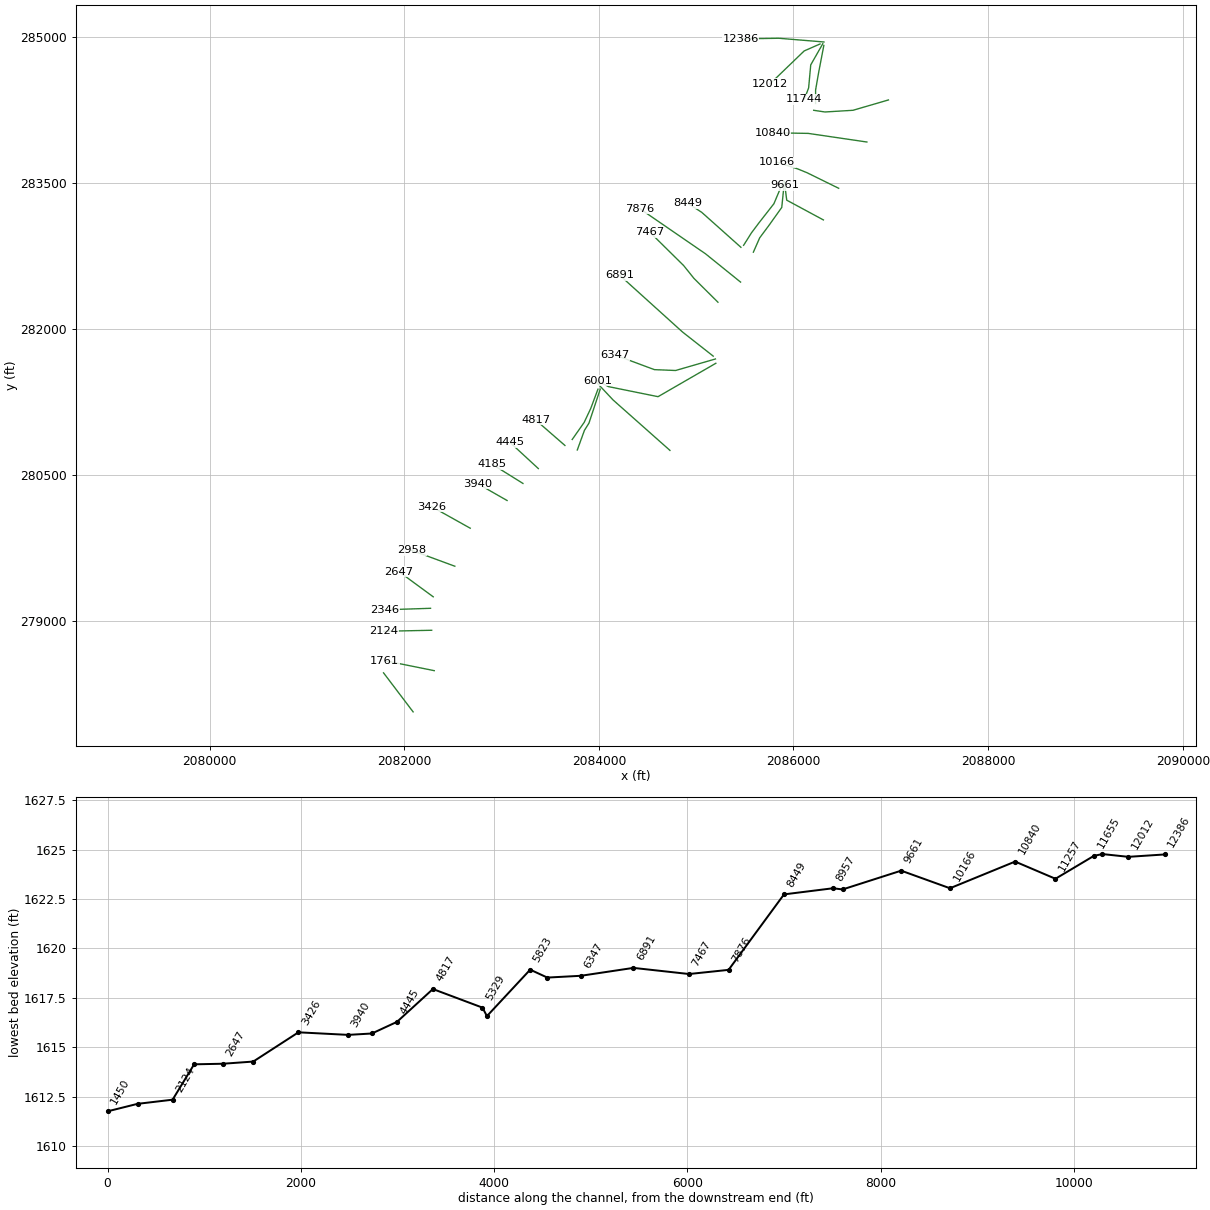
HEC-RAS study MILLCK1.prj: MILLCK1

--- MILLCK1.g01 (geometry) --- (continued)

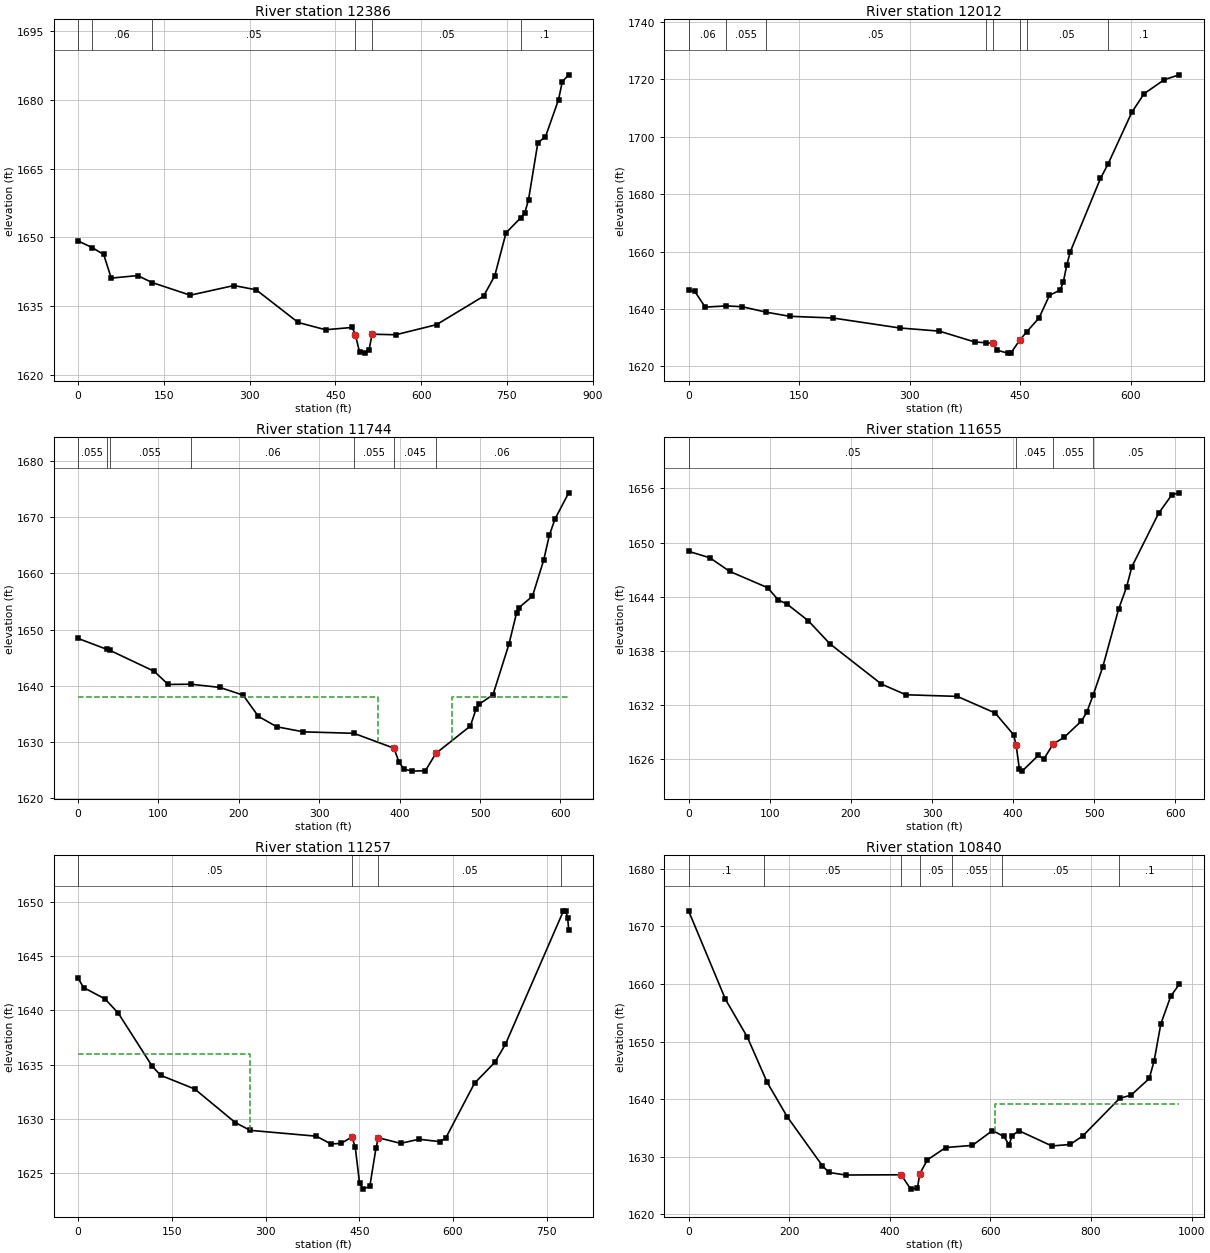
Type RM Length L Ch R = 1 ,12386   ,360.2,373.7,384.6
XS GIS Cut Line= 3
2086313.03802076284953.5616585462085849.49629694284991.756135955
2085456.70115077284985.245650291
#Sta/Elev= 30
       0 1649.22      25 1647.74    44.8 1646.26      58 1641.11   104.1 1641.66
   129.6 1640.14   196.2 1637.38   272.5 1639.49   311.4 1638.56     385 1631.43
   432.7 1629.85   479.3 1630.35  484.751628.812   492.4 1624.92   502.3 1624.75
   508.8 1625.46  514.22 1628.88   555.4 1628.75   626.9 1630.96     709 1637.15
   728.7 1641.63   748.4 1650.99   774.6 1654.32   781.2 1655.34   787.7  1658.2
   804.1 1670.68   817.3 1671.91   840.2 1680.02   846.8 1683.96     858 1685.44
#Mann= 6 ,-1 , 0
       0    .055       0      25     .06       0   129.6     .05       0
  484.75    .045       0  514.22     .05       0   774.6      .1       0
Bank Sta=484.75,514.22
XS Rating Curve= 0 ,0
Exp/Cntr=0.5,0.3

Type RM Length L Ch R = 1 ,12012   ,255.8,268.3,287.7
XS GIS Cut Line= 3
 2086272.6736002284933.1624211222086109.91309893284861.547734961
2085758.35048187284523.006089211
#Sta/Elev= 30
       0 1646.54     8.3 1646.18    22.6 1640.66    51.3 1641.09    72.8 1640.79
     105 1638.92   137.3 1637.46   195.6 1636.88   286.4  1633.4   340.4 1632.29
   388.2 1628.53   404.2 1628.22  413.661628.093   418.8 1625.65     433 1624.63
   437.8 1624.81  449.691629.224   458.8 1632.02   475.6 1636.87   489.8 1644.76
   504.4 1646.62   508.7 1649.52   513.4 1655.42     518 1659.91     559 1685.48
   569.2 1690.46   601.6 1708.55   618.2 1715.01   645.6  1719.9   665.9  1721.6
#Mann= 8 ,-1 , 0
       0     .06       0    51.3    .055       0     105     .05       0
   404.2      .1       0  413.66    .045       0  449.69      .1       0
   458.8     .05       0   569.2      .1       0
Bank Sta=413.66,449.69
XS Rating Curve= 0 ,0
Exp/Cntr=0.5,0.3

Type RM Length L Ch R = 1 ,11744   ,92.6,88.3,85.4
XS GIS Cut Line= 4
2086300.88515794284935.332364291 2086177.1872426284718.318362623
2086155.48584244284481.7732320432086112.08304211284366.756073624
#Sta/Elev= 30
       0 1648.42    35.7 1646.48    39.1 1646.33    94.7 1642.56     112 1640.22
   140.4 1640.26   176.4 1639.69   205.3 1638.31   224.3 1634.53   247.2 1632.67
   280.4 1631.77     343 1631.51  392.971628.856     399 1626.45   405.2 1625.13
   415.5 1624.77     432 1624.84  445.031627.925     488 1632.81   495.1 1635.87
   498.6 1636.67   516.1 1638.38   535.9 1647.37   545.4 1652.95   548.5 1653.92
   565.2 1655.94   579.2 1662.39   586.2  1666.8   593.2 1669.69   610.3 1674.37
#Mann= 7 ,-1 , 0
       0    .055       0    35.7     .05       0    39.1    .055       0
   140.4     .06       0     343    .055       0  392.97    .045       0
  445.03     .06       0
#XS Ineff= 2 , 0
           372.9    1638     465            1638
Permanent Ineff=
       F       F
Bank Sta=392.97,445.03
XS Rating Curve= 0 ,0
Exp/Cntr=0.5,0.3

Type RM Length L Ch R = 1 ,11655   ,420.2,398,365
XS GIS Cut Line= 4
2086311.73585802284917.9711785472086259.65262887284646.704004541
 2086227.1005286284460.071831882 2086227.1005286 284321.18300204
#Sta/Elev= 30
       0 1649.03    26.3 1648.31    50.6 1646.81    97.4    1645   110.8 1643.62
   120.8 1643.22   147.5 1641.34   174.2 1638.78   237.7 1634.32   267.8 1633.14
   331.1 1632.96   377.8 1631.12   400.5 1628.71  403.611627.569   407.7 1624.89
     411 1624.68     431 1626.42   437.7 1626.01  449.341627.693   462.8 1628.42
     484 1630.22   490.6 1631.18   498.5 1633.09   510.3 1636.19   529.9 1642.62
   539.8 1645.09   546.3 1647.33   579.2 1653.24   595.6  1655.3   604.6 1655.51
#Mann= 4 ,-1 , 0
       0     .05       0  403.61    .045       0  449.34    .055       0
   498.5     .05       0
Bank Sta=403.61,449.34
XS Rating Curve= 0 ,0
Exp/Cntr=0.5,0.3

Type RM Length L Ch R = 1 ,11257   ,408.8,417.2,400.8
XS GIS Cut Line= 4
2086975.79850626284358.0753167122086611.21524593284251.738587126
 2086322.5865581284234.3774013822086207.56939968284251.738587126
#Sta/Elev= 30
       0 1642.96     8.9  1642.1    43.1 1641.06    64.4 1639.74   118.3 1634.88
     132 1634.02   186.7 1632.75   251.5 1629.66   275.4 1628.94   381.4  1628.4
   404.4 1627.69   420.8 1627.73  438.251628.329   443.6 1627.37   450.4 1624.11
     456 1623.52   466.9 1623.78   476.7 1627.28  480.49 1628.26   516.2 1627.74
   545.6 1628.12   578.6  1627.9   588.5 1628.24   634.5 1633.29   666.8  1635.2
   683.9 1636.87   776.8 1649.18   780.6 1649.16   783.5 1648.53   785.2 1647.42
#Mann= 4 ,-1 , 0
       0     .05       0  438.25    .045       0  480.49     .05       0
  773.05     .06       0
#XS Ineff= 2 , 0
          275.27 1635.98
Permanent Ineff=
       F       F
Bank Sta=438.25,480.49
XS Rating Curve= 0 ,0
Exp/Cntr=0.3,0.1

Type RM Length L Ch R = 1 ,10840   ,650.7,674.1,664.4
XS GIS Cut Line= 3
2086754.44429019283925.7838584632086151.57968226284014.325348049
 2085785.6942592284020.835833713
#Sta/Elev= 30
       0 1672.69    73.4 1657.32   116.6 1650.81   156.3 1642.91   196.1 1636.95
   265.8 1628.47     279 1627.28   312.2 1626.84   422.6 1626.88   441.5 1624.39
   454.8 1624.55  459.711627.073   474.7 1629.47   511.2 1631.61   564.2 1631.98
     604 1634.55     627 1633.53   636.9 1632.08   643.4 1633.68   656.6 1634.53
   722.2 1631.88   758.3 1632.14   783.5 1633.61   856.7 1640.13   879.7 1640.71
   915.8 1643.59   925.6 1646.71   938.8 1653.08   958.5 1657.87   975.3 1659.94
#Mann= 7 ,-1 , 0
       0      .1       0  150.13     .05       0   422.6    .045       0
  459.71     .05       0  523.66    .055       0  623.14     .05       0
  856.52      .1       0
#XS Ineff= 2 , 0
                          608.94         1639.15
Permanent Ineff=
       F       F
Bank Sta=422.6,459.71
XS Rating Curve= 0 ,0
Exp/Cntr=0.3,0.1

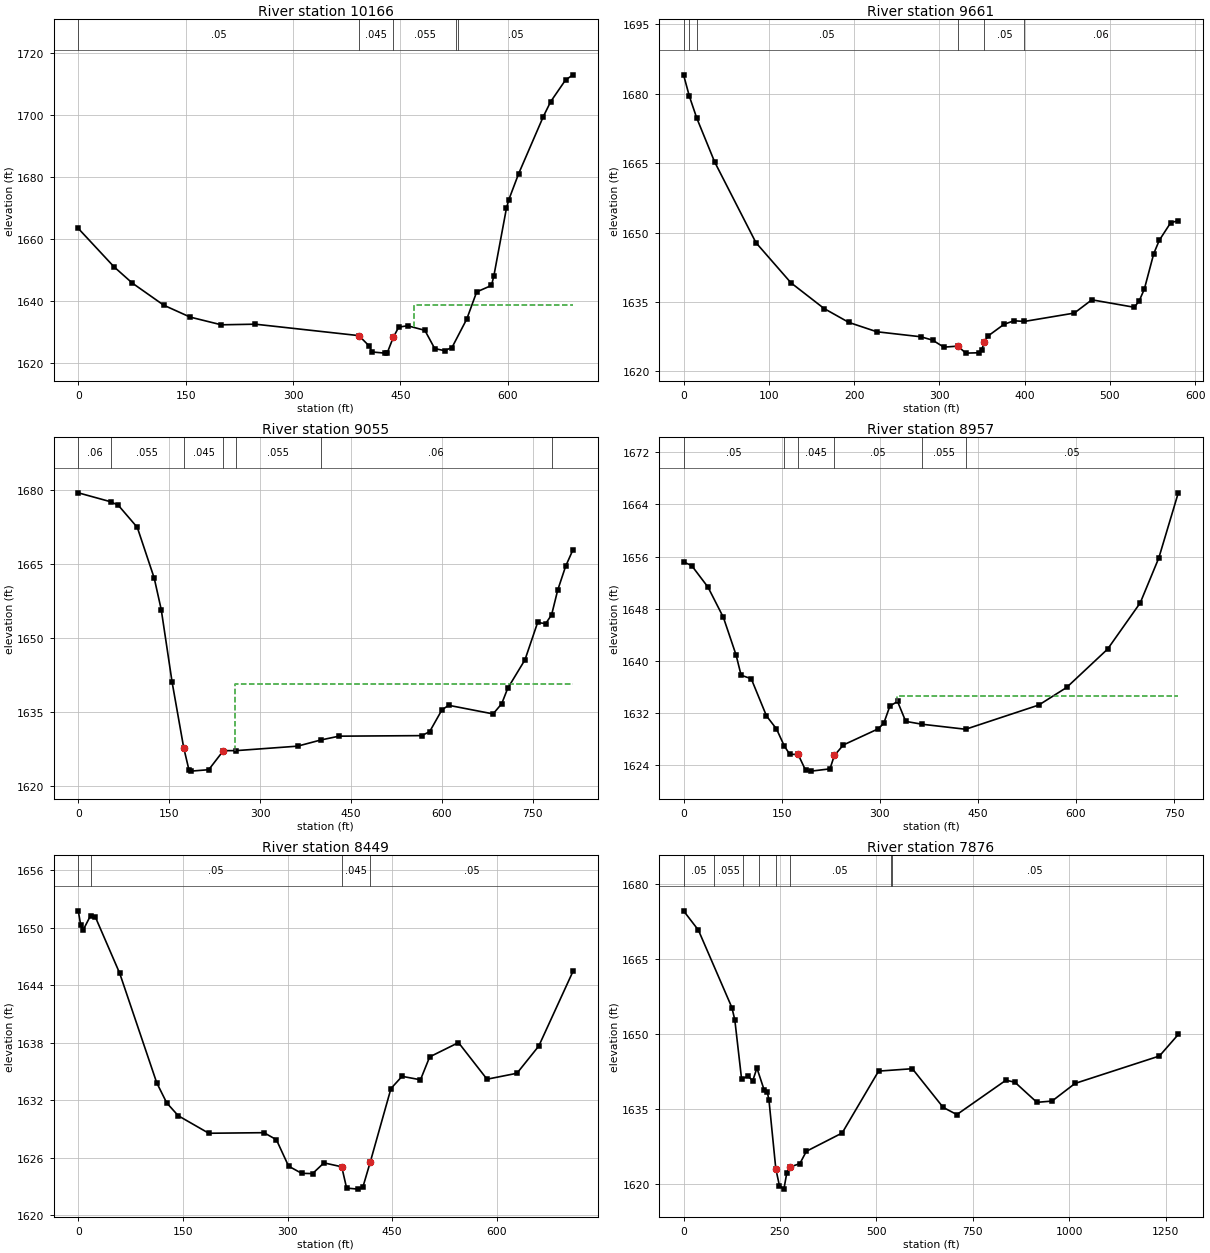
Type RM Length L Ch R = 1 ,10166   ,490.3,504.8,502.6
XS GIS Cut Line= 4
2086464.07971343283450.5233260392086141.16303644283609.377667129
2086046.11106119283648.4399249552085828.66300526 283718.75244838
#Sta/Elev= 30
       0 1663.29    49.9  1650.9    75.4 1645.66   119.4 1638.51   156.3 1634.67
   199.8 1632.18   247.3 1632.38  391.99 1628.69   406.8 1625.26   410.3 1623.42
   428.1 1623.04   431.6  1623.1  440.161628.163   447.7 1631.44   460.2 1631.87
   484.2  1630.4     498  1624.5   511.8 1623.84   522.1 1624.85   542.8 1634.06
   556.6  1642.8   577.3 1644.88   580.7 1648.08   598.2 1669.83   601.4  1672.5
   615.2 1680.94   649.7 1699.39     660 1704.21   680.7 1711.18   691.2 1712.86
#Mann= 5 ,-1 , 0
       0     .05       0  391.99    .045       0  440.16    .055       0
  527.27     .06       0  530.92     .05       0
#XS Ineff= 2 , 0
                          468.65         1638.72
Permanent Ineff=
       F       F
Bank Sta=391.99,440.16
XS Rating Curve= 0 ,0
Exp/Cntr=0.3,0.1

Type RM Length L Ch R = 1 ,9661    ,631.5,606.3,527.2
XS GIS Cut Line= 3
2086307.15679893283125.3064567892085930.42100385283328.431378633
 2085911.3236011283479.473071292
#Sta/Elev= 30
       0 1684.11     6.8 1679.48    15.5 1674.75    36.5 1665.26    84.9 1647.82
     126 1639.13   164.8 1633.58   193.9 1630.57   226.7 1628.55   278.2 1627.47
   292.1 1626.74   305.3 1625.22   321.71625.445     331 1623.93   346.5 1624.01
   349.7 1624.65  352.861626.335   357.1 1627.63   375.8 1630.15   387.6 1630.93
   399.7 1630.78   458.3 1632.59   478.9 1635.46   528.8 1633.84   534.6 1635.29
   540.5 1637.79   551.5 1645.44     558 1648.33   571.3 1652.11   580.3 1652.58
#Mann= 6 ,-1 , 0
       0      .1       0     6.8      .1       0    15.5     .05       0
   321.7    .045       0  352.86     .05       0   399.7     .06       0
Bank Sta=321.7,352.86
XS Rating Curve= 0 ,0
Exp/Cntr=0.5,0.3

Type RM Length L Ch R = 1 ,9055    ,98.4,98.5,98.6
XS GIS Cut Line= 5
2085587.77766028282794.2733262182085652.88186076282941.408858716
2085754.44432169283078.1274172962085879.44439977283253.908889875
 2085906.7881771283522.138012216
#Sta/Elev= 30
       0  1679.5    53.7 1677.68    66.2 1676.95    97.4 1672.48   125.3 1662.19
   136.9 1655.79   154.8 1641.09     1741627.726   182.6 1623.25   186.2 1622.98
   215.3 1623.27   239.51627.138   260.2 1627.14   361.9 1628.05   400.1  1629.3
   430.4 1630.08   567.1 1630.19     580 1631.02   600.1 1635.41   611.2 1636.35
   684.6  1634.6   698.8 1636.67   708.7 1639.79   737.2 1645.59   758.1 1653.17
   771.3 1652.93   781.2 1654.74   791.1 1659.69   804.3 1664.58   816.5 1667.96
#Mann= 7 ,-1 , 0
       0     .06       0    53.7    .055       0     174    .045       0
   239.5     .06       0   260.2    .055       0   400.1     .06       0
   781.2     .05       0
#XS Ineff= 2 , 0
             154  1640.7     259          1640.7
Permanent Ineff=
       F       F
Bank Sta=174,239.5
XS Rating Curve= 0 ,0
Exp/Cntr=0.5,0.3

Type RM Length L Ch R = 1 ,8957    ,474.4,507.4,541.3
XS GIS Cut Line= 5
2085487.51703402282864.585849628 2085566.9443686282990.888090461
2085645.06921235  283095.05454882085798.71523052283291.669313043
 2085887.2567201283501.304720551
#Sta/Elev= 30
       0 1655.16    12.4 1654.61    37.4 1651.29    60.9 1646.65    80.3 1640.88
      88 1637.77   103.5 1637.23   126.8 1631.52   142.1 1629.52   154.2 1626.87
   162.4 1625.63  175.241625.596   186.7 1623.15   195.2 1623.04   223.9 1623.39
  230.581625.442   244.4 1627.06     298 1629.55   306.3 1630.43   315.5 1633.03
   327.2 1633.74   339.7 1630.68   364.8 1630.24   431.3 1629.47   543.2 1633.19
   585.8 1635.89   648.4 1641.78   698.3 1648.88   726.7 1655.78   756.5 1665.78
#Mann= 6 ,-1 , 0
       0     .05       0   154.2    .055       0  175.24    .045       0
  230.58     .05       0   364.8    .055       0   431.3     .05       0
#XS Ineff= 2 , 0
                          326.82         1634.65
Permanent Ineff=
       F       F
Bank Sta=175.24,230.58
XS Rating Curve= 0 ,0
Exp/Cntr=0.5,0.3

Type RM Length L Ch R = 1 ,8449    ,568.3,573.5,577.1
XS GIS Cut Line= 3
 2085459.9347401282844.0563631212085057.15700236283203.431300551
2084914.79573852283295.445224121
#Sta/Elev= 30
       0 1651.77     3.6 1650.24       7 1649.77    17.6 1651.27    24.5 1651.12
    59.4 1645.25   112.5 1633.82   126.8 1631.73   143.3 1630.39   187.1 1628.56
   266.2 1628.62     284 1627.89   301.5 1625.13   320.2 1624.38   335.9 1624.35
   352.2 1625.47   377.7 1625.06   384.7 1622.84     401 1622.73   407.9 1622.91
  418.751625.592   448.3 1633.23   464.2  1634.5   490.6 1634.14   503.8 1636.53
   545.1 1638.02     586  1634.2   628.9 1634.82   660.2 1637.66   709.3 1645.46
#Mann= 4 ,-1 , 0
       0     .06       0   17.85     .05       0   377.7    .045       0
  418.75     .05       0
Bank Sta=377.7,418.75
XS Rating Curve= 0 ,0
Exp/Cntr=0.3,0.1

Type RM Length L Ch R = 1 ,7876    ,403.1,409,400.3
XS GIS Cut Line= 3
2085456.46263418282486.4173146342085095.74731003282777.592055887
2084420.34659402 283241.30647881
#Sta/Elev= 30
       0 1674.54    38.5 1670.68   125.3 1655.21   132.9 1652.74   150.5 1640.89
   167.1 1641.53   179.3 1640.54   190.2 1643.11   208.8 1638.78   217.2 1638.32
   221.5 1636.66  239.161623.007   248.5 1619.62   260.2 1618.91   267.8  1622.2
   275.21623.302   301.6 1624.02   318.4 1626.47   411.2 1630.13   505.7  1642.5
   593.2 1642.98   673.1 1635.25   708.6 1633.81   835.9 1640.68   859.1 1640.28
   916.2 1636.26   955.4 1636.51  1015.1 1640.04  1233.9 1645.52  1282.8 1649.83
#Mann= 8 ,-1 , 0
       0     .05       0   79.89    .055       0   154.4     .06       0
  195.07     .05       0  239.16    .045       0   275.2     .05       0
  537.25    .055       0  539.88     .05       0
Bank Sta=239.16,275.2
XS Rating Curve= 0 ,0
Exp/Cntr=0.3,0.1

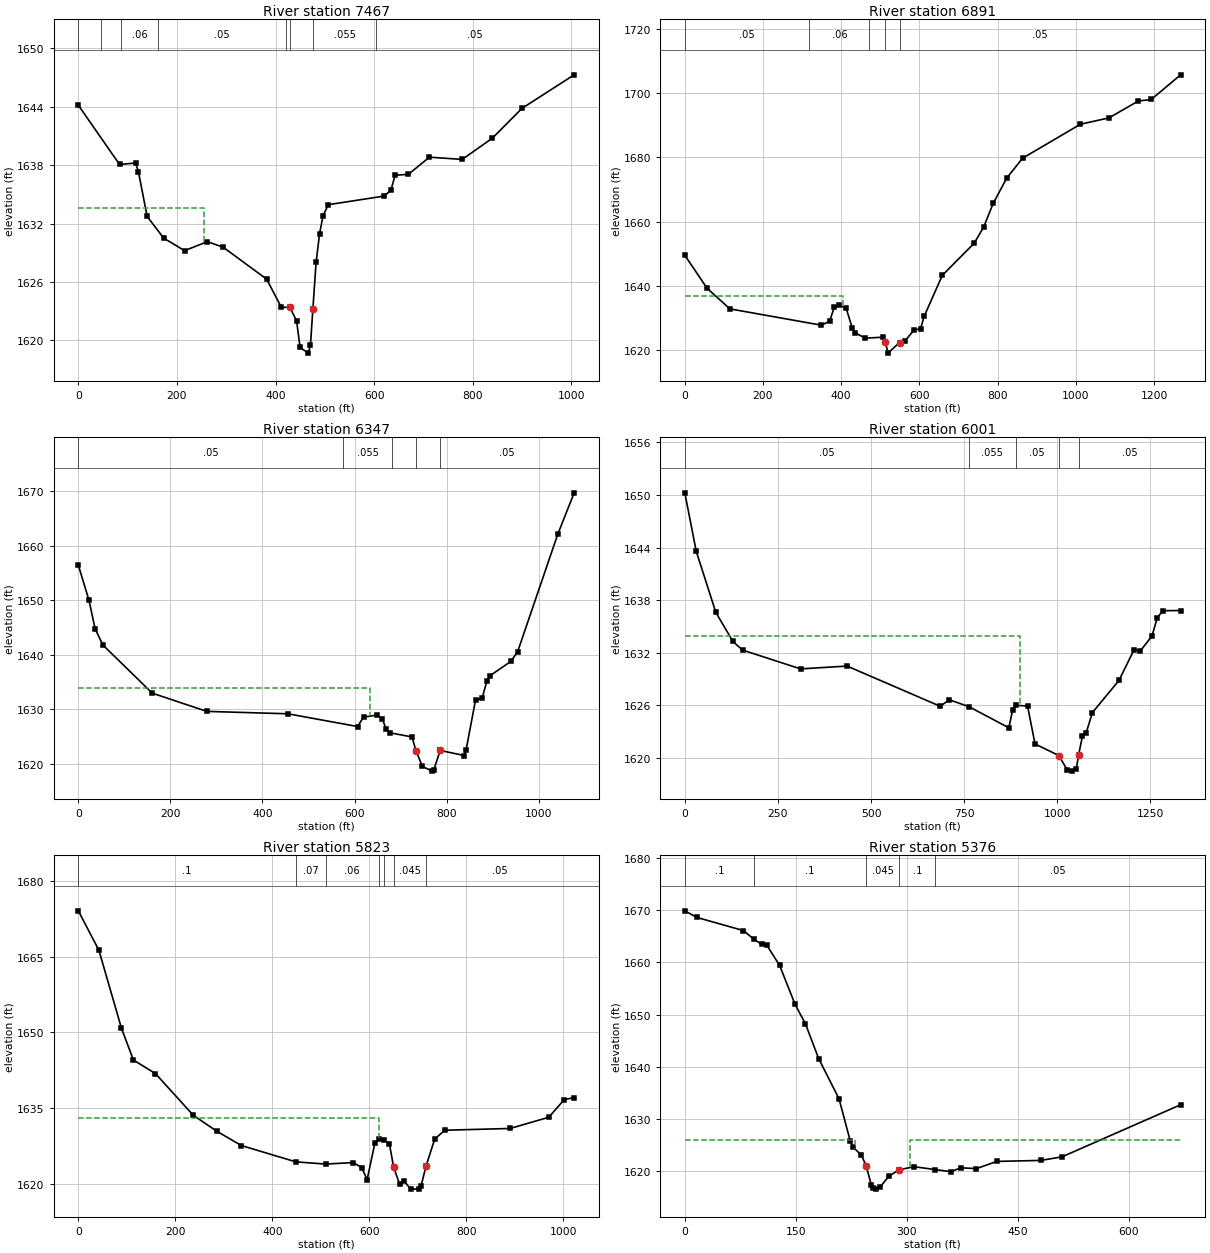
Type RM Length L Ch R = 1 ,7467    ,563.9,575.5,575.6
XS GIS Cut Line= 4
2085223.82366377282279.8202868852084977.29594162282524.611792043
 2084871.3929382282656.5564100442084523.20424818283000.216494336
#Sta/Elev= 30
       0 1644.17    83.6 1638.08   116.2 1638.23     122 1637.32   139.5 1632.75
     173 1630.52   215.5 1629.23   261.8 1630.15   294.1 1629.57     382  1626.3
     412 1623.39  428.761623.425   442.7 1622.03   449.8 1619.28   466.6  1618.7
   470.9 1619.53  475.781623.226   482.3 1628.02   489.3 1630.94   496.3 1632.81
   507.1 1633.95   619.9 1634.83   633.9 1635.41   642.6 1636.97   669.6 1637.07
   712.2 1638.83   778.7  1638.6   839.8 1640.78   900.1 1643.85  1005.8 1647.29
#Mann= 8 ,-1 , 0
       0     .05       0   44.98    .055       0   87.33     .06       0
  160.66     .05       0  421.62    .055       0  428.76    .045       0
  475.78    .055       0  604.05     .05       0
#XS Ineff= 2 , 0
          254.77 1633.58
Permanent Ineff=
       F       F
Bank Sta=428.76,475.78
XS Rating Curve= 0 ,0
Exp/Cntr=0.3,0.1

Type RM Length L Ch R = 1 ,6891    ,533.8,544.6,553.3
XS GIS Cut Line= 3
2085175.21254054281726.0008564592084859.24040344281974.264795631
2084216.42818825282555.150530929
#Sta/Elev= 30
       0 1649.52    57.1 1639.21   115.5  1632.8   349.4 1627.72   370.5 1628.97
   382.2 1633.32   395.5 1633.88   412.8 1632.97   428.7 1626.69     435 1625.42
   461.2 1623.67   505.7 1623.97  513.311622.381   519.7 1619.01  549.371622.323
   563.7 1622.87   586.7  1626.3   602.9 1626.55   612.2 1630.49   658.7 1643.27
   740.1 1653.26   764.4 1658.31   788.8  1665.7   823.6  1673.6   863.9 1679.77
  1011.8 1690.36    1085 1692.35  1160.2 1697.62    1193 1698.08  1268.2 1705.77
#Mann= 5 ,-1 , 0
       0     .05       0  318.44     .06       0   472.2     .05       0
  513.31    .045       0  549.37     .05       0
#XS Ineff= 2 , 0
          404.77 1636.72
Permanent Ineff=
       F       F
Bank Sta=513.31,549.37
XS Rating Curve= 0 ,0
Exp/Cntr=0.3,0.1

Type RM Length L Ch R = 1 ,6347    ,328.4,345.9,342.6
XS GIS Cut Line= 4
 2085197.9427566281696.6194776822084788.60929784281578.313972049
2084571.04576987281587.1120266322084164.79592618281738.153719291
#Sta/Elev= 30
       0 1656.44      23 1650.02    36.6 1644.71    53.7 1641.74   160.6 1632.93
   279.1 1629.58   455.5 1629.14   606.6  1626.8   619.7 1628.53   649.6 1628.91
   660.1 1628.26   668.7 1626.36   677.6 1625.64   724.8 1624.89   733.6 1622.35
   747.6 1619.46   768.6 1618.61   772.1  1618.8   786.1  1622.4   786.1 1622.41
   838.6 1621.47   842.4  1622.5   863.1 1631.75   877.1 1631.95   887.6 1635.17
   894.6 1636.15   940.1 1638.78   954.5 1640.57  1041.6 1662.12  1077.2 1669.72
#Mann= 5 ,-1 , 0
       0     .05       0  575.41    .055       0  680.79     .05       0
   733.6    .045       0   786.1     .05       0
#XS Ineff= 2 , 0
          632.94 1633.84
Permanent Ineff=
       F       F
Bank Sta=733.6,786.1
XS Rating Curve= 0 ,0
Exp/Cntr=0.3,0.1

Type RM Length L Ch R = 1 ,6001    ,193.8,177.5,158.9
XS GIS Cut Line= 4
2085202.10715245281652.3887320682084608.42380056281309.371684315
2084098.29588339281412.7165640872083988.35452193281472.084899275
#Sta/Elev= 30
       0 1650.23    30.7 1643.57    83.3 1636.61   129.2 1633.29   155.3 1632.31
   310.7 1630.17   435.7 1630.49   685.7 1625.91   710.1 1626.65     763 1625.86
   869.9 1623.46   879.9 1625.44   888.3 1626.01   920.1 1625.95   940.2 1621.62
  1003.8  1620.3  1026.9 1618.66  1040.6 1618.52  1050.7 1618.71  1057.4 1620.41
  1067.4 1622.47  1077.4 1622.86  1094.2 1625.19  1165.5 1628.85  1206.1 1632.35
  1222.6  1632.2  1254.1 1633.91  1268.6 1636.02  1283.8  1636.8  1331.1 1636.82
#Mann= 5 ,-1 , 0
       0     .05       0     763    .055       0   888.3     .05       0
  1003.8    .045       0  1057.4     .05       0
#XS Ineff= 2 , 0
          900.18 1633.87
Permanent Ineff=
       F       F
Bank Sta=1003.8,1057.4
XS Rating Curve= 0 ,0
Exp/Cntr(USF)=0,0
Exp/Cntr=0.3,0.1

Type RM Length L Ch R = 1 ,5823    ,473.2,447.4,404.6
XS GIS Cut Line= 4
2084730.59827226280757.4398014552084261.37119237281173.568562374
2084147.43474045281274.6119954592083980.76807901 281451.69530271
#Sta/Elev= 30
       0 1674.11    42.4  1666.3    88.9 1650.84   113.6 1644.52   159.1 1641.83
   237.2 1633.55   286.3 1630.36   336.1 1627.57   448.5 1624.33   509.9 1623.89
   566.9 1624.18   584.5  1623.2   595.6 1620.81   611.8 1628.14   619.5  1628.8
   630.4 1628.71   641.5 1627.96   650.2  1623.3   662.5 1619.92   672.4 1620.49
   685.3 1618.94     702 1618.92     707  1619.6   716.9 1623.42     735 1628.86
   755.9  1630.6   890.6 1630.95   970.2 1633.17    1002 1636.66  1022.6 1637.08
#Mann= 7 ,-1 , 0
       0      .1       0   448.5     .07       0   509.9     .06       0
   619.5    .055       0   630.4     .05       0   650.2    .045       0
   716.9     .05       0
#XS Ineff= 2 , 0
          620.05 1632.95
Permanent Ineff=
       F       F
Bank Sta=650.2,716.9
XS Rating Curve= 0 ,0
Exp/Cntr=0.5,0.3

Type RM Length L Ch R = 1 ,5376    ,47.7,46.7,46.4
XS GIS Cut Line= 4
2083778.74978226280761.6563284552083851.66663119280962.176924795
2083898.54153743281037.6977711322084014.42680436281386.656062707
#Sta/Elev= 30
       0 1669.87    16.4  1668.6    79.2 1666.09    93.5 1664.42   103.8 1663.46
   110.6 1663.33   128.1 1659.42     149 1651.95     163 1648.23   180.9 1641.56
   208.4 1633.86   223.4 1625.87   227.2 1624.63   238.7 1623.07  245.111620.998
   251.9 1617.43   254.3 1616.72     258 1616.57   263.9 1616.98   275.8 1619.04
  289.551620.282   309.7 1620.86   338.7 1620.31     359 1619.92   373.3 1620.65
     394  1620.5   421.7 1621.88     481 1622.07   509.6 1622.75   669.9 1632.73
#Mann= 5 ,-1 , 0
       0      .1       0    93.5      .1       0  245.11    .045       0
  289.55      .1       0   338.7     .05       0
#XS Ineff= 2 , 0
           230.1  1625.9  304.55          1625.9
Permanent Ineff=
       F       F
Bank Sta=245.11,289.55
XS Rating Curve= 0 ,0
Exp/Cntr=0.5,0.3

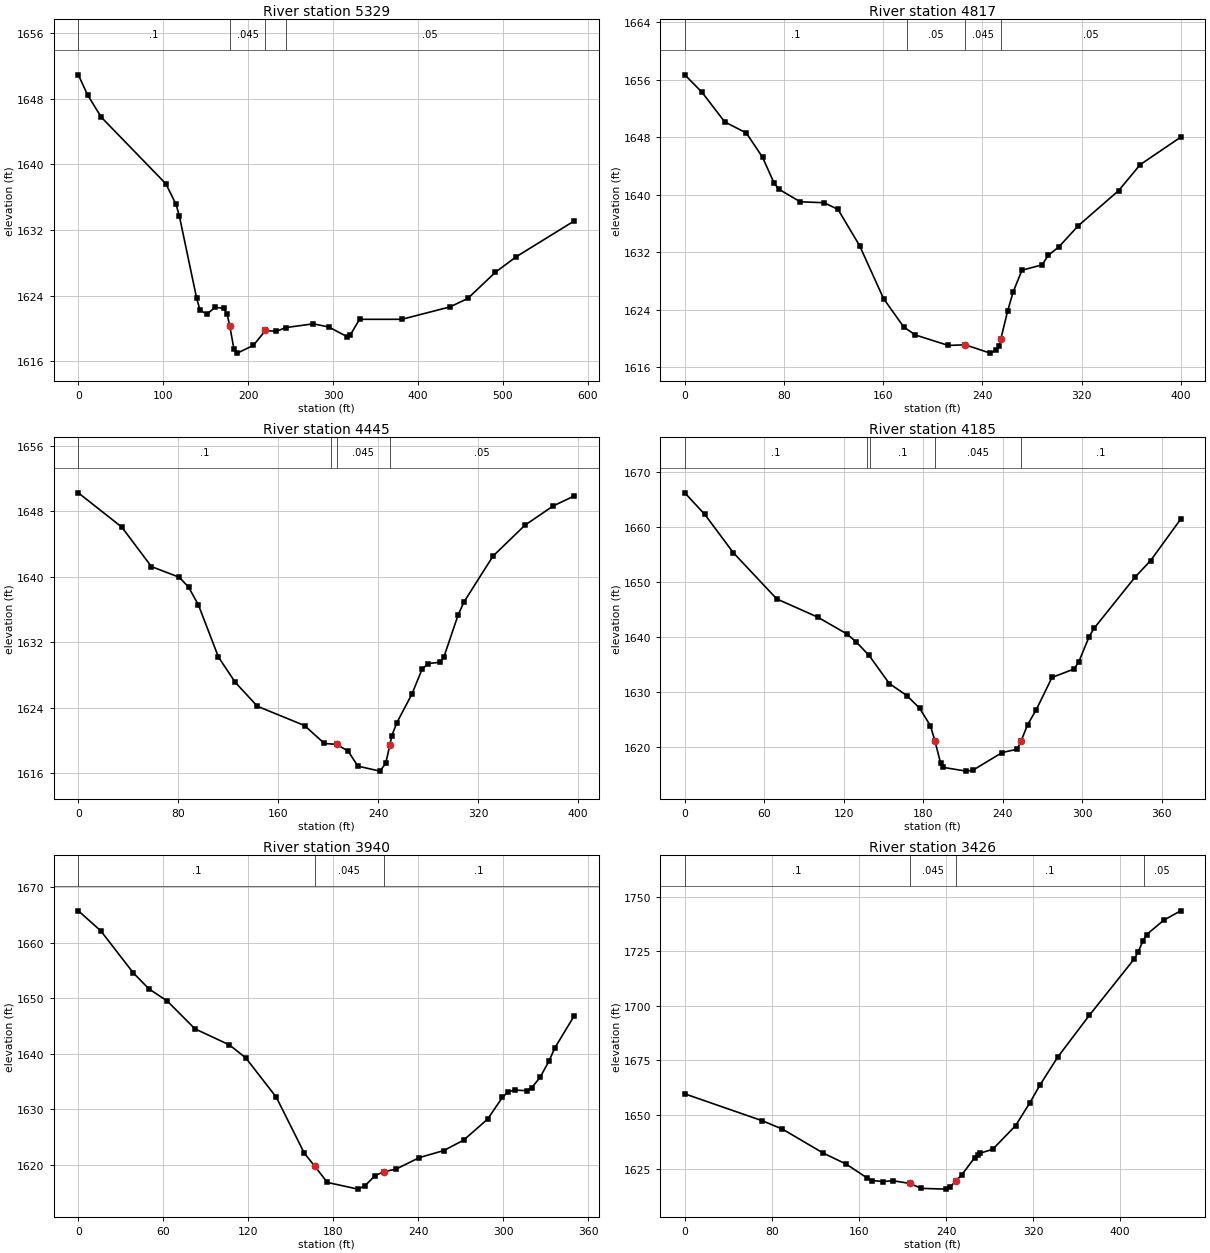
Type RM Length L Ch R = 1 ,5329    ,477.9,512.4,529.5
XS GIS Cut Line= 4
2083726.66655311280869.7289469542083849.32280385281044.989423215
2083916.38008446 281186.829690712083991.24968535281386.482506633
#Sta/Elev= 30
       0 1650.91      11 1648.44      27 1645.75   103.1 1637.63   115.1 1635.12
   119.1 1633.65   139.2 1623.76   143.2 1622.28   151.2 1621.73   161.3  1622.6
   171.2 1622.44   175.2 1621.77  178.261620.343   183.2 1617.56   187.2    1617
   206.1 1617.94  220.451619.758   233.3 1619.65   244.1 1620.11   276.8 1620.57
     295 1620.18   316.7    1619   320.4 1619.22   331.2 1621.12     381 1621.12
   437.7 1622.63   458.7 1623.66   491.3 1626.86     516 1628.76     584  1633.1
#Mann= 4 ,-1 , 0
       0      .1       0  178.26    .045       0  220.45      .1       0
   244.1     .05       0
Bank Sta=178.26,220.45
XS Rating Curve= 0 ,0
Exp/Cntr=0.5,0.3

Type RM Length L Ch R = 1 ,4817    ,370.1,371.2,371.3
XS GIS Cut Line= 2
2083651.62306803280808.1404874622083349.97373694281070.727232635
#Sta/Elev= 30
       0 1656.67    13.8 1654.26    32.2 1650.12    49.6 1648.58    62.7  1645.2
    71.9 1641.65    75.7 1640.77    93.1    1639   112.5 1638.87   123.6 1637.93
     141 1632.89   160.3 1625.53   176.6 1621.57   185.9 1620.47   212.5 1619.01
  226.191619.097   246.3 1617.94     251 1618.32   253.3 1618.97  254.871619.879
   260.3 1623.76   264.9 1626.49   271.9 1629.47   288.2 1630.23   293.2 1631.56
   301.9 1632.76   317.4 1635.68   349.8 1640.54   367.3 1644.17   399.9 1647.99
#Mann= 4 ,-1 , 0
       0      .1       0  179.37     .05       0  226.19    .045       0
  254.87     .05       0
Bank Sta=226.19,254.87
XS Rating Curve= 0 ,0
Exp/Cntr=0.3,0.1

Type RM Length L Ch R = 1 ,4445    ,256.4,260.2,268.8
XS GIS Cut Line= 2
2083378.33030751280570.7997547982083086.66356802280839.896985635
#Sta/Elev= 30
       0 1650.27    34.8 1646.08    58.5 1641.26    80.8 1639.96    88.2 1638.76
    96.1 1636.58   112.1 1630.22   125.5 1627.14   143.3  1624.2     181 1621.85
   196.9 1619.66  206.621619.549   215.9 1618.73   223.7 1616.89   241.3 1616.28
     246 1617.23  249.261619.446   250.9 1620.61   254.9  1622.2   266.9 1625.67
   275.1 1628.73     280 1629.42   289.6 1629.58   292.5  1630.2     304 1635.38
   308.7 1636.96   331.9 1642.55   357.4 1646.31   379.9 1648.66   396.8 1649.88
#Mann= 4 ,-1 , 0
       0      .1       0  202.44     .05       0  206.62    .045       0
  249.26     .05       0
Bank Sta=206.62,249.26
XS Rating Curve= 0 ,0
Exp/Cntr=0.3,0.1

Type RM Length L Ch R = 1 ,4185    ,243,244.9,243.5
XS GIS Cut Line= 2
2083220.34407493280418.0218451322082902.63572085280615.938444048
#Sta/Elev= 30
       0 1666.25    15.1 1662.32    36.6 1655.38    69.4 1646.98   100.3 1643.67
   122.4 1640.61   129.5 1639.13   139.1 1636.71   154.4  1631.6   167.6 1629.42
   177.2 1627.14   185.4 1623.95  188.781621.217   193.1 1617.15     195 1616.37
   212.4 1615.69   217.6 1615.87   239.5 1619.06   250.9 1619.67  253.88 1621.17
   258.8 1624.14   265.3 1626.83   277.2 1632.71   293.9 1634.25   297.5  1635.6
   305.2 1640.09     309 1641.65     340 1650.96   351.6 1653.93   374.3 1661.45
#Mann= 5 ,-1 , 0
       0      .1       0  137.29     .05       0  139.74      .1       0
  188.78    .045       0  253.88      .1       0
Bank Sta=188.78,253.88
XS Rating Curve= 0 ,0
Exp/Cntr=0.3,0.1

Type RM Length L Ch R = 1 ,3940    ,513.6,514.8,511.3
XS GIS Cut Line= 2
2083057.14984754280242.674754873 2082753.3302452280416.285956204
#Sta/Elev= 30
       0 1665.73    15.9 1662.11    38.9 1654.52    49.9 1651.66    62.7  1649.5
    82.3 1644.48   106.6 1641.59   118.2 1639.24   139.7 1632.17   159.5 1622.08
  166.791619.765   175.7 1616.83   197.3 1615.62   202.2  1616.2   209.4 1618.05
  215.841618.777     224  1619.2   240.7  1621.3   257.8 1622.56   271.9 1624.44
   288.8 1628.22   299.3 1632.15   303.2 1633.14     308 1633.46   316.6 1633.34
     320  1633.9   325.8 1635.72   332.1 1638.66   336.4  1641.1   349.9 1646.81
#Mann= 3 ,-1 , 0
       0      .1       0  166.79    .045       0  215.84      .1       0
Bank Sta=166.79,215.84
XS Rating Curve= 0 ,0
Exp/Cntr=0.3,0.1

Type RM Length L Ch R = 1 ,3426    ,462.3,467.5,469.8
XS GIS Cut Line= 2
2082678.67750737279957.9525552992082281.10809252  280180.1745518
#Sta/Elev= 30
       0  1659.5    71.2 1647.15    89.7 1643.31   127.2 1632.29   148.3 1627.24
   167.6 1620.84   172.3 1619.71   182.1 1619.22   191.1 1619.62  206.431618.378
   217.4  1616.1   239.9 1615.75   243.8 1616.74  249.031619.542   254.4 1622.26
   266.4 1630.27   268.9 1631.45   271.3 1632.24   282.9 1634.06   303.9 1644.91
   317.1  1655.5   326.4 1663.67   342.5 1676.31   371.5 1695.49   412.9 1721.46
   416.6 1724.74   420.7  1729.6   424.2 1732.64     440 1739.25   455.5 1743.56
#Mann= 4 ,-1 , 0
       0      .1       0  206.43    .045       0  249.03      .1       0
  421.82     .05       0
Bank Sta=206.43,249.03
XS Rating Curve= 0 ,0
Exp/Cntr=0.3,0.1

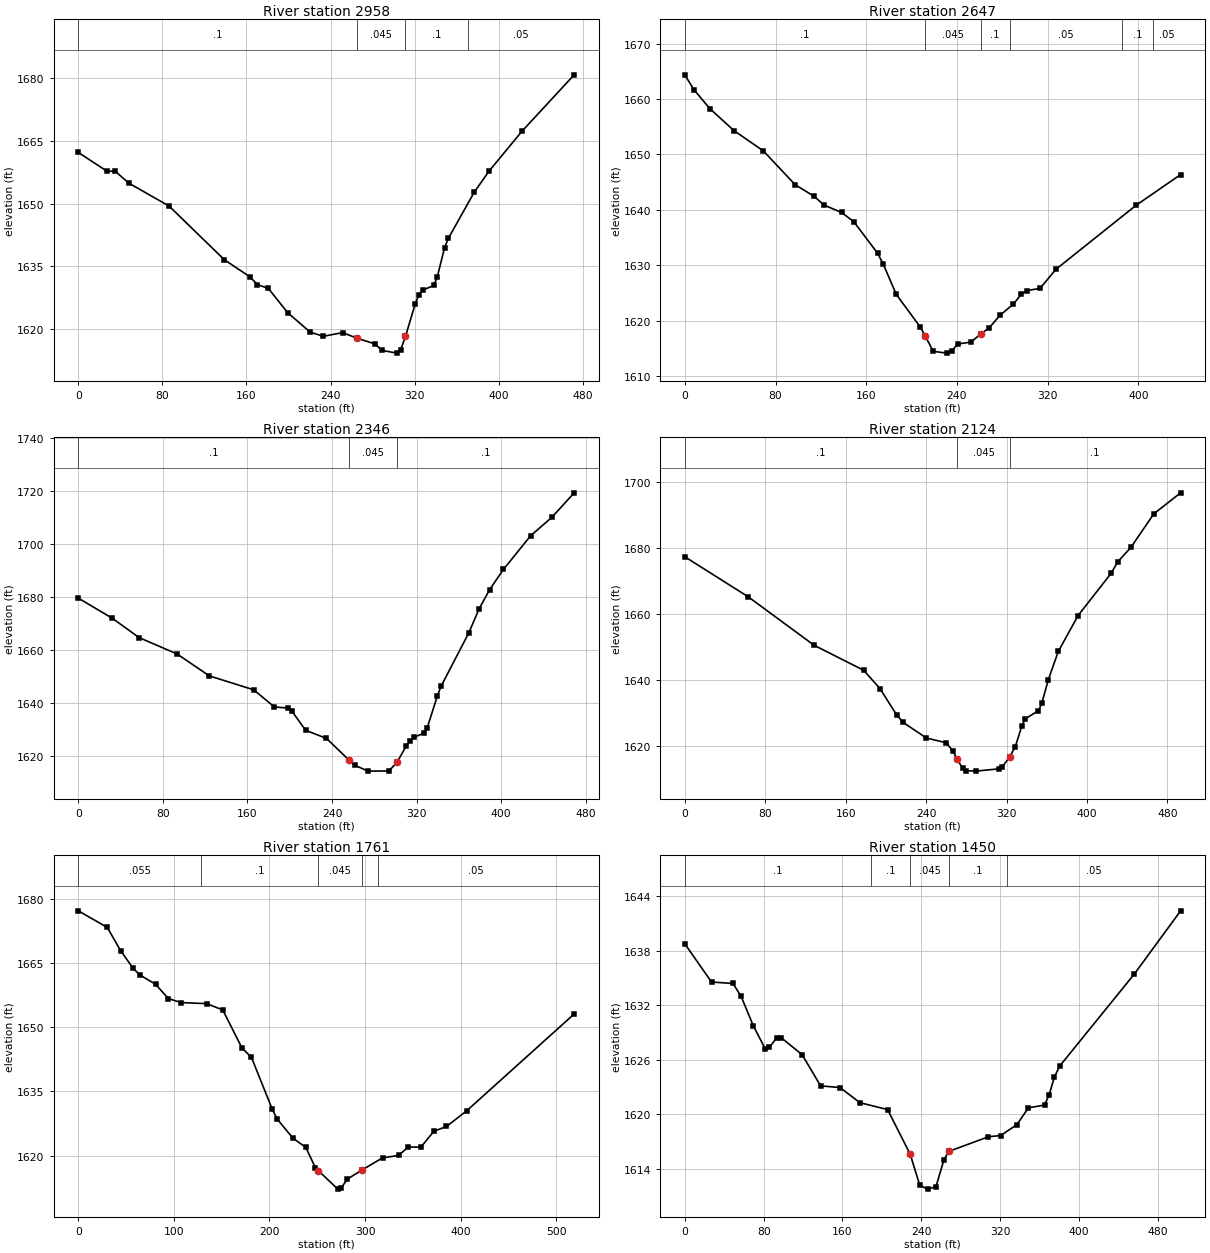
Type RM Length L Ch R = 1 ,2958    ,317.3,311.3,303.9
XS GIS Cut Line= 2
2082520.69127476  279567.32735232082077.98317069279730.521907792
#Sta/Elev= 30
       0 1662.22    26.9  1657.8    35.3 1657.69    47.9 1654.91    86.4  1649.4
     139 1636.57   163.3  1632.5   170.3 1630.65   180.8 1629.74   199.2 1623.93
   220.8 1619.25   233.2  1618.3   251.5 1619.17   265.41617.816   281.9  1616.5
   289.2 1614.91   303.2 1614.27   306.7 1615.06  311.281618.258   320.6 1626.06
   324.1 1628.27   327.6 1629.32   338.3 1630.44   341.6 1632.53   348.5 1639.47
   352.1  1641.7   376.6 1652.68   390.6 1657.69     422 1667.25   471.8 1680.77
#Mann= 4 ,-1 , 0
       0      .1       0   265.4    .045       0  311.28      .1       0
  370.92     .05       0
Bank Sta=265.4,311.28
XS Rating Curve= 0 ,0
Exp/Cntr=0.3,0.1

Type RM Length L Ch R = 1 ,2647    ,282.9,300.5,314.2
XS GIS Cut Line= 2
2082298.46927828279253.091432214 2081946.0385527279511.772017211
#Sta/Elev= 30
       0 1664.36       8 1661.69    22.2 1658.24    43.3 1654.31    69.3 1650.63
    97.3 1644.54   113.8 1642.47   123.1 1640.84   138.2 1639.53     149 1637.88
   170.1 1632.15   174.9 1630.25   186.5 1624.74   207.4 1618.93  212.061617.242
     219 1614.48   231.1 1614.16   235.7  1614.6   240.5  1615.8   252.2 1616.15
     2611617.608   268.5 1618.74     278    1621   289.8 1623.01   296.8 1624.81
   301.5 1625.43   313.3 1625.85   327.3 1629.29   397.7 1640.79   437.2 1646.37
#Mann= 6 ,-1 , 0
       0      .1       0  212.06    .045       0     261      .1       0
  286.36     .05       0  385.92      .1       0  412.57     .05       0
Bank Sta=212.06,261
XS Rating Curve= 0 ,0
Exp/Cntr=0.3,0.1

Type RM Length L Ch R = 1 ,2346    ,223.1,222.7,223
XS GIS Cut Line= 2
2082270.69144669279135.0358940512081801.94139993279119.410925299
#Sta/Elev= 30
       0 1679.59    31.8 1672.06    57.4 1664.68    93.6 1658.41   123.9 1650.17
   165.8 1644.91   185.5  1638.4   198.6 1637.98   201.9 1636.89     215 1629.59
   234.7 1626.51  255.821618.421   261.4 1616.35   274.1 1614.13   293.8  1614.2
  301.74 1617.62   310.2  1623.7   313.5 1625.36   317.7 1626.95   326.6 1628.46
   329.9 1630.39   339.5 1642.44   343.1 1646.24   369.3 1666.41   379.1 1675.56
     389 1682.77   402.1 1690.45   427.8  1703.2     448  1710.2     469 1719.44
#Mann= 3 ,-1 , 0
       0      .1       0  255.82    .045       0  301.74      .1       0
Bank Sta=255.82,301.74
XS Rating Curve= 0 ,0
Exp/Cntr=0.3,0.1

Type RM Length L Ch R = 1 ,2124    ,366.2,362.8,356.9
XS GIS Cut Line= 2
2082282.84430951278909.3414635512081789.78853711278898.924817711
#Sta/Elev= 30
       0 1677.24      63 1665.14   128.6 1650.45   177.9 1642.88   194.3 1637.28
   210.7 1629.37   217.2  1627.1   240.2 1622.38   260.1 1620.92   266.5  1618.5
  271.081615.887   276.3  1613.2   279.6  1612.5   289.4 1612.34   312.4 1613.03
   315.7 1613.55  323.331616.752   328.8 1619.78   335.4 1626.13   338.7 1628.19
   351.8 1630.63   355.1 1632.86   361.6 1640.03   371.5 1648.56   391.2 1659.45
     424 1672.21   430.7 1675.73   443.7 1680.06   466.6 1690.27   493.2  1696.6
#Mann= 3 ,-1 , 0
       0      .1       0  271.08    .045       0  323.33      .1       0
Bank Sta=271.08,323.33
XS Rating Curve= 0 ,0
Exp/Cntr=0.3,0.1

Type RM Length L Ch R = 1 ,1761    ,321.9,310.6,292.6
XS GIS Cut Line= 2
 2082308.8859241278494.4108629672081800.20518294278596.841432378
#Sta/Elev= 30
       0 1677.28    30.3 1673.39    44.3 1667.93    57.4 1663.82    64.1 1662.31
    80.8 1660.09    94.2 1656.75   107.6  1655.8   134.3 1655.55   151.1 1654.09
   171.2  1645.2   181.2 1642.96     203  1630.8     208 1628.54   224.7 1624.05
   238.1 1621.89   248.1 1617.14  251.291616.418   271.6 1612.13   274.9 1612.34
   281.6  1614.5  296.981616.614   318.4 1619.46   335.1 1620.01   345.2 1621.97
   358.6 1621.98     372 1625.66   385.3  1626.8   406.4 1630.46   518.9 1653.13
#Mann= 5 ,-1 , 0
       0    .055       0  128.51      .1       0  251.29    .045       0
  296.98      .1       0  313.45     .05       0
Bank Sta=251.29,296.98
XS Rating Curve= 0 ,0
Exp/Cntr=0.3,0.1

Type RM Length L Ch R = 1 ,1450    ,250.4,258.4,265
XS GIS Cut Line= 2
2082091.87192243278070.7998335512081788.05264819278471.841354296
#Sta/Elev= 30
       0 1638.77    27.1 1634.56    48.9  1634.4    57.1 1632.99    69.4 1629.77
    81.6  1627.2    85.9 1627.36    93.3 1628.43      98 1628.41   119.1 1626.55
   137.8 1623.12   157.5 1622.94   177.7 1621.27   205.8 1620.51   228.7 1615.59
   238.5 1612.15   246.4 1611.75   254.9 1612.03   262.9 1614.97   267.91615.904
   308.1 1617.52   320.4 1617.65   336.9 1618.84   348.6  1620.7     365 1621.01
   369.7 1622.14   374.9 1624.06   380.3 1625.29   456.2 1635.45   503.1  1642.4
#Mann= 5 ,-1 , 0
       0      .1       0  189.23      .1       0   228.7    .045       0
   267.9      .1       0  326.48     .05       0
Bank Sta=228.7,267.9
XS Rating Curve= 0 ,0
Exp/Cntr=0.3,0.1