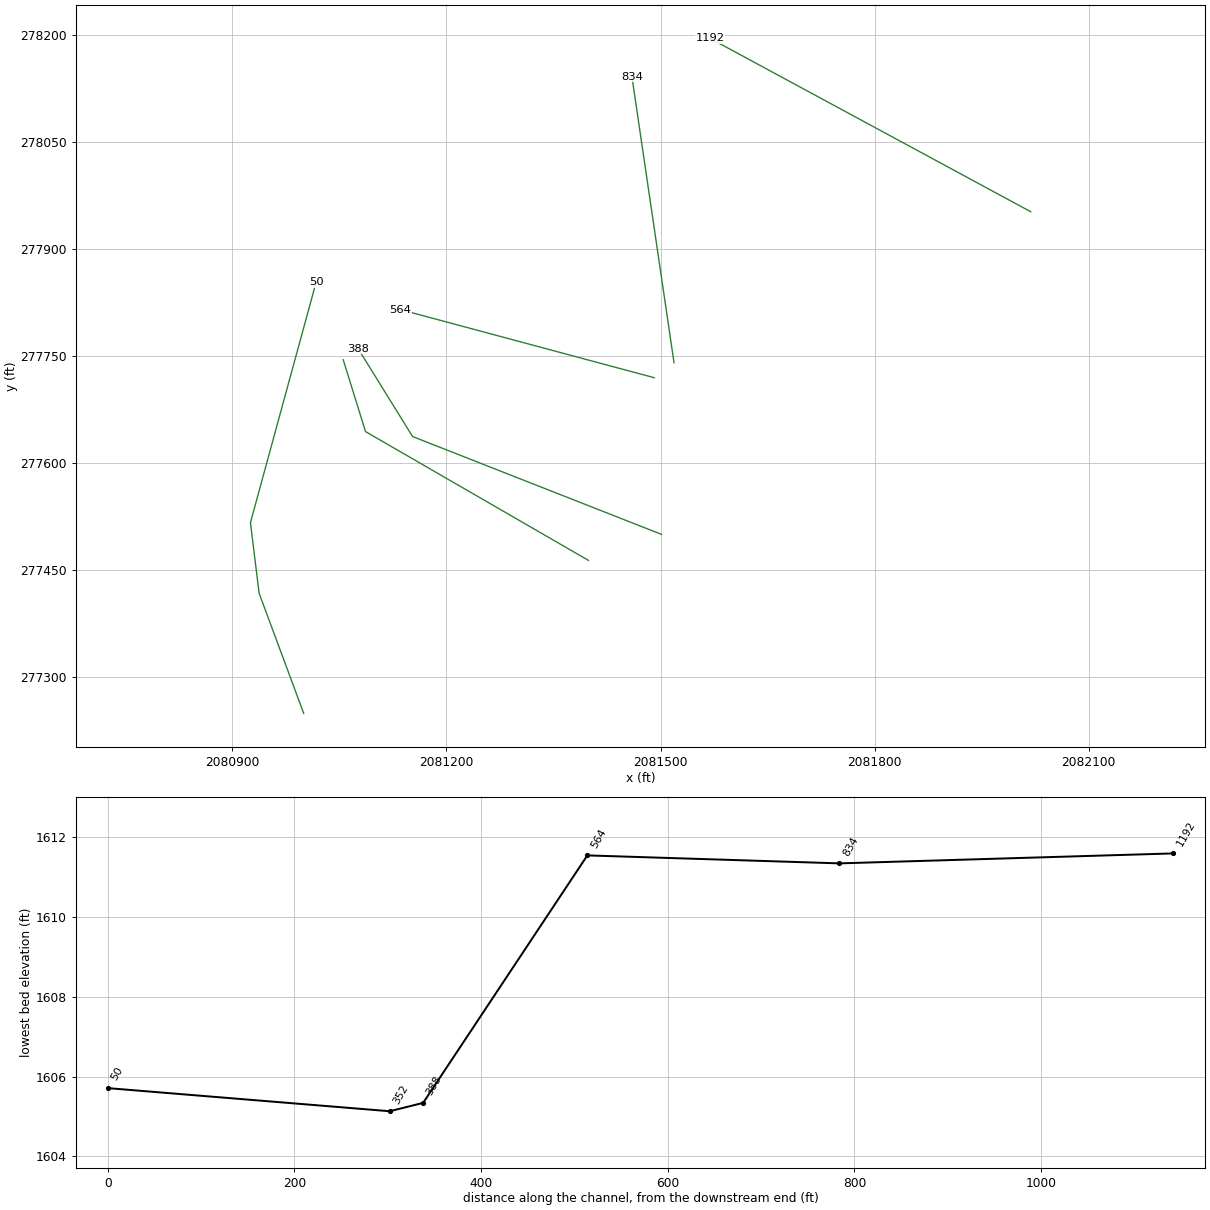
HEC-RAS study MILLCK1.prj: MILLCK1

--- MILLCK1.g01 (geometry) --- (continued)

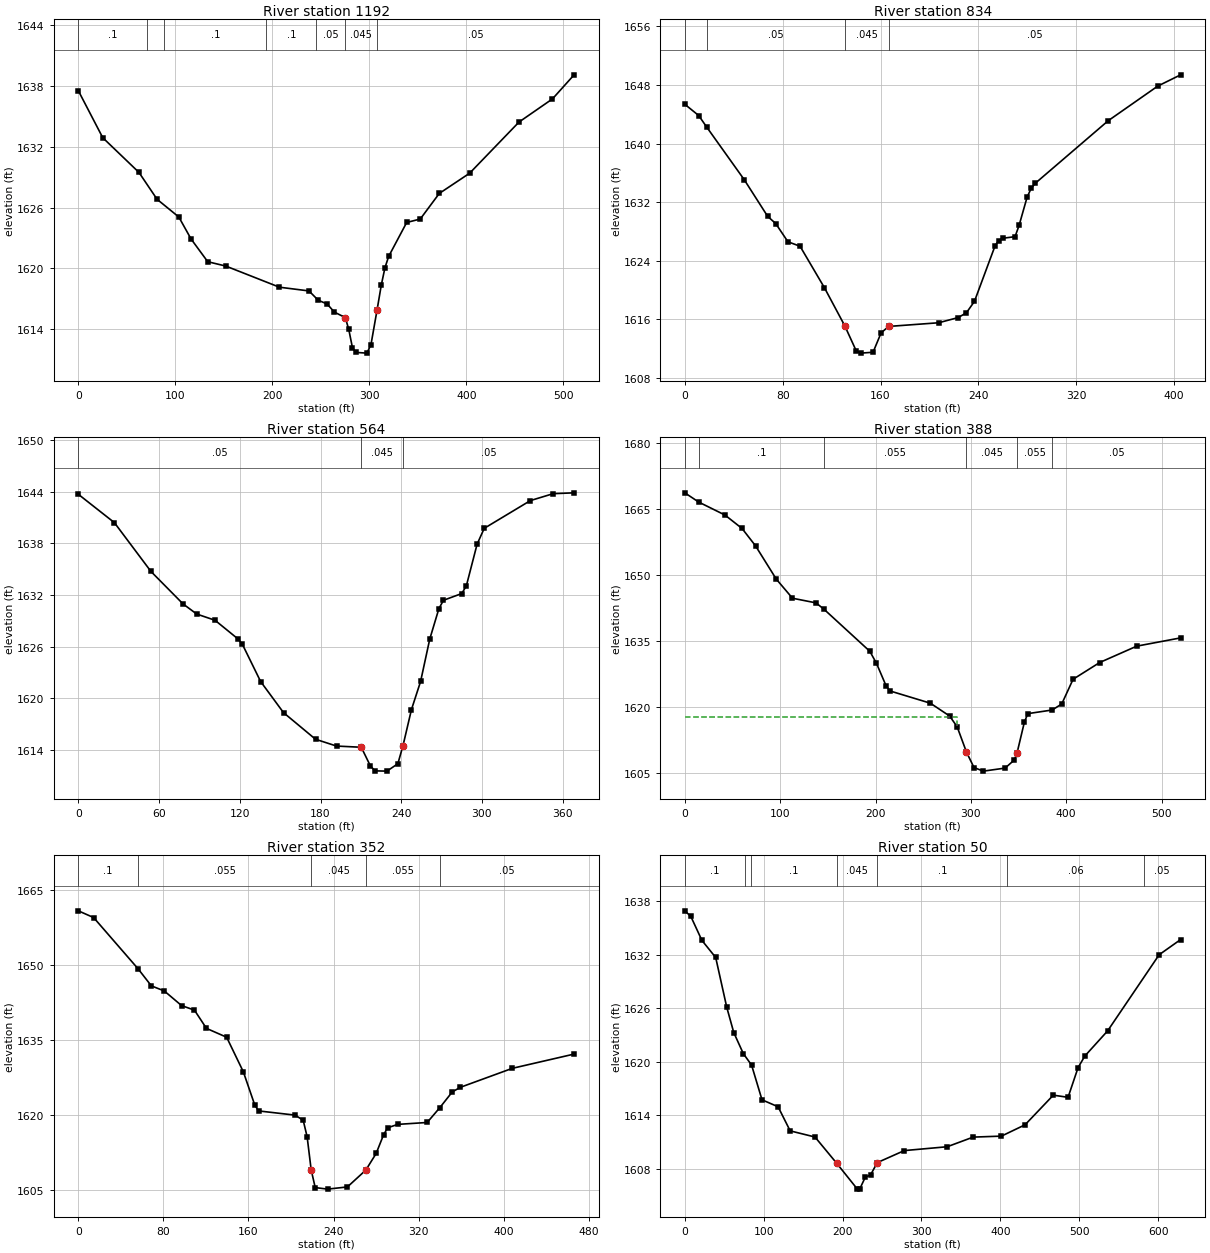
Type RM Length L Ch R = 1 ,1192    ,373.1,357.8,341.1
XS GIS Cut Line= 2
 2082018.9554016277952.7442953742081569.30242953278195.799583539
#Sta/Elev= 30
       0 1637.55    25.2  1632.9    62.5 1629.47    81.2 1626.81   103.6 1625.06
   116.2 1622.89   133.4 1620.64     152 1620.21   207.3 1618.12   237.8 1617.75
   247.3 1616.83   256.5 1616.46   263.9 1615.66  275.231615.113   278.8 1613.94
   282.6 1612.13   286.3 1611.67   297.5  1611.6   301.7 1612.45  307.991615.878
   312.4 1618.37   316.1 1620.04   319.9 1621.16   338.5 1624.52   352.5 1624.86
   372.1 1627.39   403.4 1629.39   454.3 1634.45   488.8 1636.74   511.1 1639.12
#Mann= 7 ,-1 , 0
       0      .1       0   70.98      .1       0   88.81      .1       0
  193.98      .1       0  245.22     .05       0  275.23    .045       0
  307.99     .05       0
Bank Sta=275.23,307.99
XS Rating Curve= 0 ,0
Exp/Cntr=0.3,0.1

Type RM Length L Ch R = 1 ,834     ,244.7,270.1,286.4
XS GIS Cut Line= 2
2081518.95541736277740.9386166332081459.92764828278141.980137378
#Sta/Elev= 30
       0 1645.36    11.3 1643.83    17.9 1642.24    48.5 1635.07    67.7 1630.05
    74.3 1629.06    84.3 1626.57    94.2 1625.96   114.1  1620.3  130.761615.089
   140.1 1611.67   143.9 1611.35   153.9 1611.47   160.5 1614.13  166.72    1615
   207.5  1615.5   223.5 1616.21   230.2 1616.86   236.8 1618.42   253.7 1626.03
   256.6 1626.74     260 1627.05     270 1627.27   273.3  1628.8   279.9 1632.69
   283.2 1633.87   286.5 1634.56   346.2 1643.12   386.7 1647.85   405.4 1649.39
#Mann= 4 ,-1 , 0
       0      .1       0    17.9     .05       0  130.76    .045       0
  166.72     .05       0
Bank Sta=130.76,166.72
XS Rating Curve= 0 ,0
Exp/Cntr=0.3,0.1

Type RM Length L Ch R = 1 ,564     ,178.1,175.9,175.3
XS GIS Cut Line= 2
2081491.17758578277720.1053249542081135.27475429 277815.59135446
#Sta/Elev= 30
       0 1643.68    26.8 1640.39      54 1634.72    77.8 1630.96      88 1629.78
   101.6 1629.06   118.6  1626.9     122 1626.25   135.5 1621.95   152.5 1618.34
   176.3 1615.25   191.9 1614.46   210.3 1614.32   217.1 1612.15   220.5 1611.58
   229.4 1611.55   237.5 1612.41  241.311614.502   247.6 1618.69   254.4 1621.96
   261.2 1626.87     268 1630.41   271.4 1631.38     285 1632.16   288.4 1633.05
   296.4 1637.89   301.7 1639.73     336 1642.95   352.9 1643.75   368.5 1643.85
#Mann= 3 , 0 , 0
       0     .05       0   210.3    .045       0  241.31     .05       0
Bank Sta=210.3,241.31
XS Rating Curve= 0 ,0
Exp/Cntr=0.5,0.3

Type RM Length L Ch R = 1 ,388     ,38.9,35.8,31.2
XS GIS Cut Line= 3
2081501.43150228277500.4955279682081152.47321069277637.648140788
2081076.08458394277760.912001878
#Sta/Elev= 30
       0 1668.71    14.5 1666.61    42.1 1663.65      60 1660.59    74.1 1656.65
    95.9 1649.06   112.9 1644.71   137.6 1643.65   146.1 1642.17     194 1632.63
     201 1629.88     211  1624.8   215.1  1623.6   257.5 1620.81   277.7 1617.89
   285.6 1615.44   295.4 1609.66   303.3 1606.15   313.1 1605.34   335.9 1606.03
   345.6 1607.89   348.5 1609.54   356.1 1616.48   359.7 1618.43   385.3 1619.26
   395.3 1620.63   407.2 1626.26   435.1 1630.07     474  1633.8     520 1635.68
#Mann= 6 ,-1 , 0
       0     .05       0    14.5      .1       0   146.1    .055       0
   295.4    .045       0   348.5    .055       0   385.3     .05       0
#XS Ineff= 2 , 0
           285.4  1617.7   358.5          1617.7
Permanent Ineff=
       F       F
Bank Sta=295.4,348.5
XS Rating Curve= 0 ,0
Exp/Cntr=0.5,0.3

Type RM Length L Ch R = 1 ,352     ,323.1,302.1,275.5
XS GIS Cut Line= 3
2081399.00126094277464.0372675512081086.50122976277644.592680708
2081055.25096419277745.287033126
#Sta/Elev= 30
       0 1660.79    14.4 1659.44    56.1 1649.22    68.7 1645.78    80.8 1644.77
    97.1 1641.84   109.2 1640.93   120.5 1637.28   139.5 1635.51   155.2 1628.59
     166 1621.92   169.6 1620.77   203.9 1619.93   211.5  1618.9   215.2  1615.6
     219 1608.98   222.8 1605.44   234.4 1605.13   253.1 1605.57   270.4 1608.94
   280.1 1612.26   287.2 1616.05     291  1617.4   300.4 1618.08   328.1 1618.46
   340.1 1621.45   351.7 1624.57   359.4  1625.5   408.2 1629.29   466.3 1632.14
#Mann= 5 ,-1 , 0
       0      .1       0    56.1    .055       0     219    .045       0
   270.4    .055       0   340.1     .05       0
Bank Sta=219,270.4
XS Rating Curve= 0 ,0
Exp/Cntr=0.5,0.3

Type RM Length L Ch R = 1 ,50      ,51.29,50.27,49.25
XS GIS Cut Line= 4
2080999.85803035277249.6190612172080937.35815537277418.021939635
2080925.20529252277516.9804031252081017.21921611277853.785831884
#Sta/Elev= 30
       0  1636.9     7.6 1636.27    21.6 1633.59    39.1 1631.67    53.1  1626.1
      62 1623.26    74.1  1620.9    84.6 1619.61    97.8 1615.72   118.2 1614.94
   133.5 1612.24     165 1611.55  192.491608.609   218.7 1605.71     222 1605.78
   228.7 1607.04   235.4  1607.3  243.951608.682   278.2 1610.03   332.6 1610.46
   365.5 1611.54   401.3 1611.65   431.3 1612.92   467.1 1616.24   485.8    1616
   498.5 1619.33   507.1 1620.63   535.9 1623.44   601.3 1631.98   628.5 1633.68
#Mann= 7 ,-1 , 0
       0      .1       0   76.54    .055       0    83.3      .1       0
  192.49    .045       0  243.95      .1       0  408.89     .06       0
  581.93     .05       0
Bank Sta=192.49,243.95
XS Rating Curve= 0 ,0
Exp/Cntr=0.3,0.1
LCMann Table=0

Chan Stop Cuts=-1
Use User Specified Reach Order=0
Composite Channel Slope=5